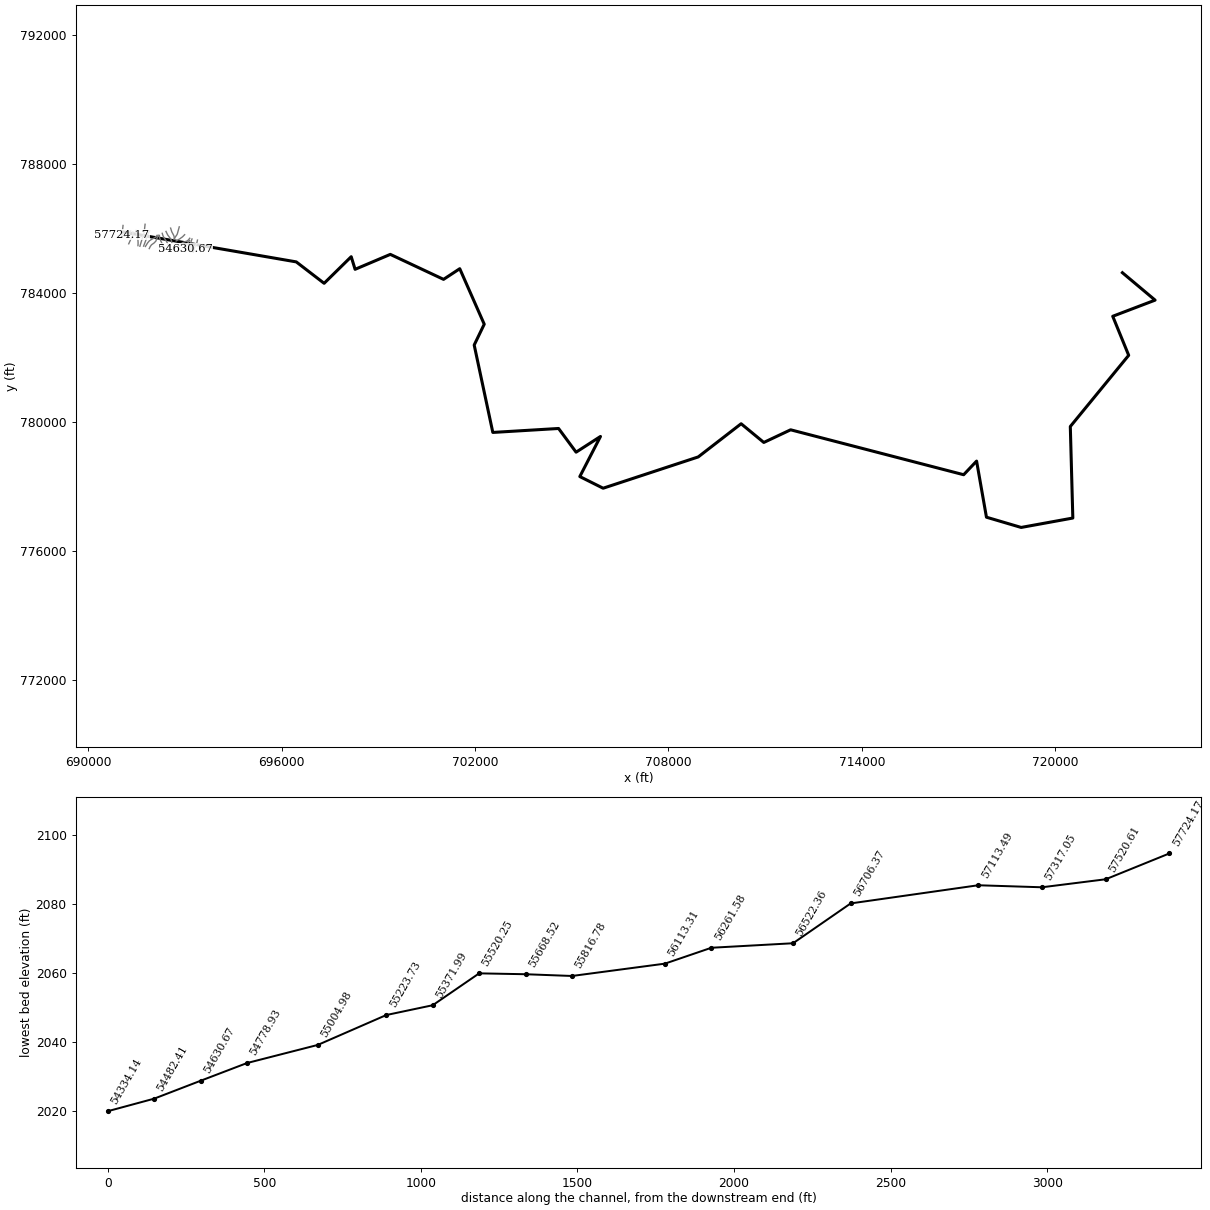
--- 14536_ras.prj (project) ---

Proj Title=14536
Current Plan=p01
Default Exp/Contr=0.3,0.1
English Units
Geom File=g01
Flow File=f01
Plan File=p01
Y Axis Title=Elevation
X Axis Title(PF)=Main Channel Distance
X Axis Title(XS)=Station
BEGIN DESCRIPTION:
RFD model 14536 exported to HEC-RAS
END DESCRIPTION:

--- 14536_ras.p01 (plan) ---

Plan Title=Plan 01
Program Version=4.10
Short Identifier=Plan 01
Geom File=g01
Flow File=f01
Subcritical Flow
Calc Critical at every XS
Secant Critical Depth

--- 14536_ras.f01 (steady flow) ---

Flow Title=Flow 01
Program Version=5.01
Number of Profiles= 6
Profile Names=10yr,25yr,50yr,100yr,100plus,500yr
River Rch & RM=14536,235,57724.17
  367.88  609.64  842.64 1063.71 1553.02 2501.74
River Rch & RM=14536,235,57520.61
  458.28  764.28 1060.98  1344.2 1962.53 3082.77
River Rch & RM=14536,235,57317.05
  460.86  768.69 1067.19 1352.18 1974.18 3098.99
River Rch & RM=14536,235,57113.49
   462.9  772.18 1072.13 1358.53 1983.45 3111.94
River Rch & RM=14536,235,56706.37
  482.28  805.21 1118.67  1418.2 2070.58 3232.38
River Rch & RM=14536,235,56522.36
  484.29  808.66 1123.55 1424.48 2079.74 3245.12
River Rch & RM=14536,235,56261.58
  486.79  812.96 1129.63 1432.31 2091.17 3261.02
River Rch & RM=14536,235,56113.31
  487.29  813.81 1130.84 1433.87 2093.45  3264.2
River Rch & RM=14536,235,55816.78
  746.25  1256.9  1756.9  2238.3 3267.91 4833.57
River Rch & RM=14536,235,55668.52
  802.31 1351.65 1889.76 2407.76 3515.33 5146.75
River Rch & RM=14536,235,55520.25
  804.11 1354.73 1894.13 2413.39 3523.55 5157.37
River Rch & RM=14536,235,55371.99
  805.92 1357.85 1898.53 2419.05 3531.81 5167.98
River Rch & RM=14536,235,55223.73
   824.5 1389.56 1943.29 2476.48 3615.66 5274.92
River Rch & RM=14536,235,55004.98
  825.61 1391.47    1946 2479.98 3620.77  5281.5
River Rch & RM=14536,235,54778.93
  893.86 1506.65 2107.37 2685.63 3921.02 5654.94
River Rch & RM=14536,235,54630.67
  894.51 1507.77 2108.96 2687.68 3924.02 5658.78
River Rch & RM=14536,235,54482.41
 1038.58 1756.46 2462.48 3144.12 4590.42 6500.94
River Rch & RM=14536,235,54334.14
 1039.83 1758.62 2465.56  3148.1 4596.23 6508.21
River Rch & RM=14536,235,54185.88
  1041.3 1761.15 2469.16 3152.75 4603.01 6516.68
River Rch & RM=14536,235,54067.37
  1057.6  1789.1 2508.72 3203.61 4677.27 6608.41
River Rch & RM=14536,235,53889.35
 1064.27 1800.61 2525.09 3224.75 4708.14 6646.88
River Rch & RM=14536,235,53741.08
 1065.94 1803.49 2529.18 3230.04 4715.86 6656.49
River Rch & RM=14536,235,53592.82
 1089.39  1843.6 2585.87 3302.84 4822.15 6786.82
River Rch & RM=14536,235,53413.65
 1095.74  1854.5 2601.31 3322.71 4851.16 6822.51
River Rch & RM=14536,235,53296.29
 1098.84 1859.85 2608.93 3332.55 4865.53 6840.33
River Rch & RM=14536,235,53148.03
 1100.49 1862.71 2612.99  3337.8 4873.19 6849.83
River Rch & RM=14536,235,52999.76
    1104 1868.77 2621.62 3348.94 4889.45    6870
River Rch & RM=14536,235, 52851.5
 1108.12 1875.88 2631.74 3362.02 4908.55 6893.69
River Rch & RM=14536,235,52703.23
 1110.77 1880.48 2638.28 3370.49 4920.91 6909.07
River Rch & RM=14536,235,52554.97
 1113.66 1885.46 2645.38 3379.65 4934.29 6925.62
River Rch & RM=14536,235,52406.71
 1133.86 1920.44 2695.19 3444.06 5028.33 7042.23
River Rch & RM=14536,235,52258.44
 1134.88  1922.2  2697.7 3447.31 5033.07  7048.1
River Rch & RM=14536,235,52110.18
 1136.09 1924.31  2700.7  3451.2 5038.75 7055.14
River Rch & RM=14536,235,51961.91
 1137.92 1927.47 2705.21 3457.03 5047.26 7065.69
River Rch & RM=14536,235,51813.65
 1138.33 1928.17 2706.21 3458.33 5049.16 7068.04
River Rch & RM=14536,235,51771.68
 1155.12 1957.18 2747.48 3511.62 5126.97 7163.91
River Rch & RM=14536,235,51474.71
 1156.94 1960.34 2751.97 3517.43 5135.45  7174.4
River Rch & RM=14536,235,51232.63
 1157.35 1961.04 2752.97 3518.73 5137.34 7176.73
River Rch & RM=14536,235,50990.55
    1176 1993.41 2799.16 3578.54 5224.67 7284.79
River Rch & RM=14536,235,50748.46
 1180.01 2000.36 2809.08 3591.38 5243.42 7307.94
River Rch & RM=14536,235,50492.37
 1183.78 2006.92 2818.45 3603.53 5261.16 7329.91
River Rch & RM=14536,235,50427.12
 1184.18 2007.61 2819.44 3604.81 5263.03 7332.22
River Rch & RM=14536,235,50316.92
 1297.41 2201.48 3093.68 3957.21 5777.53 7950.75
River Rch & RM=14536,235,50190.09
 1298.77 2203.84 3097.06  3961.6 5783.94 7958.58
River Rch & RM=14536,235,50119.03
 1299.94 2205.87 3099.96 3965.36 5789.43 7965.29
River Rch & RM=14536,235,49915.99
 1302.85 2210.94 3107.21 3974.76 5803.16 7982.06
River Rch & RM=14536,235,49635.24
 1312.74 2228.16 3131.82 4006.69 5849.76 8038.98
River Rch & RM=14536,235,49409.19
 1314.49  2231.2 3136.17 4012.31 5857.98 8049.01
River Rch & RM=14536,235,49183.14
 1727.42 2948.12 4159.64    5338 7793.4810352.49
River Rch & RM=14536,235,48957.09
  1729.6 2951.92 4165.08 5345.06 7803.79 10364.6
River Rch & RM=14536,235,48731.05
 1743.35    2976 4199.66 5390.07  7869.510442.15
River Rch & RM=14536,235,   48505
 1746.24 2981.04 4206.89 5399.46 7883.2110458.24
River Rch & RM=14536,235,48450.98
 1748.04 2984.19  4211.4 5405.32 7891.7710468.28
River Rch & RM=14536,235,48178.39
 1777.92 3036.18 4285.74 5501.74 8032.5410632.55
River Rch & RM=14536,235,47966.65
 1779.53    3039 4289.78 5506.99 8040.2110641.54
River Rch & RM=14536,235, 47557.8
 1787.42 3052.79 4309.54 5532.67  8077.710685.42
River Rch & RM=14536,235,47268.12
 1790.29  3057.8 4316.72    5542 8091.3210701.37
River Rch & RM=14536,235,46997.98
 1799.55 3073.99 4339.96 5572.22 8135.4510753.11
River Rch & RM=14536,235,46755.81
 1802.77 3079.61 4348.02  5582.7 8150.74   10771
River Rch & RM=14536,235,46513.64
 1805.63 3084.61 4355.18 5592.01 8164.3310786.89
River Rch & RM=14536,235,46271.47
 1809.71 3091.76 4365.43 5605.35 8183.8210809.72
River Rch & RM=14536,235,46060.62
 1813.63 3098.61 4375.26 5618.13 8202.4710831.54
River Rch & RM=14536,235,45787.14
 1833.91 3133.98  4425.9 5683.89 8298.4810943.34
River Rch & RM=14536,235,45544.97
 1841.68 3147.58 4445.44 5709.31  8335.610986.74
River Rch & RM=14536,235, 45302.8
 1847.87 3158.41 4460.97 5729.53 8365.1111021.23
River Rch & RM=14536,235,45060.64
 1852.97 3167.35 4473.82 5746.25 8389.5211049.77
River Rch & RM=14536,235,44818.47
 1857.92    3176 4486.23  5762.4 8413.1111077.29
River Rch & RM=14536,235, 44576.3
 1861.62 3182.48 4495.54 5774.51 8430.7811097.92
River Rch & RM=14536,235,44334.13
 1872.21 3201.01 4522.13  5809.1 8481.2811156.77
River Rch & RM=14536,235,44091.97
 1872.92 3202.25  4523.9  5811.4 8484.6411160.69
River Rch & RM=14536,235,43607.63
 2322.99 3972.67  5614.2 7211.78 10529.213429.85
River Rch & RM=14536,235,43365.46
 2375.86 4065.72 5748.24 7386.71 10784.613720.16
River Rch & RM=14536,235,43120.83
 2378.35 4070.09 5754.53 7394.9210796.5813733.71
River Rch & RM=14536,235,42746.64
 2387.55 4086.22  5777.7 7425.0710840.6113783.34
River Rch & RM=14536,235,42582.45
 2389.22 4089.14  5781.9 7430.55 10848.613792.36
River Rch & RM=14536,235,42247.84
 2415.78 4135.53 5848.39 7516.9310974.7213933.62
River Rch & RM=14536,235,41997.88
 2421.31 4145.28 5862.46 7535.3211001.5713964.14
River Rch & RM=14536,235,41747.92
  2423.4 4148.99 5867.82 7542.3411011.81 13975.8
River Rch & RM=14536,235,41497.96
 2452.25 4199.68 5940.78 7637.4611150.6914132.42
River Rch & RM=14536,235,41216.53
 2583.84 4431.39 6274.72 8073.3811787.1414848.68
River Rch & RM=14536,235,41031.32
 2594.72 4450.59 6302.44 8109.6211840.0514908.19
River Rch & RM=14536,235,40748.08
 2601.51 4462.61 6319.84 8132.4111873.3214945.77
River Rch & RM=14536,235,40498.12
 2603.98 4467.02 6326.24 8140.82 11885.614959.75
River Rch & RM=14536,235,40248.16
 2605.98 4470.59 6331.42 8147.6411895.56 14971.1
River Rch & RM=14536,235, 39998.2
  2713.3 4659.92 6604.61 8504.6312416.76 15554.2
River Rch & RM=14536,235,39748.24
 2715.29 4663.46 6609.76  8511.412426.6415565.38
River Rch & RM=14536,235,39589.78
  2715.9 4664.54 6611.34 8513.4712429.6715568.82
River Rch & RM=14536,235,39303.97
 2749.34 4724.32 6698.31 8627.95 12596.815758.36
River Rch & RM=14536,235,38998.36
 2751.31 4727.85 6703.43 8634.6912606.6415769.48
River Rch & RM=14536,235,38785.99
 2755.09 4734.59 6713.25 8647.6112625.5115790.86
River Rch & RM=14536,235,38498.44
 2827.41 4862.92  6899.1 8891.2612981.24   16189
River Rch & RM=14536,235,38248.48
 2831.11 4869.56 6908.79 8904.0512999.9116210.16
River Rch & RM=14536,235,37998.52
 2832.44 4871.95 6912.28 8908.6513006.6216217.77
River Rch & RM=14536,235,37748.56
 2837.79 4881.54 6926.25 8927.0713033.5216248.21
River Rch & RM=14536,235, 37498.6
  2844.9 4894.29 6944.85  8951.613069.3316288.77
River Rch & RM=14536,235,37289.33
 2846.97 4898.01 6950.27 8958.7513079.77 16300.6
River Rch & RM=14536,235,37167.81
 2847.86  4899.6 6952.59 8961.8113084.2416305.66
River Rch & RM=14536,235,36998.68
 2848.74 4901.19 6954.91 8964.8713088.7116310.73
River Rch & RM=14536,235,36778.12
 2849.63 4902.78 6957.23 8967.9313093.1816315.79
River Rch & RM=14536,235,36748.72
 3176.49 5481.56 7794.5510064.4814694.1418081.83
River Rch & RM=14536,235,36663.77
 3178.94 5485.97 7800.9810072.9514706.5118095.61
River Rch & RM=14536,235,36471.05
 3179.95 5487.78 7803.6210076.4414711.6118101.28
River Rch & RM=14536,235,36319.49
 3181.11 5489.85 7806.6410080.4314717.4318107.76
River Rch & RM=14536,235,36221.09
 3182.55 5492.45 7810.4210085.4214724.7118115.86
River Rch & RM=14536,235,35971.13
 3187.46 5501.25 7823.2710102.3614749.4418143.39
River Rch & RM=14536,235,35712.09
 3189.04 5504.08  7827.410107.8214757.4218152.29
River Rch & RM=14536,235,35439.31
 3209.48 5540.85 7881.1210178.77   1486118267.89
River Rch & RM=14536,235,35170.44
  3210.9 5543.41 7884.8610183.7214868.2318275.96
River Rch & RM=14536,235,34953.22
 3254.25 5621.38 7998.7610334.1715087.8918520.72
River Rch & RM=14536,235,34703.26
 3255.38 5623.42 8001.7510338.1115093.6518527.14
River Rch & RM=14536,235,34408.65
 3258.49 5629.03 8009.9510348.9615109.48 18544.8
River Rch & RM=14536,235,34088.75
 3262.88 5636.93  8021.510364.2415131.7918569.68
River Rch & RM=14536,235, 33875.1
 3263.59  5638.2 8023.37 10366.715135.3918573.69
River Rch & RM=14536,235, 33789.7
 3264.15 5639.22 8024.8610368.6715138.2618576.89
River Rch & RM=14536,235,33715.43
 3264.58 5639.99 8025.9810370.1515140.42 18579.3
River Rch & RM=14536,235,33541.15
 3265.14 5641.01 8027.4710372.12 15143.318582.51
River Rch & RM=14536,235,33476.05
 3265.99 5642.53  8029.710375.0815147.6118587.32
River Rch & RM=14536,235,33180.16
 3293.31 5691.88 8101.9810470.7615287.3118743.43
River Rch & RM=14536,235, 32930.2
 3294.28 5693.64 8104.5610474.17 15292.318749.02
River Rch & RM=14536,235,32680.24
  3296.5 5697.65 8110.4510481.99 15303.718761.81
River Rch & RM=14536,235,32430.28
 3299.27 5702.67 8117.8110491.7515317.9518777.79
River Rch & RM=14536,235,32180.32
 3316.43 5733.75 8163.4210552.2215406.2518876.72
River Rch & RM=14536,235,31930.36
 3321.09 5742.21 8175.8610568.7415430.3618903.81
River Rch & RM=14536,235, 31680.4
 3323.84 5747.21 8183.1910578.4715444.5718919.74
River Rch & RM=14536,235,31430.44
 3326.05 5751.21 8189.0710586.2615455.9518932.48
River Rch & RM=14536,235,31180.48
 3328.12 5754.97 8194.5810593.5715466.6118944.42
River Rch & RM=14536,235,30930.52
 3329.65 5757.73 8198.6310598.9415474.4518953.17
River Rch & RM=14536,235,30680.56
 3332.15 5762.26 8205.2610607.7315487.2818967.49
River Rch & RM=14536,235, 30430.6
 3340.77 5777.77 8227.9310637.67   15531   19016
River Rch & RM=14536,235,30163.61
 3341.48 5779.04 8229.7910640.1315534.5919019.97
River Rch & RM=14536,235,29930.68
10545.5318209.8925932.1333465.9648860.3150607.48
River Rch & RM=14536,235,29680.72
10549.0518216.2825941.5333478.43 48878.5 50624.8
River Rch & RM=14536,235,29430.76
 10558.818233.9525967.4933512.8148928.7150672.39
River Rch & RM=14536,235, 29180.8
10561.4418238.7425974.5333522.1648942.3650685.37
River Rch & RM=14536,235,28930.84
10565.3518245.8725985.0433536.1248962.7350704.84
River Rch & RM=14536,235,28680.88
10567.9118250.5625991.9833545.3748976.2450717.82
River Rch & RM=14536,235,28430.92
10583.1418278.2426032.7133599.4349055.1750792.94
River Rch & RM=14536,235,28180.96
 10583.918279.6226034.7533602.1449059.1350796.72
River Rch & RM=14536,235,   27931
10596.5918302.9326069.2833648.2149126.3850861.54
River Rch & RM=14536,235,27681.04
10600.1118309.3826078.8233660.9149144.9350879.36
River Rch & RM=14536,235,27431.08
10615.7318337.9226120.9433716.9549226.7450957.63
River Rch & RM=14536,235,27181.12
10617.7318341.5926126.3833724.2249237.3650967.88
River Rch & RM=14536,235,26931.16
10641.72 18385.3 26190.833809.8149362.3351087.07
River Rch & RM=14536,235, 26681.2
10647.7718396.4626207.3733831.9649394.6651118.33
River Rch & RM=14536,235,26431.24
10654.0418408.0226224.5133854.8749428.1151150.66
River Rch & RM=14536,235,26181.28
10659.3718417.7726238.9433874.0949456.1851177.61
River Rch & RM=14536,235,25931.32
10667.7618433.15 26261.733904.4349500.4751220.15
River Rch & RM=14536,235,25681.36
10675.5718447.5626283.0933933.0449542.2351260.54
River Rch & RM=14536,235, 25431.4
10678.1618452.3526290.2133942.5549556.13   51274
River Rch & RM=14536,235,25181.44
10682.9218461.1526303.2833960.0449581.6651298.75
River Rch & RM=14536,235,24931.48
10684.8918464.7826308.6833967.2749592.2151308.98
River Rch & RM=14536,235,24681.53
10687.8818470.31 26316.933978.29 49608.351324.59
River Rch & RM=14536,235,24431.57
10689.9418474.1326322.5833985.8949619.3951335.35
River Rch & RM=14536,235, 24149.1
10982.8419007.9127109.4935031.64 51146.2 52787.6
River Rch & RM=14536,235,23931.65
10985.7219013.2227117.3935042.2251161.64 52802.5
River Rch & RM=14536,235,23681.69
10986.95 19015.527120.7835046.7551168.2652808.89
River Rch & RM=14536,235,23431.73
11558.7820036.8928608.3837002.7654024.0355439.68
River Rch & RM=14536,235,23181.77
 11559.920038.9528611.4537006.8654030.0255445.42
River Rch & RM=14536,235,22931.81
11579.9520076.0828666.7337080.9454138.1855549.26
River Rch & RM=14536,235,22681.85
11582.8820081.51 28674.837091.7554153.9655564.39
River Rch & RM=14536,235,22431.89
 11584.720084.8828679.8137098.4654163.7655573.78
River Rch & RM=14536,235,22181.93
11592.1620098.6928700.36   3712654203.9655612.37
River Rch & RM=14536,235,21931.97
11594.1820102.4328705.9237133.4554214.8455622.79
River Rch & RM=14536,235,21682.01
11599.5220112.3128720.6437153.1754243.6355650.43
River Rch & RM=14536,235,21432.05
11602.6420118.0928729.2437164.7154260.4755666.58
River Rch & RM=14536,235,20932.13
11652.8620211.2128867.9637350.7154532.0455927.46
River Rch & RM=14536,235,20682.17
11656.7820218.4728878.77 37365.254553.1955947.75
River Rch & RM=14536,235,20432.21
11684.1920269.3628954.6437467.0254701.8656090.73
River Rch & RM=14536,235,20182.25
 11688.220276.7928965.7237481.8754723.5356111.51
River Rch & RM=14536,235,19932.29
11692.6120284.9628977.8937498.1854747.3456134.38
River Rch & RM=14536,235,19682.33
11699.9620298.6328998.2737525.5454787.2956172.81
River Rch & RM=14536,235,19432.37
 11706.220310.1729015.4537548.56 54820.956205.01
River Rch & RM=14536,235,19182.41
11718.01 20331.929047.6637591.5954883.7256264.71
River Rch & RM=14536,235,18932.45
11723.4420341.9529062.6237611.6354912.9756292.73
River Rch & RM=14536,235,18682.49
11726.0420346.7829069.8137621.2754927.0556306.22
River Rch & RM=14536,235,18182.57
11753.9320398.2529146.3137723.6255076.4956448.84
River Rch & RM=14536,235,17682.65
11760.8520411.1329165.5337749.4455114.1956485.12
River Rch & RM=14536,235,17182.73
11764.11 20417.229174.58 37761.655131.9456502.22
River Rch & RM=14536,235,16824.88
11810.6720502.76 29301.437930.9155379.1356736.76
River Rch & RM=14536,235,16432.85
11813.1520507.3829308.2837940.1455392.6156749.69
River Rch & RM=14536,235,16208.55
11813.4420507.9229309.0937941.2455394.2156751.24
River Rch & RM=14536,235,15932.93
 11884.420641.0329508.78 38210.655787.48   57133
River Rch & RM=14536,235,15682.97
 11887.1 20646.129516.3738220.8255802.4157147.45
River Rch & RM=14536,235,15433.01
11888.7820649.2229521.0338227.0755811.5357156.22
River Rch & RM=14536,235,15183.05
11891.7620654.7529529.2638238.1455827.68 57171.7
River Rch & RM=14536,235,14683.13
11900.9320671.7529554.5938272.0955877.2657219.14
River Rch & RM=14536,235,14183.21
11920.9120708.6429609.4238345.48 55984.457321.19
River Rch & RM=14536,235,13933.25
11926.0220718.0329623.3538364.0856011.5557346.95
River Rch & RM=14536,235,13683.29
11928.2220722.1129629.4238372.2156023.4357358.28
River Rch & RM=14536,235,13433.33
11933.1920731.2729643.0238390.3956049.9857383.52
River Rch & RM=14536,235,13183.37
 11934.920734.4329647.7238396.6956059.1757392.27
River Rch & RM=14536,235,12933.41
12026.5120899.7829890.1438717.2956527.2557825.26
River Rch & RM=14536,235,12433.49
 12356.821487.9930745.4139840.1258166.5859310.48
River Rch & RM=14536,235,11933.58
12362.9521499.4230762.4839863.0658200.07 59342.5
River Rch & RM=14536,235,11683.62
12364.5121502.3330766.82 39868.958208.5959350.63
River Rch & RM=14536,235,11433.66
 12366.521506.01 30772.339876.23 58219.3 59360.8
River Rch & RM=14536,235, 11183.7
12369.1721510.9630779.6639886.1158233.7159374.52
River Rch & RM=14536,235,10933.74
12372.2521516.7230788.2939897.7158250.6659390.78
River Rch & RM=14536,235,10683.78
 12373.421518.8730791.5139902.05   5825759396.88
River Rch & RM=14536,235,10433.82
12374.7421521.3830795.2639907.1258264.3959403.99
River Rch & RM=14536,235,10183.86
12390.1421550.2130838.4639965.3358349.3959485.77
River Rch & RM=14536,235,9737.191
12442.4821648.6630986.4140165.1758641.1559767.84
River Rch & RM=14536,235,9433.977
12445.2621653.8530994.1840175.6558656.4559782.54
River Rch & RM=14536,235,9184.017
12470.4521701.1931065.2740271.6358796.57 59917.8
River Rch & RM=14536,235,8911.261
12471.0921702.4131067.1140274.1258800.2259921.34
River Rch & RM=14536,235,8684.097
12478.02 21715.531086.8540300.8758839.2759959.31
River Rch & RM=14536,235,8434.138
12478.9421717.2531089.4840304.4458844.4859964.38
River Rch & RM=14536,235,8184.178
12483.5521725.9831102.6540322.26 58870.559989.68
River Rch & RM=14536,235,7934.218
12486.7821732.0931111.8640334.7558888.73 60007.4
River Rch & RM=14536,235,7684.258
12491.7521741.4931126.0540353.9858916.8160034.72
River Rch & RM=14536,235,7434.298
 12495.321748.2531136.2540367.8358937.0360054.45
River Rch & RM=14536,235,6934.379
12498.4621754.2631145.35 40380.258955.0960072.16
River Rch & RM=14536,235,6684.419
12546.7221845.9331283.8840568.2159229.5860340.02
River Rch & RM=14536,235,6473.801
12548.3321849.0131288.5540574.5759238.8760349.11
River Rch & RM=14536,235,6184.499
12563.1621877.1731331.1140632.3459323.2160431.39
River Rch & RM=14536,235, 5934.54
   1257421897.8131362.3340674.7659385.1560491.94
River Rch & RM=14536,235, 5684.58
12576.1521901.9131368.5540683.22 59397.560504.04
River Rch & RM=14536,235, 5434.62
 12591.421931.0131412.6340743.1659485.0260589.77
River Rch & RM=14536,235, 5184.66
12608.6421963.9431462.5440811.09 59584.260687.04
River Rch & RM=14536,235,  4934.7
12618.4821982.6631490.8740849.59 59640.460741.95
River Rch & RM=14536,235,4684.741
12620.3421986.2231496.2840856.9659651.1660752.52
River Rch & RM=14536,235,4184.821
12620.69 21986.931497.3140858.3659653.2160754.54
Boundary for River Rch & Prof#=14536,235,1
Up Type= 0
Dn Type= 2
Boundary for River Rch & Prof#=14536,235,2
Up Type= 0
Dn Type= 2
Boundary for River Rch & Prof#=14536,235,2
Up Type= 0
Dn Type= 2
Boundary for River Rch & Prof#=14536,235,2
Up Type= 0
Dn Type= 2
Boundary for River Rch & Prof#=14536,235,2
Up Type= 0
Dn Type= 2
Boundary for River Rch & Prof#=14536,235,2
Up Type= 0
Dn Type= 2

--- 14536_ras.g01 (geometry) ---

Geom Title=14536
Program Version=4.10

River Reach=14536,235
Reach XY= 30
691066.474807233785894.176699042696452.933140606784964.315587908
 697317.51647386784299.732254595698158.089390576785125.201004595
698278.401890606784733.951004595699371.283834964785197.145449042
701022.603279412784422.180171236701525.381057262784752.735726848
702284.825501621783030.791282371701973.170409143782384.876930505
702551.434297919779673.140819415704591.384889543779796.019834548
705134.489853501 779060.50193052   705891.572678779548.576349869
705250.259490907778303.989167243705973.349758148777942.444157407
708923.678883731778913.271832779710254.669173658779942.687100276
710958.011163473779362.391983211711790.345550448 779754.93849948
717158.532190561778361.089893445717559.573829949778784.266858906
717865.563279927 777043.38153258718942.386329651776725.673452467
720545.250792772777017.339758962720467.126014024 779857.18355383
722278.259242445782065.883740678721783.410200804783276.837735668
723097.710697979783777.630017161722083.460651994 784628.52443184

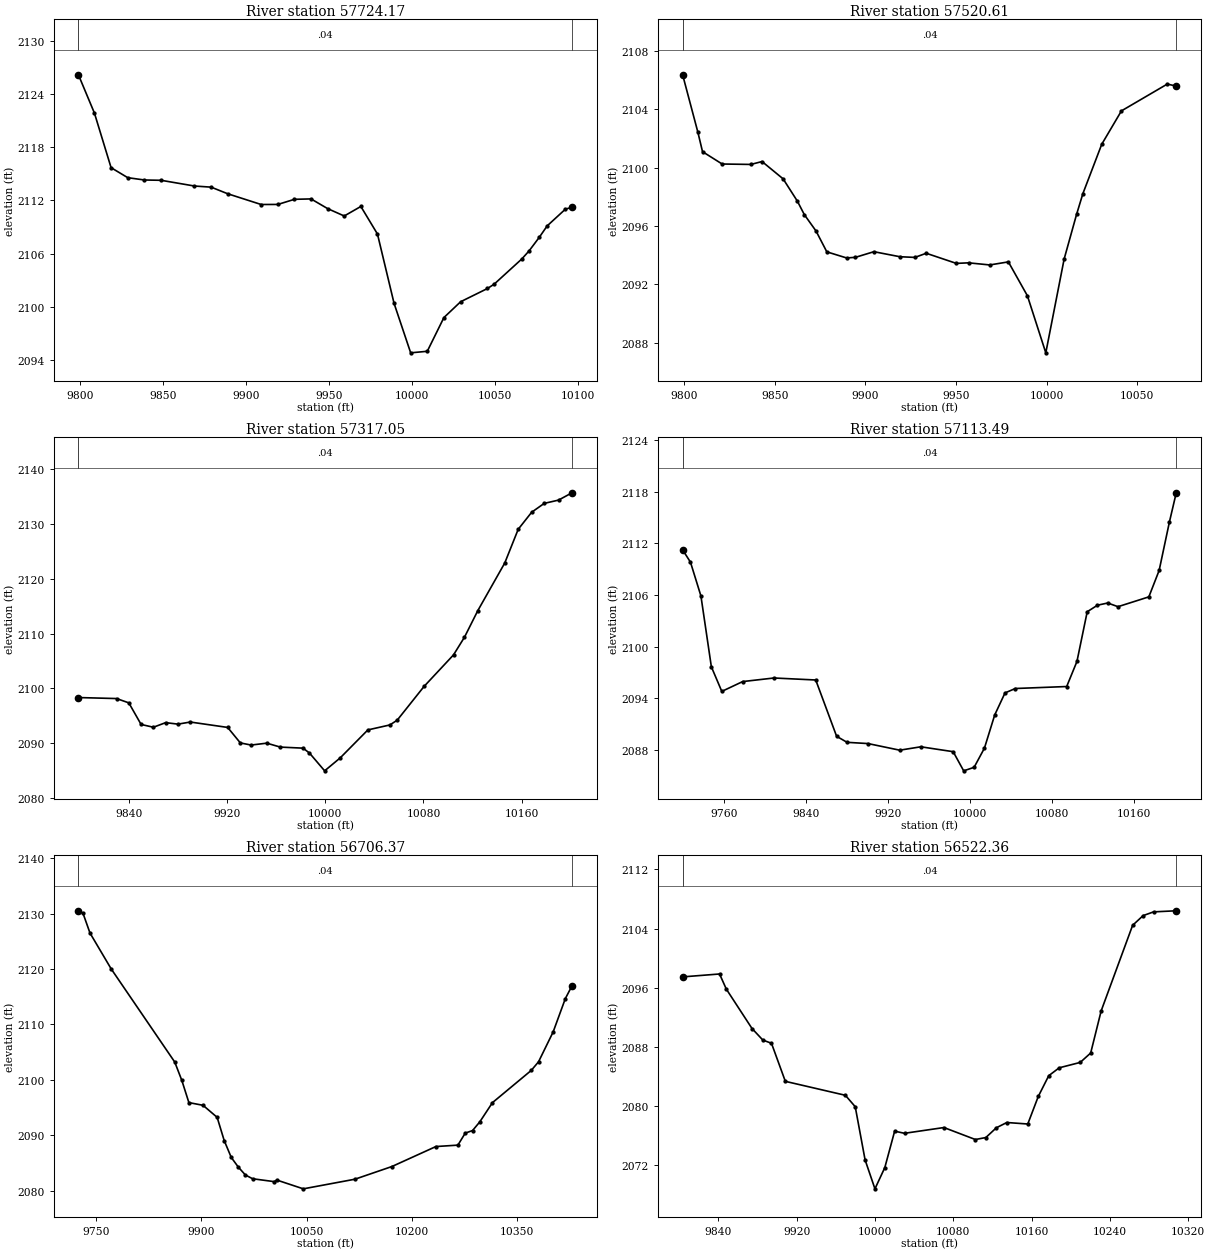
Type RM Length L Ch R = 1 ,57724.17,203.560800,203.560800,203.560800
XS GIS Cut Line= 6
691078.765825612786094.596827027691067.169147632785977.358097713
691067.960380219785877.634864389691064.887807605785848.888250123
691059.243033909785828.999922044 691047.00350397785801.314370389
#Sta/Elev= 30
9799.0292126.1519808.6732121.8369818.7212115.679 9828.77 2114.559838.819 2114.29
9848.8682114.2569868.965 2113.619879.0142113.4849889.0632112.7339909.1612111.527
9919.1992111.5349929.2032112.1129939.2062112.157 9949.212111.0649959.2142110.232
9969.2212111.3069979.2292108.1999989.2372100.3849999.2452094.80510009.252094.981
10019.272098.78110029.332100.56310045.532102.05910049.572102.549 10066.22105.385
10070.582106.294 10076.72107.81910081.512109.11910092.452110.99810096.472111.219
#Mann= 3 , 0 , 0
9799.029    0.04       09799.029    0.04       010096.47    0.04       0
#XS Ineff= 2 , 0
       0                               0
Bank Sta=9799.029,10096.47
Exp/Cntr=0.3,0.1

Type RM Length L Ch R = 1 ,57520.61,203.560800,203.560800,203.560800
XS GIS Cut Line= 6
691318.223486101785925.136238031691291.099402314785868.086041645
691249.248111046785818.781066102691214.708077014785796.364320543
691154.271451865785780.895742066691118.482777813785762.493426759
#Sta/Elev= 30
9799.1592106.3639807.5812102.419 9810.132101.0939820.9542100.2479836.7862100.218
9842.9742100.4169854.5822099.231 9862.452097.7039866.282 2096.789872.7362095.658
9878.7012094.2279889.6012093.8099894.4792093.8519904.6762094.2379919.0222093.892
9927.2732093.8469933.541 2094.139950.1492093.4369956.9312093.474 9968.582093.329
 9978.852093.5399989.3432091.2189999.4982087.30510009.622093.736 10016.52096.806
10019.962098.21810030.372101.60310041.222103.88810066.522105.72610071.462105.589
#Mann= 3 , 0 , 0
9799.159    0.04       09799.159    0.04       010071.46    0.04       0
#XS Ineff= 2 , 0
       0                               0
Bank Sta=9799.159,10071.46
Exp/Cntr=0.3,0.1

Type RM Length L Ch R = 1 ,57317.05,203.560800,203.560800,203.560800
XS GIS Cut Line= 6
691382.552269871785896.013461214 691384.72209713785811.698968193
691374.660240284785756.517684809691361.210265894785727.920450359
691316.035487826785660.413003896691255.802862973785524.968325605
#Sta/Elev= 30
9799.1592098.3349830.1822098.1519840.1862097.3679850.1892093.4339860.1922092.925
9870.1962093.7639880.199 2093.499890.2392093.8739920.6412092.8919930.9782090.067
9939.7472089.6799952.4752090.0239963.5252089.3069982.0222089.1159987.2362088.223
9999.5932084.98110012.232087.33510034.772092.43810052.722093.34410058.642094.209
10080.532100.36510104.492106.10710113.372109.31510124.312114.191 10146.22122.849
10157.14 2128.9910168.092132.09410178.322133.70910189.972134.30810200.952135.642
#Mann= 3 , 0 , 0
9799.159    0.04       09799.159    0.04       010200.95    0.04       0
#XS Ineff= 2 , 0
       0                               0
Bank Sta=9799.159,10200.95
Exp/Cntr=0.3,0.1

Type RM Length L Ch R = 1 ,57113.49,407.121700,407.121700,407.121700
XS GIS Cut Line= 6
691480.650873303785942.524246633691512.075669467 785774.46990189
691539.419047609785667.926384253691546.086877612785575.761282195
691545.692010264785521.053000424 691541.69563231785468.374756077
#Sta/Elev= 30
9719.8632111.2319727.5172109.7929737.6912105.8759747.8642097.6489758.0372094.791
9778.3842095.9339808.9042096.3499849.5972096.1169869.944 2089.589880.1172088.879
9900.5782088.7349931.4582087.9669952.045 2088.369983.5492087.7929993.7852085.568
10003.952085.97610014.012088.20110024.062092.06310034.072094.61510044.092095.128
10094.192095.35810104.192098.27110114.192104.04110124.19  2104.810134.192105.056
10144.192104.62910174.262105.76810184.292108.83410194.322114.46810200.972117.855
#Mann= 3 , 0 , 0
9719.863    0.04       09719.863    0.04       010200.97    0.04       0
#XS Ineff= 2 , 0
       0                               0
Bank Sta=9719.863,10200.97
Exp/Cntr=0.3,0.1

Type RM Length L Ch R = 1 ,56706.37,184.004200,184.004200,184.004200
XS GIS Cut Line= 5
691763.371536076786131.393690303691735.728311628785893.661960766
691712.692291379785803.360761151 691676.03112781785693.858468205
691602.251171589785449.291576236
#Sta/Elev= 30
9724.8492130.5049731.2862130.0929741.3532126.4839771.555 2120.019862.1622103.188
9872.2292099.8769882.2972095.8719902.4312095.3839922.566 2093.219932.633 2089.01
9942.7012085.9699952.768 2084.229962.836  2082.89973.1222082.12210004.082081.597
10007.582081.88710045.36  2080.310118.922082.03910171.65 2084.3310234.332087.936
10265.672088.19210276.112090.35810286.562090.824   102972092.41410314.922095.864
10370.122101.67410380.56 2103.2310401.452108.64310418.792114.65210428.312116.969
#Mann= 3 , 0 , 0
9724.849    0.04       09724.849    0.04       010428.31    0.04       0
#XS Ineff= 2 , 0
       0                10153.76       0
Bank Sta=9724.849,10428.31
Exp/Cntr=0.3,0.1

Type RM Length L Ch R = 1 ,56522.36,260.788500,260.788500,260.788500
XS GIS Cut Line= 6
691893.946342826785919.145166561691857.578585953 785841.60680224
 691841.54396987785814.219479263691813.547734708785778.179606929
691801.730312496785674.730331421691717.019992352785453.390462697
#Sta/Elev= 30
9803.6222097.4529841.3372097.844 9848.242095.7969874.4732090.4619885.5182088.898
9894.3692088.458 9908.512083.3059969.8382081.4169979.9032079.8689989.9682072.669
10000.032068.747 10010.12071.61910020.162076.55810030.232076.26810070.492077.049
10102.592075.427 10113.32075.69510124.012077.01510134.72 2077.7310156.132077.527
10166.842081.25710177.54 2084.0710188.252085.13910209.672085.86710220.372087.141
10231.082092.847 10263.22104.43510273.912105.74910284.622106.25610307.762106.404
#Mann= 3 , 0 , 0
9803.622    0.04       09803.622    0.04       010307.76    0.04       0
#XS Ineff= 2 , 0
       0                10033.48       0
Bank Sta=9803.622,10307.76
Exp/Cntr=0.3,0.1

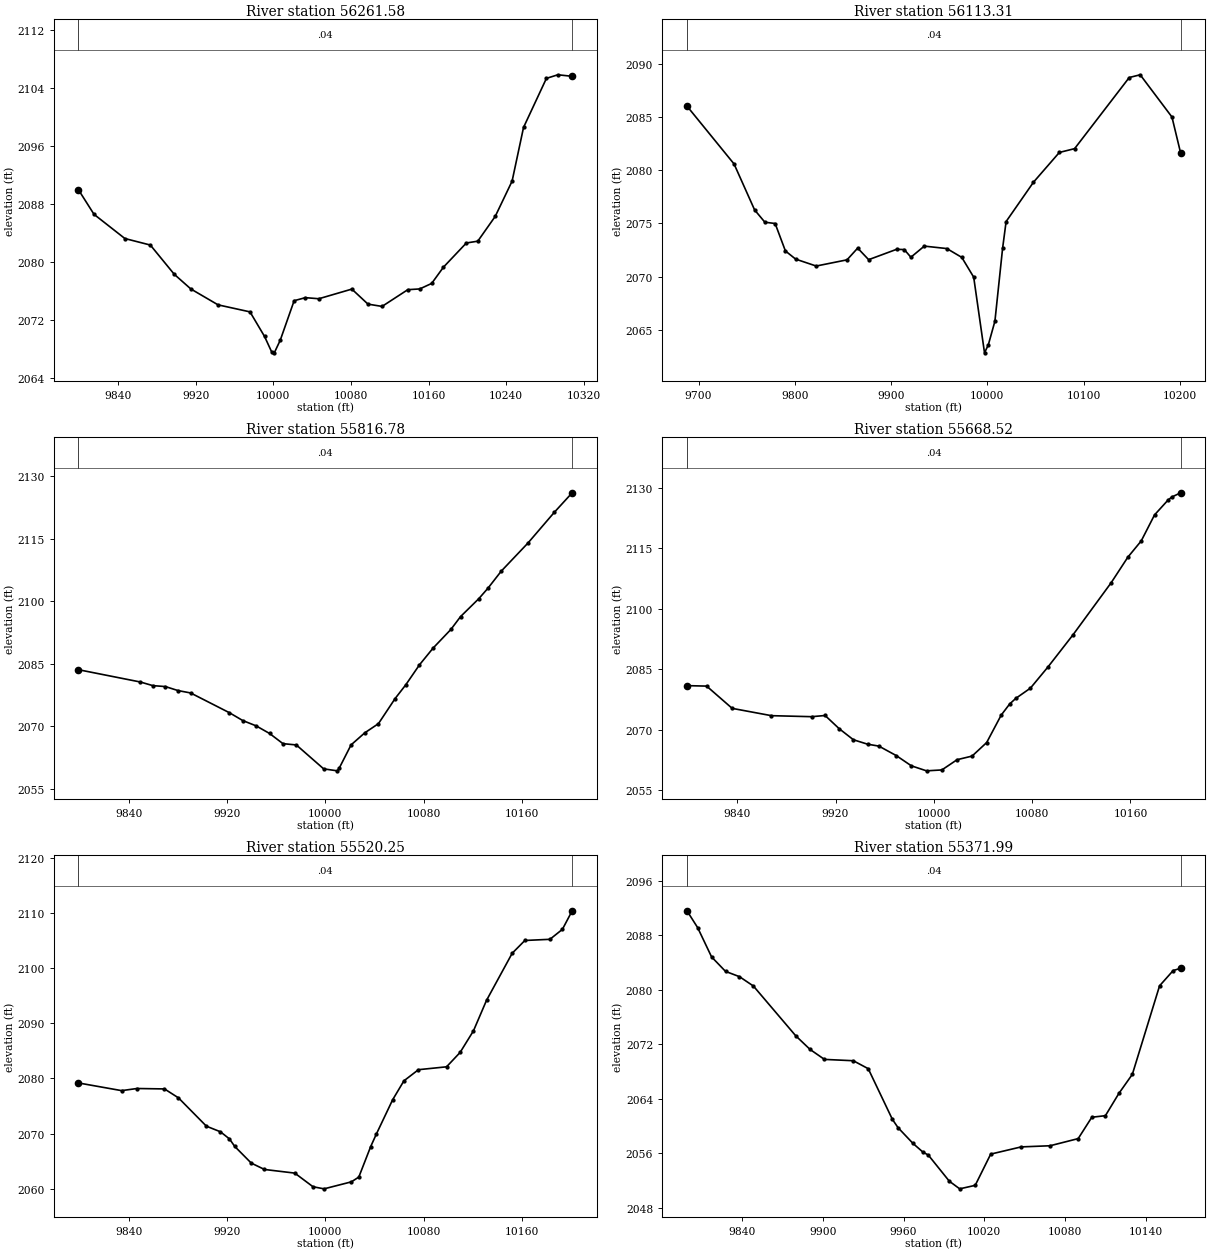
Type RM Length L Ch R = 1 ,56261.58,148.264200,148.264200,148.264200
XS GIS Cut Line= 6
692132.429117948785784.127056375692076.363882661785720.212561429
691981.310813785785673.167878404691899.377845645785621.707020238
691844.883697391785557.658792019691773.038107276785442.460098818
#Sta/Elev= 30
9799.1612089.9749815.252 2086.579847.036 2083.239873.2732082.3299897.9512078.287
9914.9972076.2649943.0422074.0689975.9612073.0989990.9822069.6979998.2852067.569
   100012067.43910007.162069.18810021.45 2074.6410033.022075.06210046.912074.912
10080.912076.24410097.562074.16610112.062073.85210138.592076.16510150.882076.266
10163.182077.02910175.342079.27910198.912082.614 10210.72082.86410228.682086.291
10246.052091.15810257.842098.57710281.412105.353 10293.2 2105.8510307.982105.639
#Mann= 3 , 0 , 0
9799.161    0.04       09799.161    0.04       010307.98    0.04       0
#XS Ineff= 2 , 0
       0                 10059.3       0
Bank Sta=9799.161,10307.98
Exp/Cntr=0.3,0.1

Type RM Length L Ch R = 1 ,56113.31,296.528500,296.528500,296.528500
XS GIS Cut Line= 6
692169.263798207785790.865447715692097.823004127785609.051943466
692041.403461546 785550.04857868691962.096318036785493.994023606
691924.285097897785442.706265718691891.956977546785376.654658139
#Sta/Elev= 30
9687.8832086.0339736.8262080.5929758.1682076.2729768.8392075.114 9779.512074.993
9790.1822072.4129800.8532071.6439822.1952070.9949854.2082071.5779865.269 2072.68
9876.6692071.5929905.6582072.5649913.6692072.5449920.5622071.8229934.5022072.867
9957.9232072.6379973.4572071.8069985.8142069.9489997.0532062.833   10001 2063.58
10007.862065.80910015.842072.66110019.492075.17610047.932078.87710074.792081.673
10090.662082.03110147.432088.71910158.792088.976 10191.82085.00610200.922081.582
#Mann= 3 , 0 , 0
9687.883    0.04       09687.883    0.04       010200.92    0.04       0
#XS Ineff= 2 , 0
       0                               0
Bank Sta=9687.883,10200.92
Exp/Cntr=0.3,0.1

Type RM Length L Ch R = 1 ,55816.78,148.264200,148.264200,148.264200
XS GIS Cut Line= 6
692207.453623122785785.373678198692211.344079162785725.475698073
692227.184703051785666.746037156692251.074560794785611.649383163
692319.793477024785471.921022827 692344.54740767785411.638997592
#Sta/Elev= 30
9799.0572083.5539849.5542080.5939859.6222079.7279869.8672079.4999880.1122078.539
9890.3572077.9689921.945 2073.229932.8452071.3359943.7442070.0579954.6442068.233
9965.5432065.7879976.4432065.4749998.6782059.73110009.842059.25610011.462059.972
10020.982065.48810032.122068.38110043.262070.58910056.852076.62810065.542079.934
10076.682084.72910087.822088.76710102.242093.226 10110.12096.30910124.932100.608
10132.382103.11910143.29 2107.2510164.912113.96210186.532121.39910200.972126.055
#Mann= 3 , 0 , 0
9799.057    0.04       09799.057    0.04       010200.97    0.04       0
#XS Ineff= 2 , 0
       0                               0
Bank Sta=9799.057,10200.97
Exp/Cntr=0.3,0.1

Type RM Length L Ch R = 1 ,55668.52,148.264300,148.264300,148.264300
XS GIS Cut Line= 6
 692295.05563411785850.484781362692312.536087607785792.041741281
692333.747942045 785743.85561719692360.246193315785697.964634788
692431.802182321785592.885982131692477.841623472785495.349467406
#Sta/Elev= 30
9799.0872080.9089815.1052080.7929835.8922075.2679867.8162073.4549900.5952073.201
9911.5212073.4979922.9972070.2179934.5442067.4779946.0922066.3749955.271  2065.9
9969.4142063.5529981.7312061.0039994.0482059.76210006.562059.98610018.95 2062.53
10031.122063.42310042.992066.77910054.852073.60310061.752076.36610066.722077.749
10078.59 2080.2810092.962085.56810113.222093.50310144.312106.44410157.922112.799
10168.772116.81610179.612123.27610190.462126.917 10193.62127.71310200.932128.772
#Mann= 3 , 0 , 0
9799.087    0.04       09799.087    0.04       010200.93    0.04       0
#XS Ineff= 2 , 0
       0                               0
Bank Sta=9799.087,10200.93
Exp/Cntr=0.3,0.1

Type RM Length L Ch R = 1 ,55520.25,148.264200,148.264200,148.264200
XS GIS Cut Line= 6
692411.507104038785909.018282223692464.475960271785799.366613792
692537.911468592 785704.01279195692562.581405495785664.825234256
692582.846458029 785615.89791871692594.927335835785557.108875998
#Sta/Elev= 30
9799.0822079.1929834.232  2077.89846.7522078.1869869.1342078.1099880.502 2076.49
 9903.242071.3639914.6092070.3539921.9452069.0719926.2942067.697 9939.732064.681
 9950.482063.5259975.1542062.8669989.9972060.394    99992060.01710021.222061.283
10027.262062.14910036.93 2067.6710041.512069.92310054.812076.15210063.972079.574
10075.792081.59310098.662082.11410109.692084.71410120.572088.63410131.182094.145
10152.072102.67410162.392104.99210182.792105.20310192.922107.00210200.912110.369
#Mann= 3 , 0 , 0
9799.082    0.04       09799.082    0.04       010200.91    0.04       0
#XS Ineff= 2 , 0
       0                               0
Bank Sta=9799.082,10200.91
Exp/Cntr=0.3,0.1

Type RM Length L Ch R = 1 ,55371.99,148.264200,148.264200,148.264200
XS GIS Cut Line= 6
692555.217763847786012.684970596692591.084047304785898.041214401
692648.801088202785790.488877844692662.826858623785754.756304142
692666.975569429785706.946674691692661.308021975785669.452427796
#Sta/Elev= 30
9799.0742091.582 9807.032089.1059817.3832084.8099827.7352082.6879838.0882081.912
 9848.442080.5399879.921 2073.239890.5822071.2269901.2442069.7699922.6932069.573
 9933.772068.4069951.6852060.9829955.9232059.7499966.9992057.4439974.4512056.157
9978.3892055.7339994.0112051.89310001.742050.77110013.262051.28310024.782055.869
 10047.42056.92610068.882057.09410089.782058.14410099.91 2061.28   101102061.507
   101202064.77110130.022067.57710150.252080.56810160.362082.81110165.972083.146
#Mann= 3 , 0 , 0
9799.074    0.04       09799.074    0.04       010165.97    0.04       0
#XS Ineff= 2 , 0
       0                               0
Bank Sta=9799.074,10165.97
Exp/Cntr=0.3,0.1

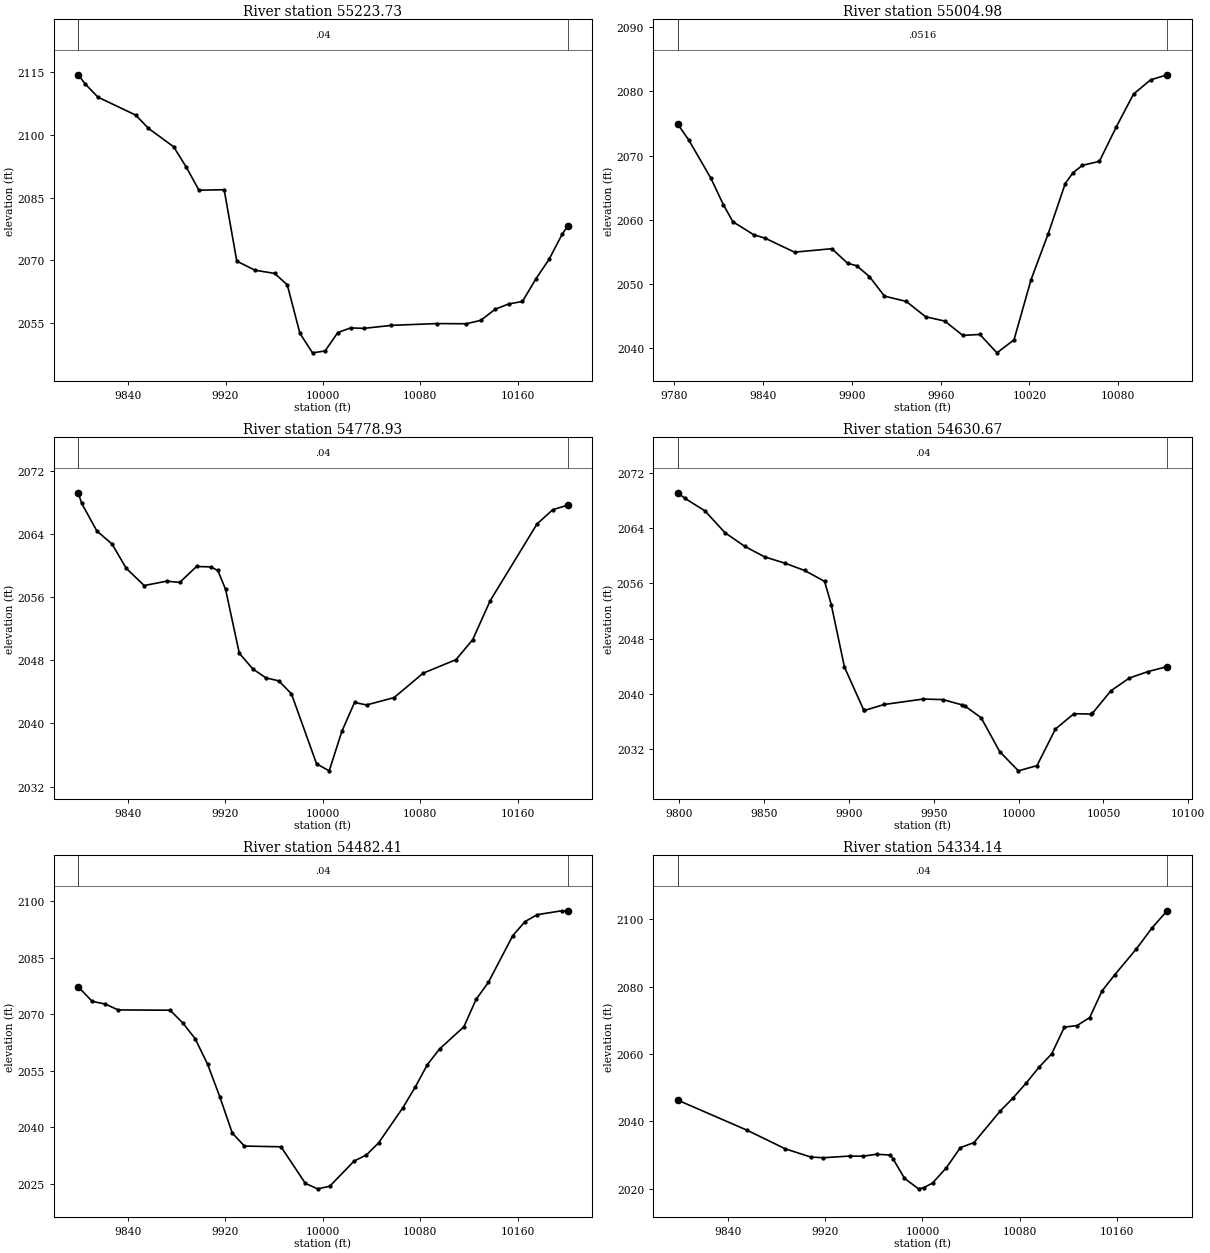
Type RM Length L Ch R = 1 ,55223.73,218.748100,218.748100,218.748100
XS GIS Cut Line= 6
692823.248480474786050.658278711692761.915578934785829.396445631
692749.799885214  785806.1496818692700.840052774 785735.56386316
 692687.55282431785709.367797371 692676.18932035785680.845418339
#Sta/Elev= 30
9799.012 2114.319804.8782112.0829815.2442108.9729846.3422104.6669856.7082101.519
 9877.442097.1119887.8062092.2469898.1722086.7519918.904 2086.87 9929.272069.814
9944.2352067.6459960.3682066.8939970.7342064.152  9981.12052.5899991.4662047.926
10001.772048.37410012.25 2052.7810022.77 2053.8810033.632053.76510056.312054.489
10093.512054.91310117.782054.86710129.642055.68110141.462058.33610152.682059.606
10163.892060.19710174.912065.59510185.672070.21710196.432076.21910200.912078.118
#Mann= 3 , 0 , 0
9799.012    0.04       09799.012    0.04       010200.91    0.04       0
#XS Ineff= 2 , 0
       0                               0
Bank Sta=9799.012,10200.91
Exp/Cntr=0.3,0.1

Type RM Length L Ch R = 1 ,55004.98,226.044600,226.044600,226.044600
XS GIS Cut Line= 6
692990.082016094785807.776211214 692930.81242991785747.260162004
692907.441137991785728.223538215692885.682989572785714.520383211
692851.045245677785685.660695285692725.346060991 785613.24703455
#Sta/Elev= 30
9782.289 2074.919789.8412072.3959804.7022066.4659813.0792062.3739819.5632059.692
9833.5272057.6829841.4172057.1219861.2412054.9499886.4572055.4889897.1872053.203
9903.236 2052.84 9911.892051.139    99222048.0989936.8052047.2659949.8222044.882
9962.8382044.2029974.9622041.9689986.5032042.1259998.0432039.25510009.58 2041.28
10021.122050.67810032.672057.80510044.212065.64510049.442067.33110055.752068.479
10067.292069.10410078.832074.52610090.372079.59710101.912081.80610113.052082.602
#Mann= 3 , 0 , 0
9782.289  0.0516       09782.289  0.0516       010113.05  0.0516       0
#XS Ineff= 2 , 0
       0                               0
Bank Sta=9782.289,10113.05
Exp/Cntr=0.3,0.1

Type RM Length L Ch R = 1 ,54778.93,148.264300,148.264300,148.264300
XS GIS Cut Line= 6
693148.927134945785697.347676564693102.867623807785641.082512533
693065.038455979 785611.37483472692953.618644468785574.486424076
692916.888472192 785554.12691773692835.057534376785465.530907227
#Sta/Elev= 30
9799.0882069.2269802.0082067.8749814.4492064.375 9826.892062.7349838.5232059.659
9853.2662057.4729871.8722058.0319882.4442057.871 9896.282059.8899907.9052059.835
9913.7332059.3829920.103 2056.989931.3712048.891  9942.52046.9099953.2382045.777
9963.7792045.3999974.1312043.7689994.835 2034.8810005.19    203410015.582039.011
10025.982042.65810035.93 2042.3510058.392043.27410082.382046.37810109.262048.082
10122.972050.61210137.382055.55810175.842065.285 10188.72067.07310200.88 2067.66
#Mann= 3 , 0 , 0
9799.088    0.04       09799.088    0.04       010200.88    0.04       0
#XS Ineff= 2 , 0
       0                               0
Bank Sta=9799.088,10200.88
Exp/Cntr=0.3,0.1

Type RM Length L Ch R = 1 ,54630.67,148.264200,148.264200,148.264200
XS GIS Cut Line= 6
693142.482952595785628.694616968 693078.99688093 785525.65899998
693054.989775105785483.501554756693042.470751297785455.758335021
  693041.4576532785454.033912728 693007.17276503785374.575278678
#Sta/Elev= 30
9799.0252069.0849803.3652068.2649815.111 2066.469826.8562063.3149838.6022061.324
9850.3482059.8049862.0942058.909 9873.84 2057.849885.586 2056.279889.5422052.915
9897.3322043.8559908.6052037.7039909.0772037.5889920.8082038.4599943.8232039.242
9955.3312039.1639966.8392038.3889968.5632038.199 9977.892036.5439988.8612031.632
 9999.882028.85610010.84 2029.6110021.73 2034.9110032.622037.12210042.542037.072
10043.512037.174 10054.42040.43710065.292042.28110076.19 2043.2110087.542043.937
#Mann= 3 , 0 , 0
9799.025    0.04       09799.025    0.04       010087.54    0.04       0
#XS Ineff= 2 , 0
       0                               0
Bank Sta=9799.025,10087.54
Exp/Cntr=0.3,0.1

Type RM Length L Ch R = 1 ,54482.41,148.264200,148.264200,148.264200
XS GIS Cut Line= 6
693219.230994188 785675.75230535693193.784086421 785607.56946928
693182.704103262785553.379921294693181.738790699785471.617942496
693187.707590411785370.999749631693179.984258312785280.257417564
#Sta/Elev= 30
9799.0632077.292 9810.542073.4259821.2142072.7259831.8872071.1619874.4872071.077
9884.7922067.7649895.0962063.5279905.3632056.732 9915.472048.0039925.5782038.502
9935.6072035.0199965.634 2034.839985.6352025.1119995.6352023.66810005.642024.346
10025.692031.05310035.722032.65210045.762035.85510065.832045.25510075.852050.666
10085.852056.63810095.852060.78910115.862066.70310125.882073.97810135.892078.454
10155.942090.838   101662094.59510176.072096.43810196.192097.47110200.972097.306
#Mann= 3 , 0 , 0
9799.063    0.04       09799.063    0.04       010200.97    0.04       0
#XS Ineff= 2 , 0
       0                               0
Bank Sta=9799.063,10200.97
Exp/Cntr=0.3,0.1

Type RM Length L Ch R = 1 ,54334.14,148.264300,148.264300,148.264300
XS GIS Cut Line= 6
693388.454246967785640.855543488693372.822908085 785569.75135466
693356.266507681785516.923413512693304.704714296785419.183419444
693288.826806628 785380.56863113693259.675761547 785262.83626905
#Sta/Elev= 30
9799.0672046.3289856.2562037.3679887.328  2031.99908.2872029.4539918.7672029.251
9940.3462029.7499951.3452029.7049962.3452030.2879973.7312030.043 9976.172028.744
9985.2742023.1549996.8162020.026   100012020.36710008.312021.72910019.742026.319
10031.182032.25210042.352033.73410063.982043.13410074.792047.10510085.382051.458
10095.782056.08610106.182060.05810116.592067.96610126.992068.43810137.352070.807
10147.582078.73910157.81 2083.4310175.682091.15310188.492097.34710200.942102.469
#Mann= 3 , 0 , 0
9799.067    0.04       09799.067    0.04       010200.94    0.04       0
#XS Ineff= 2 , 0
       0                               0
Bank Sta=9799.067,10200.94
Exp/Cntr=0.3,0.1