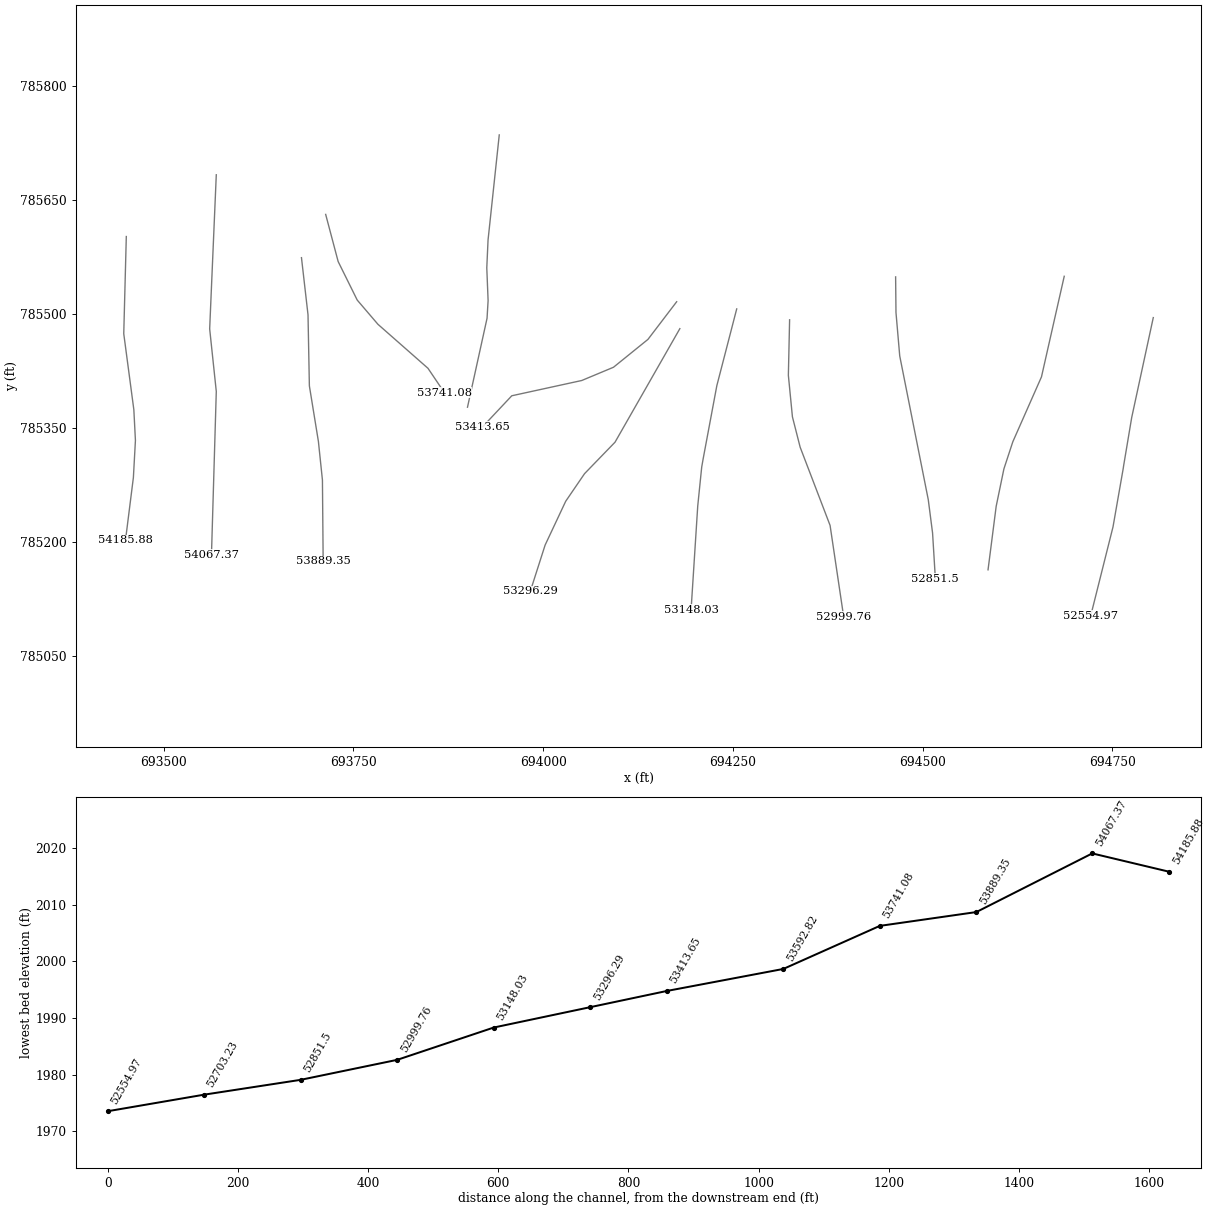
HEC-RAS study 14536_ras.prj: 14536

--- 14536_ras.g01 (geometry) --- (continued)

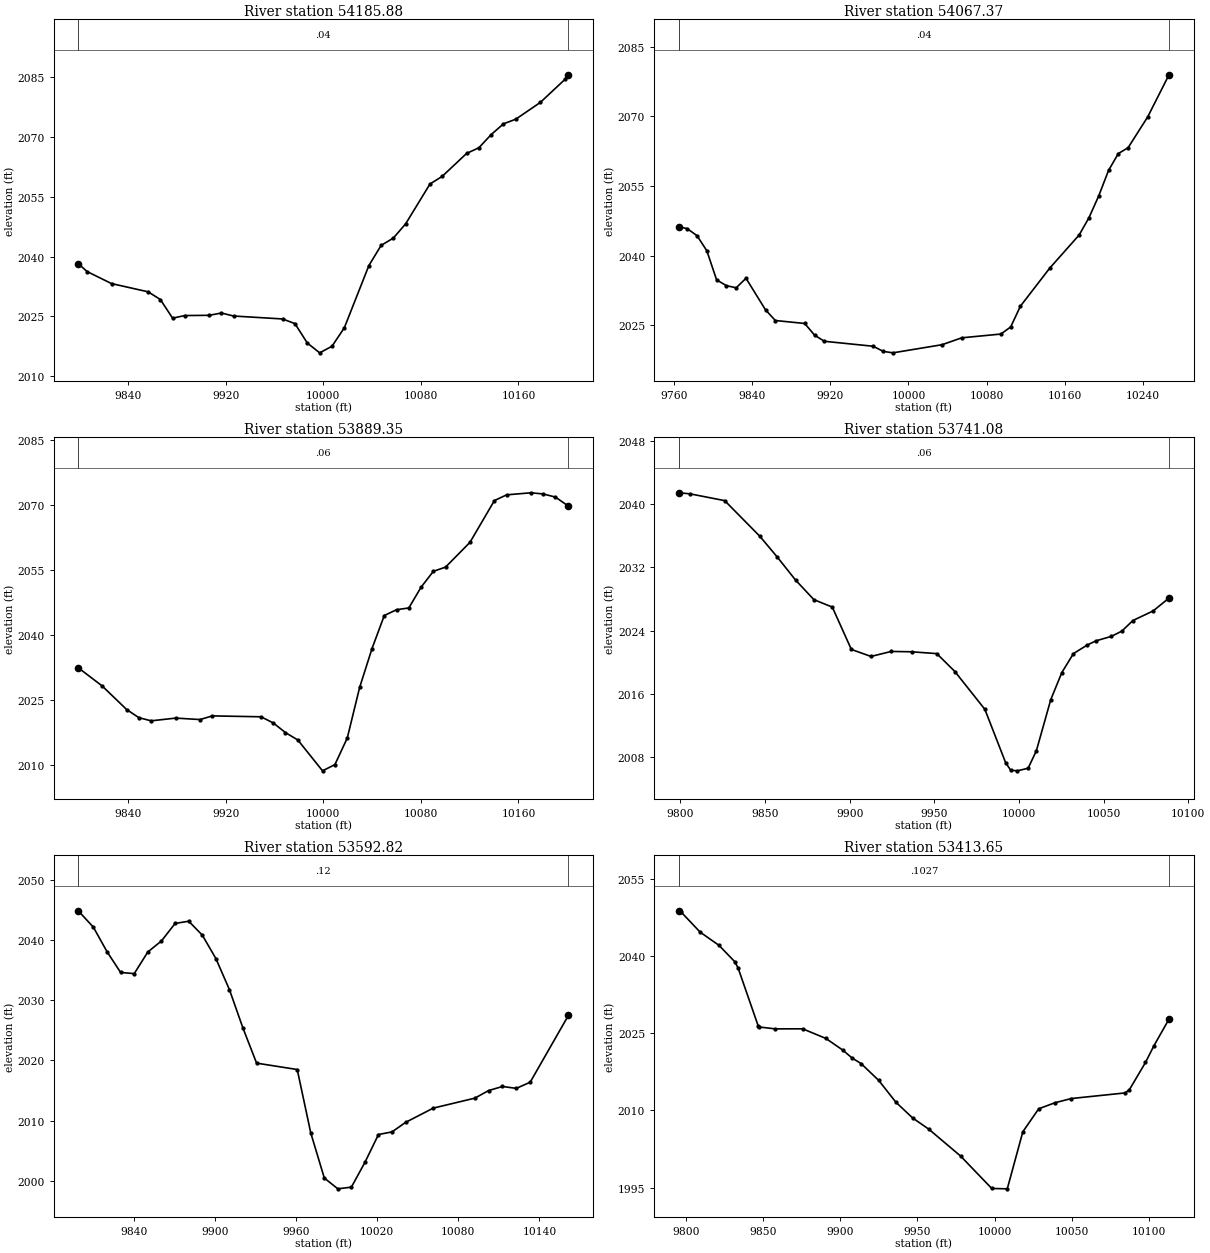
Type RM Length L Ch R = 1 ,54185.88,118.507000,118.507000,118.507000
XS GIS Cut Line= 6
 693450.80913776785602.254360685693447.437883228785474.179432409
693460.737986267785374.005402411 693462.82644654785333.560551801
693460.139770855 785284.81407976693449.739340319785202.167732719
#Sta/Elev= 30
9799.0352038.218  9806.32036.2269826.3282033.205 9856.372031.1359866.3842029.201
9876.3952024.5269886.3962025.1829906.397 2025.249916.3982025.8199926.3982025.066
9966.5652024.3269976.7042023.1619986.8422018.294 9996.982015.824 10007.12017.478
10017.212022.11510037.352037.73710047.362042.78110057.372044.62610067.392048.159
10087.422058.19410097.432060.11210117.462065.86710127.542067.29310137.622070.601
 10147.72073.29810157.78 2074.4610177.942078.67810198.092084.44510200.952085.608
#Mann= 3 , 0 , 0
9799.035    0.04       09799.035    0.04       010200.95    0.04       0
#XS Ineff= 2 , 0
       0                               0
Bank Sta=9799.035,10200.95
Exp/Cntr=0.3,0.1

Type RM Length L Ch R = 1 ,54067.37,178.021400,178.021400,178.021400
XS GIS Cut Line= 4
693569.363154233785683.606474802693560.639883071785480.592163742
693569.363154233 785398.11759986693563.018957049785183.207918987
#Sta/Elev= 30
9765.2772046.2279773.8912045.817  9783.9  2044.3 9793.912041.0539803.9192034.782
9813.9282033.5419823.9372033.0789833.9472035.1299853.9652028.3149863.9742026.033
9894.0022025.3959904.0112022.891 9914.022021.5629964.0662020.4889974.1022019.394
9984.1582019.07110034.442020.82310054.532022.30710094.552023.11810104.552024.647
10114.562029.13910144.572037.33810174.58 2044.4610184.592048.17410194.592052.881
 10204.62058.358 10214.62061.98510224.612063.25310244.612069.87810266.422078.956
#Mann= 3 , 0 , 0
9765.277    0.04       09765.277    0.04       010266.42    0.04       0
#XS Ineff= 2 , 0
       0                               0
Bank Sta=9765.277,10266.42
Exp/Cntr=0.3,0.1

Type RM Length L Ch R = 1 ,53889.35,148.264300,148.264300,148.264300
XS GIS Cut Line= 6
693681.598788536785574.413226753693690.219341136785499.075057135
693692.017321561785405.431142305693703.900304557785332.333462509
693709.217587438785281.371092064693710.184871565785174.322759495
#Sta/Elev= 30
9799.076 2032.469818.6162028.2859838.7462022.8419848.8112020.9549858.8772020.234
9878.9812020.8619898.9852020.5279908.9872021.3729948.9942021.1619958.9962019.739
9969.0032017.514 9979.122015.818 9999.36 2008.7110009.522010.14810019.65 2016.27
10029.79 2027.9310039.932036.878   100502044.49710060.062045.83110070.11 2046.24
10080.172051.02810090.222054.67410100.242055.64910120.26 2061.3610140.272070.974
10150.282072.29710170.282072.77410180.292072.50110190.292071.78210200.972069.694
#Mann= 3 , 0 , 0
9799.076    0.06       09799.076    0.06       010200.97    0.06       0
#XS Ineff= 2 , 0
       0                               0
Bank Sta=9799.076,10200.97
Exp/Cntr=0.3,0.1

Type RM Length L Ch R = 1 ,53741.08,148.264200,148.264200,148.264200
XS GIS Cut Line= 6
693713.492464176785631.380474234693729.931043354 785569.28632034
693755.054661468 785518.51819747693782.349322024785486.607605213
693848.306619006 785428.60737868693869.815278531785396.686468438
#Sta/Elev= 30
9799.075 2041.429805.6262041.2889826.1632040.4289846.8732035.9369857.3612033.263
9868.0112030.3929878.8772027.9099889.7432026.9689900.9972021.6169912.5962020.731
9924.5352021.362 9936.54 2021.329951.4692021.0889962.166 2018.829979.8662014.046
9992.1692007.2839995.1152006.353    9999 2006.2710005.422006.59810010.292008.805
 10018.82015.27210025.342018.69210032.192021.09110040.382022.17810045.572022.708
10054.592023.26810060.832023.937 10067.3 2025.2710079.252026.48110088.652028.109
#Mann= 3 , 0 , 0
9799.075    0.06       09799.075    0.06       010088.65    0.06       0
#XS Ineff= 2 , 0
       0                               0
Bank Sta=9799.075,10088.65
Exp/Cntr=0.3,0.1

Type RM Length L Ch R = 1 ,53592.82,179.166900,179.166900,179.166900
XS GIS Cut Line= 6
 693942.19654907785736.116940027693927.436715713785597.711513827
693925.766072776785560.905105205693927.502016917785517.832501068
693926.118104521 785494.55044833693900.345861576785377.365731882
#Sta/Elev= 30
 9799.022044.8829810.2172042.1549820.2882038.084 9830.362034.6319840.4312034.435
9850.5032038.0449860.5752039.8719870.6462042.7749880.7112043.1479890.7512040.834
 9900.792036.945 9910.832031.7669920.8692025.3539930.9092019.5559960.9612018.494
9970.9712007.9459980.9782000.4559990.983 1998.66   100011998.94310011.01 2003.06
10021.02 2007.6910031.042008.12410041.052009.70310061.522012.07910092.242013.731
10102.482014.99910112.722015.67510122.96 2015.36 10133.22016.38210161.492027.493
#Mann= 3 , 0 , 0
 9799.02    0.12       0 9799.02    0.12       010161.49    0.12       0
#XS Ineff= 2 , 0
       0                               0
Bank Sta=9799.02,10161.49
Exp/Cntr=0.3,0.1

Type RM Length L Ch R = 1 ,53413.65,117.361600,117.361600,117.361600
XS GIS Cut Line= 6
694175.957599944785516.331830355694138.110987087785466.706141287
694092.741559079785430.019577145694050.919114364785412.554045259
693958.710384904785392.428246236693920.609627886785351.915702224
#Sta/Elev= 30
9795.3212048.7779796.9942048.4779809.1412044.6289821.3372042.0729831.483 2038.92
9833.6982037.7169846.8772026.3379847.2312026.2129857.8082025.837 9875.612025.849
 9890.662023.9829901.4582021.7519907.4722020.2269913.5682019.0779924.925 2015.83
9936.064 2011.599946.8852008.5419957.4252006.3489977.9932001.1389998.1941994.841
10008.281994.76510018.372005.85510028.64 2010.3110038.962011.46410049.732012.305
10084.762013.39810087.49 2014.0410097.89 2019.3110103.292022.52110113.142027.732
#Mann= 3 , 0 , 0
9795.321  0.1027       09795.321  0.1027       010113.14  0.1027       0
#XS Ineff= 2 , 0
       0                               0
Bank Sta=9795.321,10113.14
Exp/Cntr=0.3,0.1

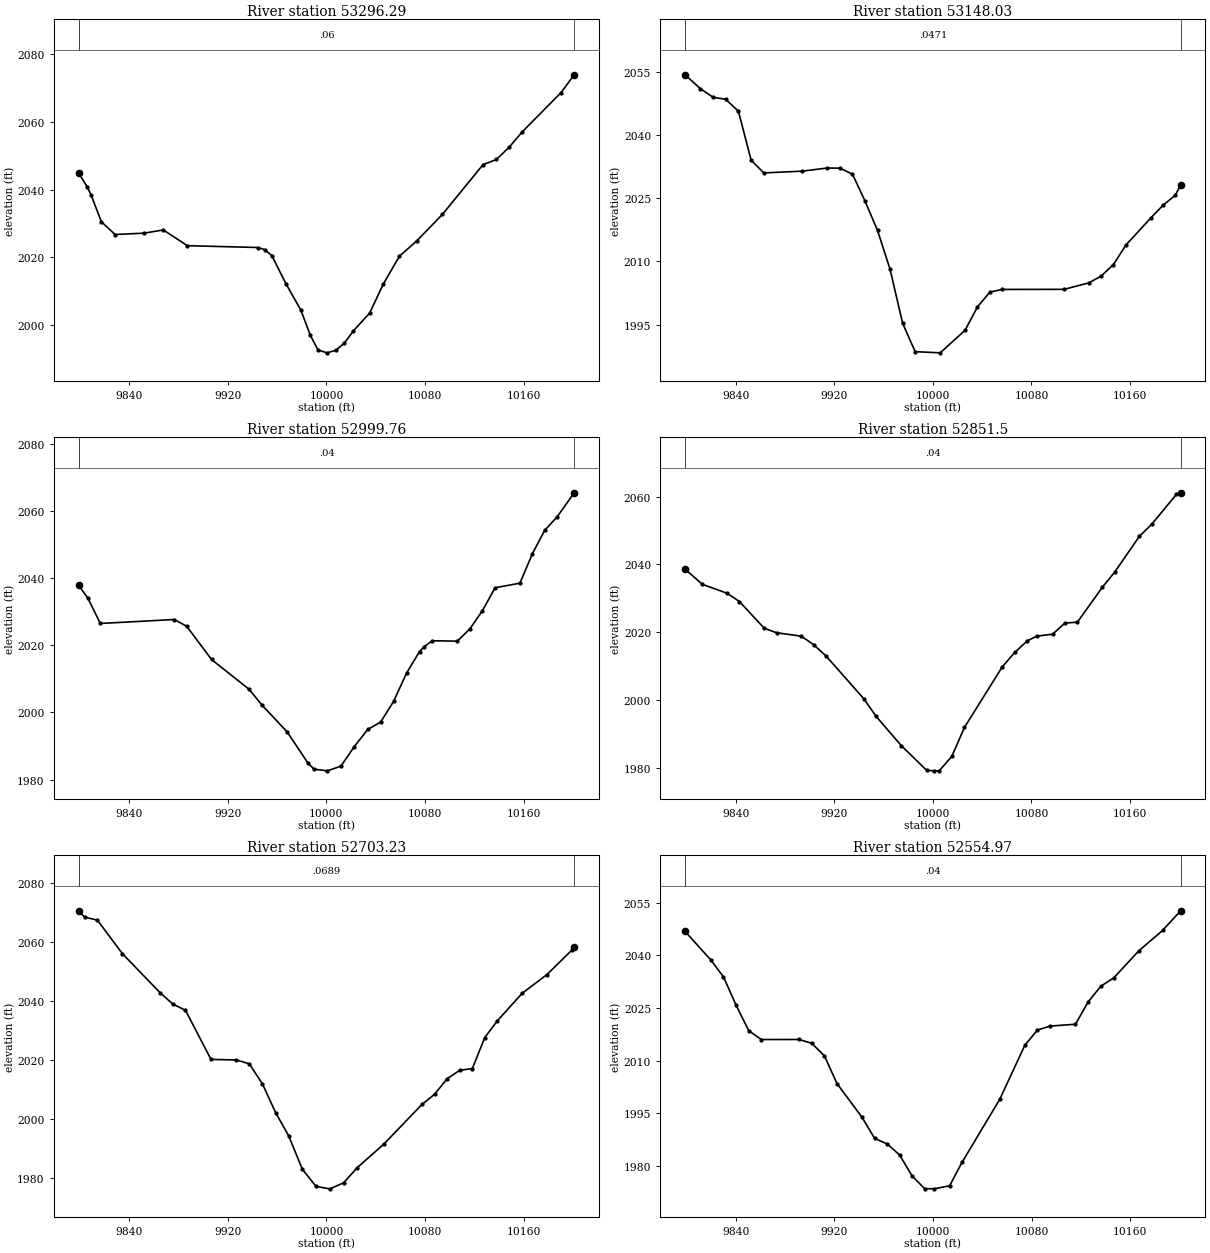
Type RM Length L Ch R = 1 ,53296.29,148.264200,148.264200,148.264200
XS GIS Cut Line= 6
694180.151457506785480.861098694694094.740976886785331.273179868
694054.593447748785289.811743447694029.736328205785253.407013258
694002.621785831785195.697109406693983.145404593785134.937767555
#Sta/Elev= 30
9799.055 2044.839805.8792040.8789809.1152038.4239817.521 2030.499828.6432026.757
9852.4482027.1659867.6982028.1099887.2262023.4659944.3742022.9319949.7762022.331
9955.7422020.539 9967.112012.2779979.3572004.4219986.8651997.1159993.1081992.768
10000.471991.91110007.551992.64610014.54 1994.7710021.781998.34910034.99  2003.6
10046.18 2012.2310059.212020.37910073.252024.88810093.992032.66810126.952047.324
10137.792048.85210148.292052.51410158.792057.00310190.292068.57210200.862073.796
#Mann= 3 , 0 , 0
9799.055    0.06       09799.055    0.06       010200.86    0.06       0
#XS Ineff= 2 , 0
       0                               0
Bank Sta=9799.055,10200.86
Exp/Cntr=0.3,0.1

Type RM Length L Ch R = 1 ,53148.03,148.264200,148.264200,148.264200
XS GIS Cut Line= 6
694255.072606543785506.873784894694228.885716605785405.788257692
694210.953520359785309.898940227694208.931152943785298.336207759
694203.710034002785247.104740199694194.966271881785110.633008967
#Sta/Elev= 30
9799.026 2054.339811.2922051.0559821.6222049.0089831.9522048.5059842.2822045.676
9852.6122034.0199862.9422031.0339893.9322031.4459914.4232032.1969924.5962032.153
9934.7692030.7459944.9432024.3729955.1162017.3669965.2892008.1489975.4621995.341
9985.6351988.59410005.971988.31110026.14 1993.68 10036.21999.23210046.252002.728
 10056.32003.36810106.432003.38510126.472004.91810136.492006.53610146.512009.282
10156.532013.87710176.572020.27910186.592023.31310196.612025.70610200.992028.112
#Mann= 3 , 0 , 0
9799.026  0.0471       09799.026  0.0471       010200.99  0.0471       0
#XS Ineff= 2 , 0
       0                               0
Bank Sta=9799.026,10200.99
Exp/Cntr=0.3,0.1

Type RM Length L Ch R = 1 ,52999.76,148.264300,148.264300,148.264300
XS GIS Cut Line= 6
694324.762825787785492.531066508694323.129661095785419.391701524
694328.480280792785364.682099851694338.665590877785324.659975518
694378.086819424785221.630507438694396.003383133 785101.21761095
#Sta/Elev= 30
9799.1192037.8719806.6612034.0399816.6752026.5219876.7192027.7019886.7672025.672
9906.8622015.7939937.2682006.9169947.5862002.2839968.2241994.194 9984.91    1985
9989.9041983.10710000.851982.60410011.781984.005 10022.7 1989.8510033.521994.934
10044.011997.14510054.512003.301   100652011.734 10075.5 2018.1310079.042019.505
 10085.82021.36910106.192021.24610116.382024.93710126.582030.35110136.77 2037.17
10156.912038.52210166.962047.24910177.012054.27110187.062058.27510200.912065.466
#Mann= 3 , 0 , 0
9799.119    0.04       09799.119    0.04       010200.91    0.04       0
#XS Ineff= 2 , 0
       0                               0
Bank Sta=9799.119,10200.91
Exp/Cntr=0.3,0.1

Type RM Length L Ch R = 1 , 52851.5,148.264200,148.264200,148.264200
XS GIS Cut Line= 6
694464.448841646785549.068642198694464.922595914785502.082897463
694469.877476777785444.821135031 694507.46851303785255.519237436
694513.140490314785211.540961506694516.798804626785151.573111301
#Sta/Elev= 30
9799.0362038.5619813.105  2034.19833.1062031.4749843.1072029.0349863.1712021.159
9873.2082019.8239893.2832018.805 9903.322016.2989913.4582012.9279943.8762000.393
9954.0151995.1189974.4661986.492 9994.921979.225   100011979.073 10005.21979.109
10015.411983.35610025.621991.88310056.242009.72710066.452014.02510076.662017.447
10084.262018.81610097.072019.39210107.152022.68310117.232022.933 10137.42033.209
10147.442037.69310167.482048.256 10177.52051.82210197.53 2060.6410200.972061.118
#Mann= 3 , 0 , 0
9799.036    0.04       09799.036    0.04       010200.97    0.04       0
#XS Ineff= 2 , 0
       0                               0
Bank Sta=9799.036,10200.97
Exp/Cntr=0.3,0.1

Type RM Length L Ch R = 1 ,52703.23,148.264200,148.264200,148.264200
XS GIS Cut Line= 6
694686.613340051785549.871038192694656.624859527 785417.31472444
 694618.84351971785331.756786844 694607.12132845785296.072372824
694596.947534205785246.815596913694586.217697058785163.093230734
#Sta/Elev= 30
9799.0492070.5169804.0142068.3379814.2092067.3669834.5992055.9849865.1832042.771
9875.3782038.9829885.716 2036.849906.3932020.2439927.0712020.0449937.486 2018.74
9948.1552011.9219958.8242002.2199969.4921994.309 9980.451983.0979991.6171977.259
 10002.81976.45310013.931978.48210025.061983.653 10046.31991.47910077.532005.017
10087.742008.46110097.952013.71610108.172016.54810118.352017.15510128.442027.634
10138.522033.23910158.682042.57210178.842048.93410199.012057.20210200.932058.329
#Mann= 3 , 0 , 0
9799.049  0.0689       09799.049  0.0689       010200.93  0.0689       0
#XS Ineff= 2 , 0
       0                               0
Bank Sta=9799.049,10200.93
Exp/Cntr=0.3,0.1

Type RM Length L Ch R = 1 ,52554.97,148.264300,148.264300,148.264300
XS GIS Cut Line= 6
694803.947520803785495.443624801694775.494993105785363.706410375
694764.723787233785299.388236187694764.468743748785297.404564636
 694750.87084748785219.624646998694721.426335041785102.257112817
#Sta/Elev= 30
9799.0112046.8389819.9262038.6919830.1572033.8769840.3882025.8219850.6182018.581
9860.8492016.046 9891.542016.0669901.7712014.9689912.0022011.4129922.2322003.504
9942.6141993.8599952.7531987.8949962.8921986.3239973.0321983.1639983.1711977.179
 9993.311973.588   100011973.52510013.591974.39610023.741981.147 10054.2    1999
 10074.52014.35510084.732018.73410095.042019.88610115.662020.39910125.97 2026.79
10136.282031.25410146.592033.57210167.21 2041.3710186.282047.10910200.962052.721
#Mann= 3 , 0 , 0
9799.011    0.04       09799.011    0.04       010200.96    0.04       0
#XS Ineff= 2 , 0
       0                               0
Bank Sta=9799.011,10200.96
Exp/Cntr=0.3,0.1