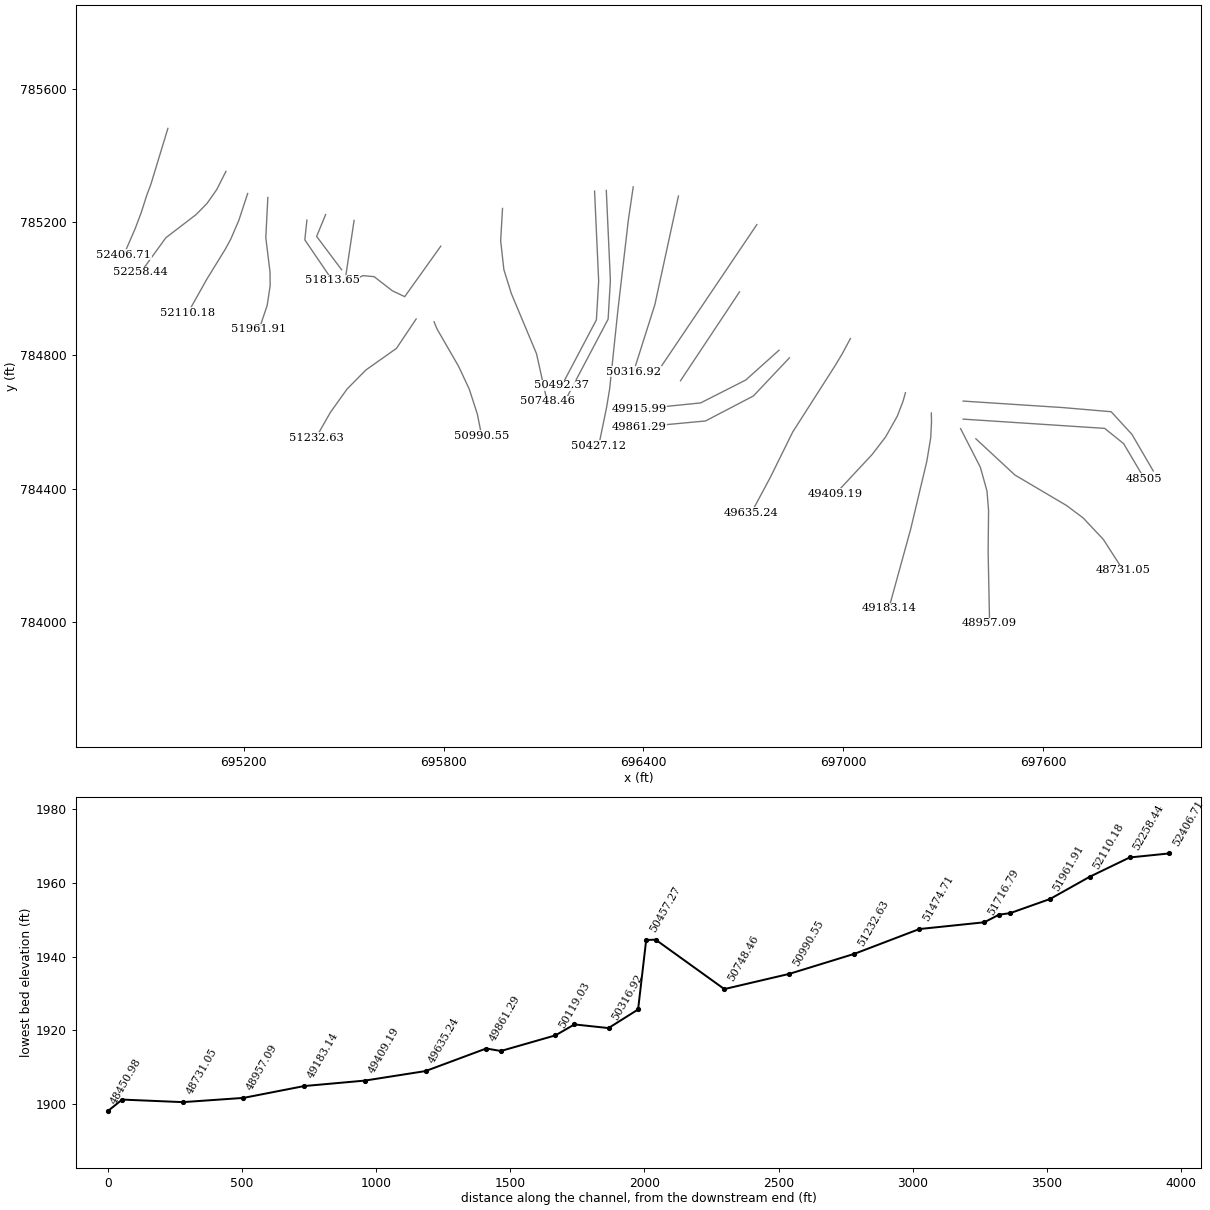
HEC-RAS study 14536_ras.prj: 14536

--- 14536_ras.g01 (geometry) --- (continued)

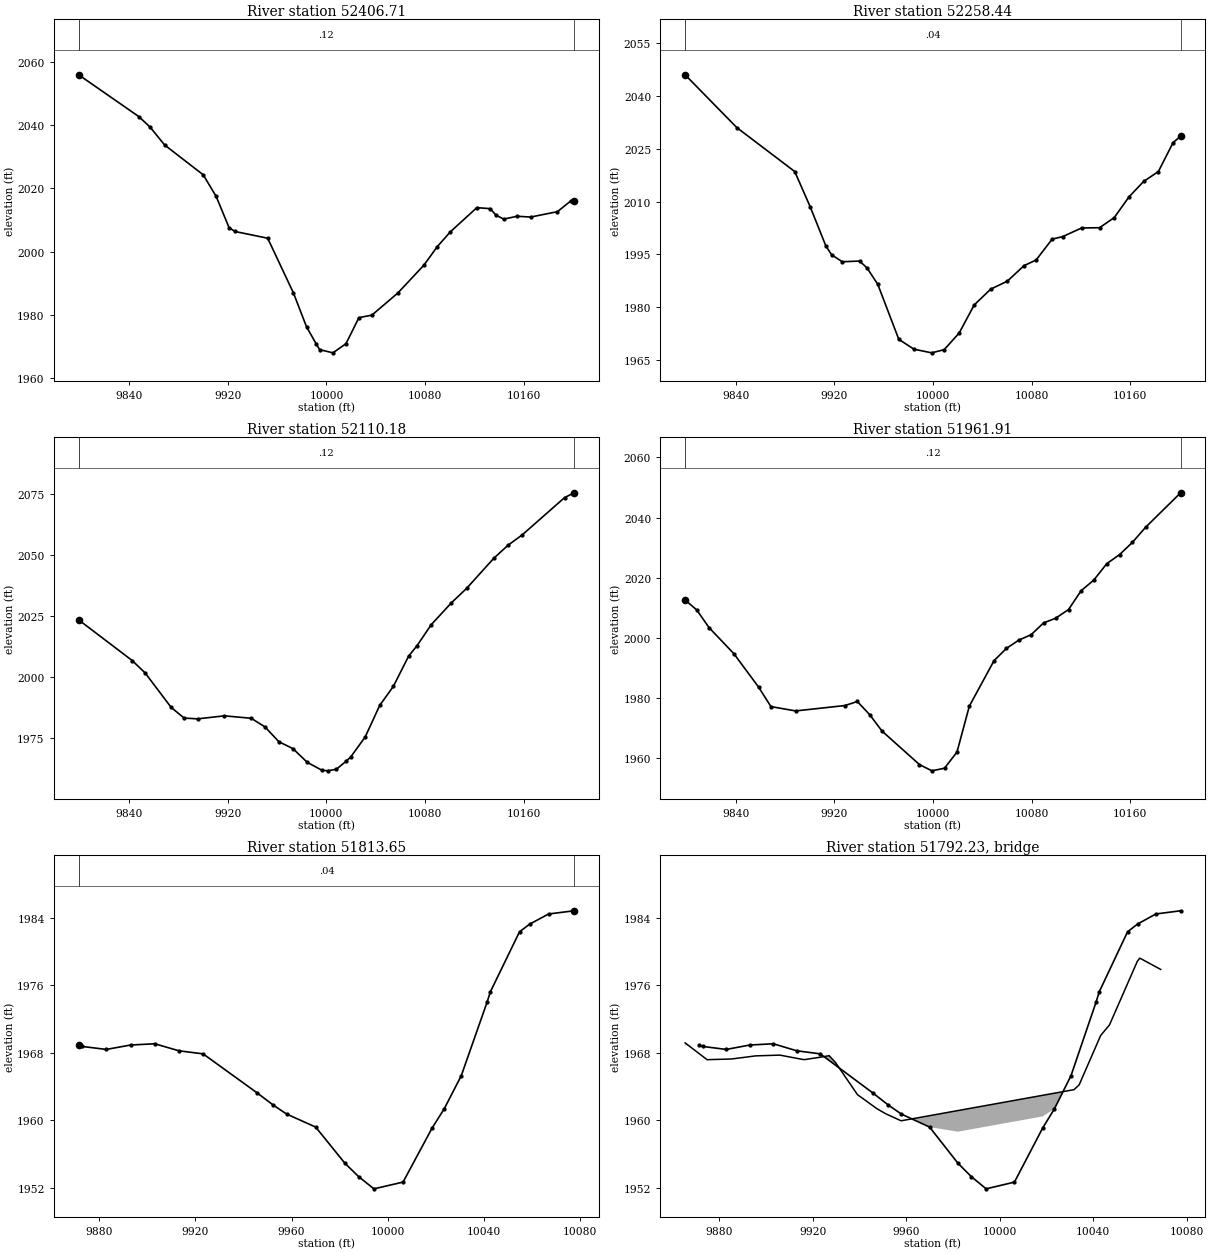
Type RM Length L Ch R = 1 ,52406.71,148.264200,148.264200,148.264200
XS GIS Cut Line= 6
694971.866284883785481.712112777694920.781236941785313.785674587
694909.081858824785282.875956586694891.139410044785227.049206394
694873.299714489785179.963519443694839.705769078785102.570078643
#Sta/Elev= 30
9799.0242055.925 9847.852042.7149856.9762039.4049868.7552033.7539900.1122024.311
9910.5652017.5039921.0172007.6639925.6942006.4259952.3752004.289 9973.281986.975
9983.8861976.2949991.624 1970.979994.5141969.07610005.331968.07210015.891970.973
 10026.41979.199 10036.91979.98310057.911986.96110079.141995.78910089.842001.582
10100.532006.29410122.022013.94610132.922013.62810137.462011.60610143.832010.318
10154.732011.22510165.632010.97210187.432012.67910198.33  2016.110200.982016.185
#Mann= 3 , 0 , 0
9799.024    0.12       09799.024    0.12       010200.98    0.12       0
#XS Ineff= 2 , 0
       0                               0
Bank Sta=9799.024,10200.98
Exp/Cntr=0.3,0.1

Type RM Length L Ch R = 1 ,52258.44,148.264200,148.264200,148.264200
XS GIS Cut Line= 6
695146.160683209785352.760443961695118.679698951785298.221437155
695088.764556862 785255.62794326695056.266606323785222.791298488
694965.916774477785153.571491376694890.643854232785049.850611599
#Sta/Elev= 30
9799.0642046.0819841.0232031.0479887.9632018.5529900.5042008.5259913.1021997.469
9917.8861994.8519926.5531992.8829940.5751993.0869946.5761991.1279955.2591986.493
 9972.351970.8069984.6411968.007    99991966.96810009.151967.86910021.321972.615
10033.491980.59410046.841985.08610060.291987.34310073.931991.78610083.671993.372
10096.721999.32610105.092000.01610120.672002.50310135.132002.56410147.06 2005.46
10158.982011.326 10170.92015.74710182.822018.53810194.752026.77810200.882028.622
#Mann= 3 , 0 , 0
9799.064    0.04       09799.064    0.04       010200.88    0.04       0
#XS Ineff= 2 , 0
       0                               0
Bank Sta=9799.064,10200.88
Exp/Cntr=0.3,0.1

Type RM Length L Ch R = 1 ,52110.18,148.264300,148.264300,148.264300
XS GIS Cut Line= 6
695211.425984376785286.244019265695185.096484099785206.105162306
 695160.78172399785149.441881593695144.026184617785118.683030142
695089.018209978785029.360552795695032.275877194784928.210368249
#Sta/Elev= 30
9799.0582023.5969842.471 2006.949852.9972001.8559874.0491987.7679884.6141983.367
9895.4961983.0449917.2591984.2779939.0231983.2819950.1291979.7769961.517 1973.66
9972.9041970.8479984.4581965.2429996.2961962.015   100011961.74910008.111962.416
10015.93 1965.6410019.821967.47510031.541975.68210043.25 1988.5510054.321996.342
10066.682008.71410073.522013.009   100852021.58610101.472030.61310113.662036.452
10135.87 2048.8610147.332054.155 10158.82058.387 10193.22073.67310200.982075.649
#Mann= 3 , 0 , 0
9799.058    0.12       09799.058    0.12       010200.98    0.12       0
#XS Ineff= 2 , 0
       0                               0
Bank Sta=9799.058,10200.98
Exp/Cntr=0.3,0.1

Type RM Length L Ch R = 1 ,51961.91,148.264200,148.264200,148.264200
XS GIS Cut Line= 6
695272.076134038785274.386533636695265.880716102785153.621796967
695278.519808366785051.182122798695279.031017339785009.703249633
695270.000539247784949.958438088695245.734283008784878.474807714
#Sta/Elev= 30
9799.0532012.5689808.475 2009.249818.5132003.3389838.5881994.6939858.6641983.557
9868.6681977.0719888.6711975.6329928.6981977.4279938.7251978.7739948.7521974.381
9958.7791968.9139989.1071957.7779999.2481955.69410009.421956.57610019.531961.932
10029.571977.24310049.571992.34210059.571996.425 10069.61999.17410079.652000.991
10089.712004.90610099.492006.47210110.022009.37610120.222015.63510130.532019.188
10140.962024.61910151.392027.65110161.832031.73910172.452036.72710200.912048.228
#Mann= 3 , 0 , 0
9799.053    0.12       09799.053    0.12       010200.91    0.12       0
#XS Ineff= 2 , 0
       0                               0
Bank Sta=9799.053,10200.91
Exp/Cntr=0.3,0.1

Type RM Length L Ch R = 1 ,51813.65,41.964000,41.964000,41.964000
XS GIS Cut Line= 3
695389.344788879785206.437451228695383.094788879785147.062451228
695465.386455536  785026.2291179
#Sta/Elev= 24
9871.5351968.8539872.9811968.7299883.0361968.3739893.0911968.8959903.1471969.046
9913.2021968.2139923.2571967.8499945.8331963.1999952.3881961.7829957.9311960.721
 9970.031959.1739982.1291954.9029987.9191953.2939994.2281951.85710006.331952.655
10018.431959.07610023.451961.34610030.521965.26210041.221973.95510042.621975.208
10054.721982.30810058.981983.22610066.821984.42210077.431984.801
#Mann= 3 , 0 , 0
9871.535    0.04       09871.535    0.04       010077.43    0.04       0
#XS Ineff= 2 , 0
       0                               0
Bank Sta=9871.535,10077.43
Exp/Cntr=0.3,0.1

Type RM Length L Ch R = 3 ,51792.23,,,
BEGIN DESCRIPTION:
END DESCRIPTION:
Bridge Culvert--1,0,-1,-1, 0
Deck Dist Width WeirC Skew NumUp NumDn MinLoCord MaxHiCord MaxSubmerge Is_Ogee
13.482000,15.000000,2.6,0, 26, 26, , , 0.95, 0, 0,0,,
 9865.43 9874.89 9876.18 9885.25 9895.62 9905.98 9914.19 9916.35 9924.81 9927.04
 9929.76 9939.16 9947.45 9951.28 9957.82 9964.88 9964.8810027.8810027.8810031.84
10034.0210043.2010046.9910058.9110059.9510068.92
 1969.15 1967.15 1967.17 1967.24 1967.61 1967.70 1967.27 1967.16 1967.52 1967.64
 1966.83 1963.02 1961.36 1960.75 1959.92 1960.27 1960.27 1963.41 1963.41 1963.61
 1964.18 1970.02 1971.28 1978.82 1979.19 1977.85
  969.15  967.15  967.17  967.24  967.61  967.70  967.27  967.16  967.52  967.64
  966.83  963.02  961.36  960.75  959.92  960.27 1957.77 1960.91  963.41  963.61
  964.18  970.02  971.28  978.82  979.19  977.85
 9865.43 9874.89 9876.18 9885.25 9895.62 9905.98 9914.19 9916.35 9924.81 9927.04
 9929.76 9939.16 9947.45 9951.28 9957.82 9961.30 9961.3010024.3010024.3010031.84
10034.0210043.2010046.9910058.9110059.9510068.92
 1969.15 1967.15 1967.17 1967.24 1967.61 1967.70 1967.27 1967.16 1967.52 1967.64
 1966.83 1963.02 1961.36 1960.75 1959.92 1960.09 1960.09 1963.24 1963.24 1963.61
 1964.18 1970.02 1971.28 1978.82 1979.19 1977.85
  969.15  967.15  967.17  967.24  967.61  967.70  967.27  967.16  967.52  967.64
  966.83  963.02  961.36  960.75  959.92  960.09 1957.59 1960.74  963.24  963.61
  964.18  970.02  971.28  978.82  979.19  977.85
BR Coef=-1 , 0 , 0 ,, 0 ,,,0.8,0,1,0,
WSPro=,,,, 1 ,,,, 0 ,,,, 0 ,,,,-1 ,-1 ,-1 , 0 , 0 , 0 , 0 , 0
BC Design=,, 0 ,, 0 ,,,,,,

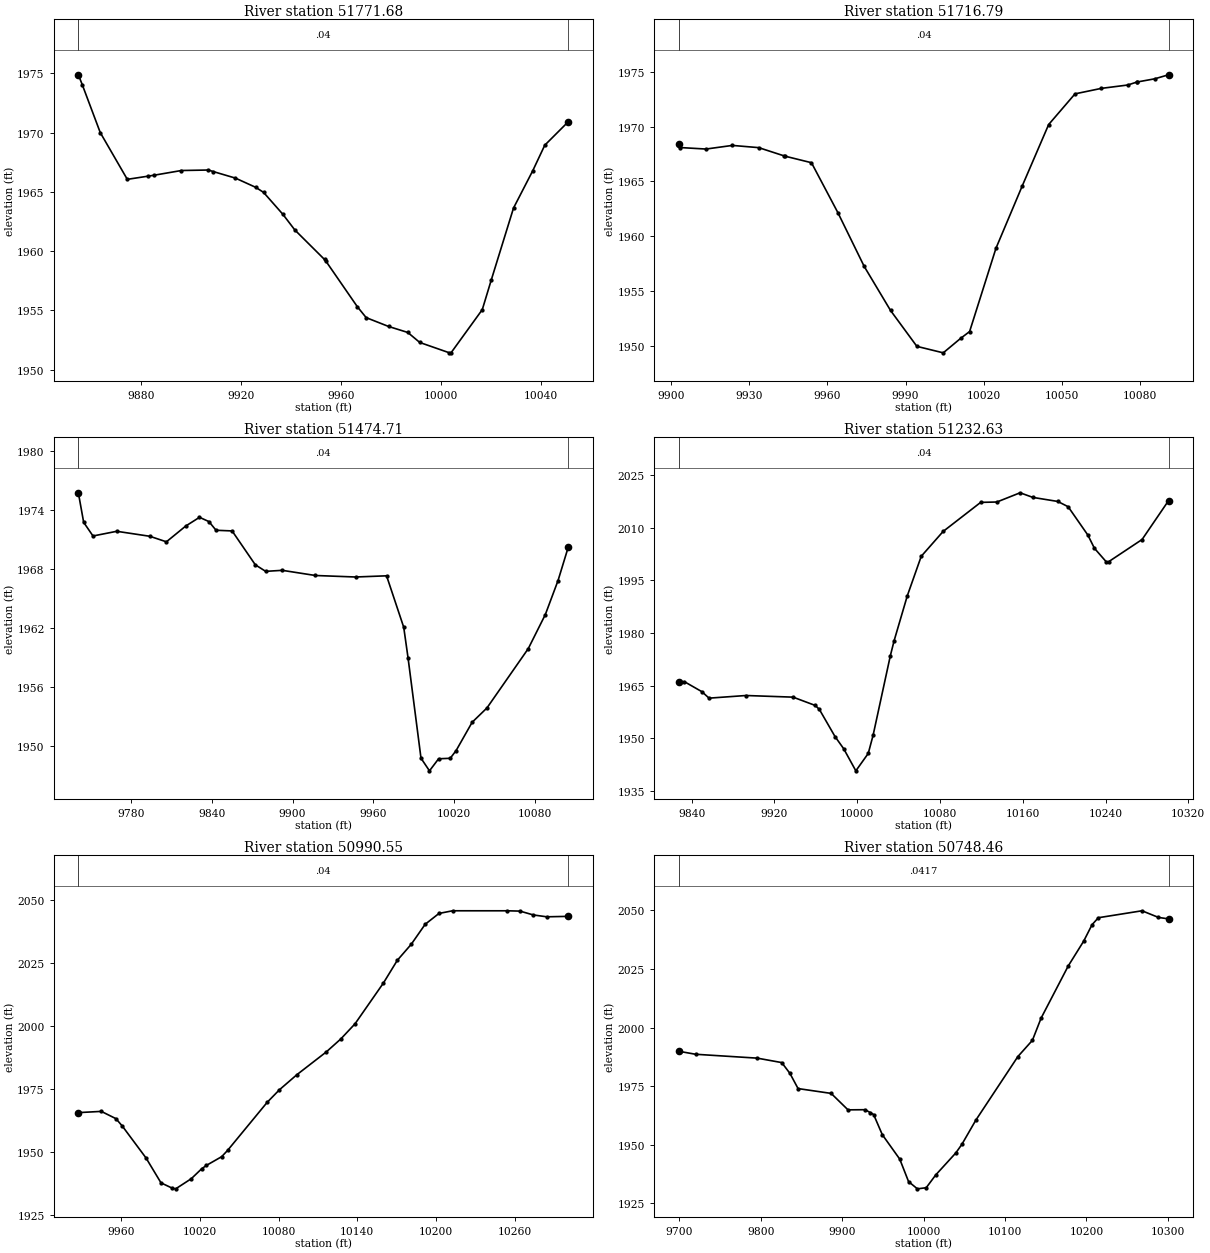
Type RM Length L Ch R = 1 ,51771.68,54.895500,54.895500,54.895500
XS GIS Cut Line= 3
695445.594788879  785223.1041179695418.511455536  785157.4791179
695493.511455536  785057.4791179
#Sta/Elev= 29
9854.8671974.8769856.4261974.0449863.6341969.9999874.4521966.0569882.6391966.321
 9885.271966.4089896.0881966.8019906.9071966.8439908.8521966.7129917.7251966.159
9925.8611965.379 9928.961964.9579936.6751963.111 9941.46 1961.799953.3421959.299
 9953.961959.137 9966.461955.3189970.0081954.393 9978.961953.6499986.6751953.141
 9991.461952.29710003.341951.42310003.961951.42510016.461955.06610020.011957.535
10028.961963.63710036.681966.79510041.461968.93510050.861970.916
#Mann= 3 , 0 , 0
9854.867    0.04       09854.867    0.04       010050.86    0.04       0
#XS Ineff= 2 , 0
       0                               0
Bank Sta=9854.867,10050.86
Exp/Cntr=0.3,0.1

Type RM Length L Ch R = 1 ,51716.79,242.081200,242.081200,242.081200
XS GIS Cut Line= 3
695531.011455536785205.395784542695504.969788879785031.437451199
695501.390228599785019.933640838
#Sta/Elev= 25
9902.9531968.3889903.3531968.0999913.465 1967.969923.5761968.2919933.6881968.088
9943.5571967.3259943.7991967.308 9953.911966.7139964.0221962.1689974.1331957.254
9984.2451953.2319994.3561949.95410004.471949.363 10011.11950.67610014.581951.306
10024.691958.904 10034.8 1964.6110044.911970.19710055.021972.99610065.141973.497
10075.251973.80310078.651974.06610078.851974.07810085.591974.368 10090.91974.737
#Mann= 3 , 0 , 0
9902.953    0.04       09902.953    0.04       0 10090.9    0.04       0
#XS Ineff= 2 , 0
       0                               0
Bank Sta=9902.953,10090.9
Exp/Cntr=0.3,0.1

Type RM Length L Ch R = 1 ,51474.71,242.081200,242.081200,242.081200
XS GIS Cut Line= 6
695791.313131362785128.212137043695683.083356261784976.550453231
695645.876087219784994.252752468695591.209979147785036.575262785
695557.220193267785039.658870786695528.431568593785025.694020331
#Sta/Elev= 30
9740.9481975.7189744.8941972.7219751.8161971.3379769.4641971.8139794.0351971.307
 9806.321970.7469820.6771972.347 9830.89 1973.239837.8921972.7989843.1761971.917
9855.107 1971.859872.3221968.4169880.0311967.7519892.3161967.8569916.8871967.332
9946.7311967.1799969.7731967.2999982.5181962.081 9985.761958.9439995.3351948.808
10001.631947.526 10008.41948.74910017.031948.79810021.391949.578 10033.31952.448
10044.281953.89910074.971959.91610087.64 1963.3710097.091966.82310104.67 1970.21
#Mann= 3 , 0 , 0
9740.948    0.04       09740.948    0.04       010104.67    0.04       0
#XS Ineff= 2 , 0
       0                               0
Bank Sta=9740.948,10104.67
Exp/Cntr=0.3,0.1

Type RM Length L Ch R = 1 ,51232.63,242.081200,242.081200,242.081200
XS GIS Cut Line= 6
695717.407344724 784909.56180564695658.234306888784821.276010976
695566.259683298784756.213018397695510.036288483 784699.29413297
695460.044897679 784629.36067709695416.384243127784552.773947609
#Sta/Elev= 30
9827.4481966.0949833.0241966.1669849.978 1963.319856.8451961.4789892.5761962.231
9938.0751961.763 9959.531959.3959963.4671958.2749978.5751950.5539986.9671947.084
9998.7171940.78910010.711945.74510015.391950.91310032.031973.51910035.731977.853
10048.461990.62110061.912001.85310083.042008.91910119.362017.20310134.992017.304
10157.452019.93310169.812018.61510193.912017.46310203.892015.96210222.952007.895
10229.292004.13610240.812000.24910243.142000.33410275.342006.63310300.92 2017.69
#Mann= 3 , 0 , 0
9827.448    0.04       09827.448    0.04       010300.92    0.04       0
#XS Ineff= 2 , 0
       0                               0
Bank Sta=9827.448,10300.92
Exp/Cntr=0.3,0.1

Type RM Length L Ch R = 1 ,50990.55,242.081200,242.081200,242.081200
XS GIS Cut Line= 6
695771.124874475784901.213652034695779.746374839784880.124973197
695845.277399062784766.469903767695877.061650475784698.282611418
695901.049695192784624.168508236695914.091561516784558.903057398
#Sta/Elev= 30
9927.199 1965.579944.7151966.0599955.8591963.1799960.7171960.2539978.793 1947.62
 9990.261937.723    99991935.58210001.451935.35610013.361939.37410021.241943.295
10024.951944.66810036.54 1948.1110041.041950.589 10071.3 1969.6810080.631974.642
   100941980.63810116.341989.62610127.381994.75310138.26 2000.7710159.932016.947
10170.542025.95810181.162032.30410191.772040.22210202.322044.52910212.722045.581
10254.542045.57710264.13 2045.4510274.332043.92210284.522043.19410300.942043.368
#Mann= 3 , 0 , 0
9927.199    0.04       09927.199    0.04       010300.94    0.04       0
#XS Ineff= 2 , 0
       0                               0
Bank Sta=9927.199,10300.94
Exp/Cntr=0.3,0.1

Type RM Length L Ch R = 1 ,50748.46,256.098200,256.098200,256.098200
XS GIS Cut Line= 6
695976.734892021785241.402399692 695971.10373692785144.749099224
695980.725910586785057.936081728696003.033646678 784986.30467894
 696078.81358741784805.168133151696110.495022821784662.825931358
#Sta/Elev= 30
9699.0681989.9319719.8831988.637 9795.681986.9839825.7421985.0869835.7631980.498
9845.791    19749886.4331971.9399907.1381964.9219928.0361964.9859934.3991963.788
9938.6441962.9079949.2521954.3459970.7161943.8969981.5441934.3129992.3721931.221
10003.221931.69510014.941937.16210039.551946.527   10047 1950.1810064.151960.508
10115.851987.66810133.681994.58610144.372004.06510177.752026.34710196.612036.865
10206.992043.93510214.722046.89410268.292049.85710288.572047.01910300.922046.401
#Mann= 3 , 0 , 0
9699.068  0.0417       09699.068  0.0417       010300.92  0.0417       0
#XS Ineff= 2 , 0
       0                               0
Bank Sta=9699.068,10300.92
Exp/Cntr=0.3,0.1

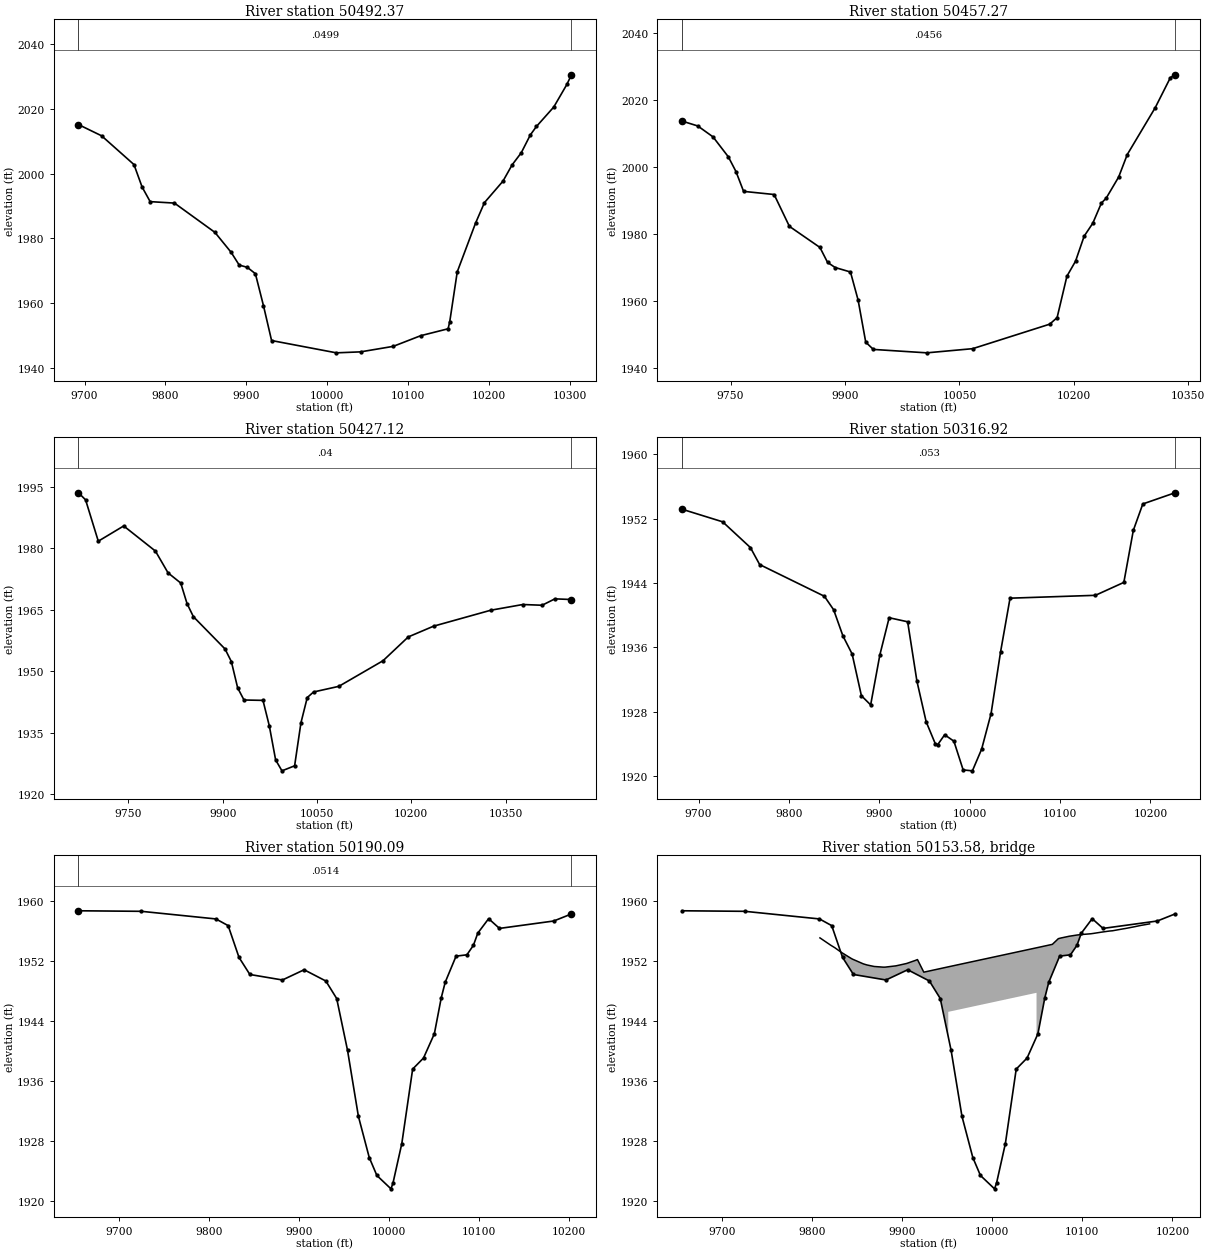
Type RM Length L Ch R = 1 ,50492.37,35.093700,35.093700,35.093700
XS GIS Cut Line= 4
696253.121005606785293.533890851696265.417664956785023.007384636
696258.586187523784906.872268327696154.831099073784710.129128893
#Sta/Elev= 30
9692.4862015.2149721.0492011.744 9761.092002.8489771.1011995.9349781.1111991.391
9811.1421990.9419861.1941981.8889881.2141975.7319891.2251971.7789901.2351971.084
9911.2451969.1079921.2561959.2069931.2661948.44910011.381944.64510041.431944.949
10081.741946.65110115.661949.94510149.581952.08510151.631954.33210160.881969.692
10183.491984.736 10194.51991.08110217.411997.72310228.712002.74810240.022006.495
10251.322012.04110258.822014.62910280.252020.64310296.552027.66810302.05 2030.61
#Mann= 3 , 0 , 0
9692.486  0.0499       09692.486  0.0499       010302.05  0.0499       0
#XS Ineff= 2 , 0
       09951.825         10044.3       0
Bank Sta=9692.486,10302.05
Exp/Cntr=0.3,0.1

Type RM Length L Ch R = 1 ,50457.27,30.153900,30.153900,30.153900
XS GIS Cut Line= 4
696288.337089843785295.585006918696300.633749193785025.058500702
 696293.80227176784908.923384394696172.908935426784679.682246612
#Sta/Elev= 30
9686.3392013.7589706.9452012.3019726.9652009.0359746.9862003.0959756.9961998.704
9767.0071992.7699807.0481991.8349827.0691982.326 9867.111976.029 9877.121971.564
9887.1311970.0289907.1511968.6969917.1621960.3289927.1721947.7449937.1821945.576
10007.291944.55610067.39  1945.810168.361953.113 10178.11955.06610190.97 1967.44
10202.27 1971.9210213.581979.39710224.891983.25610236.191989.28210242.411990.727
 10258.81997.04910270.112003.77410306.732017.75110326.632026.73210332.652027.586
#Mann= 3 , 0 , 0
9686.339  0.0456       09686.339  0.0456       010332.65  0.0456       0
#XS Ineff= 2 , 0
       09953.307        10040.53       0
Bank Sta=9686.339,10332.65
Exp/Cntr=0.3,0.1

Type RM Length L Ch R = 1 ,50427.12,110.202500,110.202500,110.202500
XS GIS Cut Line= 6
696369.191495582785306.156900941696354.528653068785206.519259873
696322.944531171784933.888823921696298.403983174784699.410237235
696288.987884261784642.936562352696265.605718692784529.274637827
#Sta/Elev= 30
9670.5841993.4779681.8611991.7539702.0771981.6739742.5071985.3899792.9591979.265
9813.0941973.9459833.2281971.4749843.2961966.4559853.3631963.273  9903.71955.401
9913.7671952.3369923.8341945.9059933.9021942.9539964.1041942.8649974.1711936.659
9984.2381928.3429994.3061925.68310014.441926.908 10024.51937.38310034.571943.557
10044.631944.91110084.811946.28410155.12 1952.53 10195.31958.33410235.561960.954
10326.561964.84210377.521966.23510408.211966.05510428.571967.61410454.841967.455
#Mann= 3 , 0 , 0
9670.584    0.04       09670.584    0.04       010454.84    0.04       0
#XS Ineff= 2 , 0
       0                10038.03       0
Bank Sta=9670.584,10454.84
Exp/Cntr=0.3,0.1

Type RM Length L Ch R = 1 ,50316.92,126.828500,126.828500,126.828500
XS GIS Cut Line= 3
696504.991826267  785278.8716311696434.158492951 784952.48274223
696370.269604085784751.093853379
#Sta/Elev= 30
9681.8091953.1539726.7021951.5889757.401 1948.399767.6331946.2769839.2631942.333
9849.4961940.6549859.7281937.4169869.9611935.1519880.1941929.9719890.4271928.828
 9900.661935.0719910.8921939.6669931.3581939.1629941.5911931.7969951.8241926.738
9962.0561923.9699964.6771923.8989972.2891925.1159982.522 1924.329992.7551920.746
10002.991920.63310013.221923.33410023.651927.75410034.141935.41110044.631942.096
10139.051942.45110170.521944.05710181.011950.526 10191.51953.80810227.081955.198
#Mann= 3 , 0 , 0
9681.809   0.053       09681.809   0.053       010227.08   0.053       0
#XS Ineff= 2 , 0
       09924.517                       0
Bank Sta=9681.809,10227.08
Exp/Cntr=0.3,0.1

Type RM Length L Ch R = 1 ,50190.09,71.060900,71.060900,71.060900
XS GIS Cut Line= 2
696740.386455566785192.895784542696434.136455536784738.729117885
#Sta/Elev= 30
9655.1331958.6959724.9621958.623 9807.861957.607 9821.451956.7149833.5111952.477
9845.5721950.2019881.7561949.4689905.8781950.831    99301949.3329942.0611946.997
9954.1221940.0869966.1831931.2959978.2441925.7989986.7251923.40510002.371921.622
10004.611922.38210014.431927.65810026.491937.59110038.551939.06110050.611942.298
10058.271947.09610062.671949.16710074.731952.64510086.791952.82610094.041954.097
10098.861955.71210110.921957.64110122.981956.34410183.281957.33210202.91 1958.27
#Mann= 3 , 0 , 0
9655.133  0.0514       09655.133  0.0514       010202.91  0.0514       0
#XS Ineff= 2 , 0
       0                               0
Bank Sta=9655.133,10202.91
Exp/Cntr=0.3,0.1

Type RM Length L Ch R = 3 ,50153.58,,,
BEGIN DESCRIPTION:
END DESCRIPTION:
Bridge Culvert--1,0,-1,-1, 0
Deck Dist Width WeirC Skew NumUp NumDn MinLoCord MaxHiCord MaxSubmerge Is_Ogee
8.955700,53.149500,2.6,0, 38, 38, , , 0.95, 0, 0,0,,
 9808.37 9820.39 9824.76 9832.43 9842.70 9844.47 9856.52 9860.65 9868.56 9878.59
 9880.61 9892.65 9896.53 9904.69 9914.48 9916.74 9923.78 9950.95 9950.9510049.05
10049.0510066.6610073.3110075.9610085.3510093.9110097.4010109.4410111.8510121.48
10129.7910133.5310145.5710147.7310157.6210165.6810169.6610174.70
 1955.08 1954.10 1953.78 1953.13 1952.37 1952.25 1951.62 1951.47 1951.27 1951.18
 1951.18 1951.35 1951.45 1951.67 1952.08 1952.19 1950.51 1951.22 1951.22 1953.76
 1953.76 1954.22 1954.98 1955.06 1955.30 1955.46 1955.51 1955.63 1955.67 1955.85
 1955.99 1956.03 1956.29 1956.33 1956.56 1956.76 1956.84 1956.95
  955.08  954.10  953.78  953.13  952.37  952.25  951.62  951.47  951.27  951.18
  951.18  951.35  951.45  951.67  952.08  952.19  950.51  951.22 1945.22 1947.76
  953.76  954.22  954.98  955.06  955.30  955.46  955.51  955.63  955.67  955.85
  955.99  956.03  956.29  956.33  956.56  956.76  956.84  956.95
 9808.37 9820.39 9824.76 9832.43 9842.70 9844.47 9856.52 9860.65 9868.56 9878.59
 9880.61 9892.65 9896.53 9904.69 9914.48 9916.74 9923.78 9950.95 9950.9510049.05
10049.0510066.6610073.3110075.9610085.3510093.9110097.4010109.4410111.8510121.48
10129.7910133.5310145.5710147.7310157.6210165.6810169.6610174.70
 1955.08 1954.10 1953.78 1953.13 1952.37 1952.25 1951.62 1951.47 1951.27 1951.18
 1951.18 1951.35 1951.45 1951.67 1952.08 1952.19 1950.51 1951.22 1951.22 1953.76
 1953.76 1954.22 1954.98 1955.06 1955.30 1955.46 1955.51 1955.63 1955.67 1955.85
 1955.99 1956.03 1956.29 1956.33 1956.56 1956.76 1956.84 1956.95
  955.08  954.10  953.78  953.13  952.37  952.25  951.62  951.47  951.27  951.18
  951.18  951.35  951.45  951.67  952.08  952.19  950.51  951.22 1945.22 1947.76
  953.76  954.22  954.98  955.06  955.30  955.46  955.51  955.63  955.67  955.85
  955.99  956.03  956.29  956.33  956.56  956.76  956.84  956.95
BR Coef=-1 , 0 , 0 ,, 0 ,,,0.8,0,1,0,
WSPro=,,,, 1 ,,,, 0 ,,,, 0 ,,,,-1 ,-1 ,-1 , 0 , 0 , 0 , 0 , 0
BC Design=,, 0 ,, 0 ,,,,,,

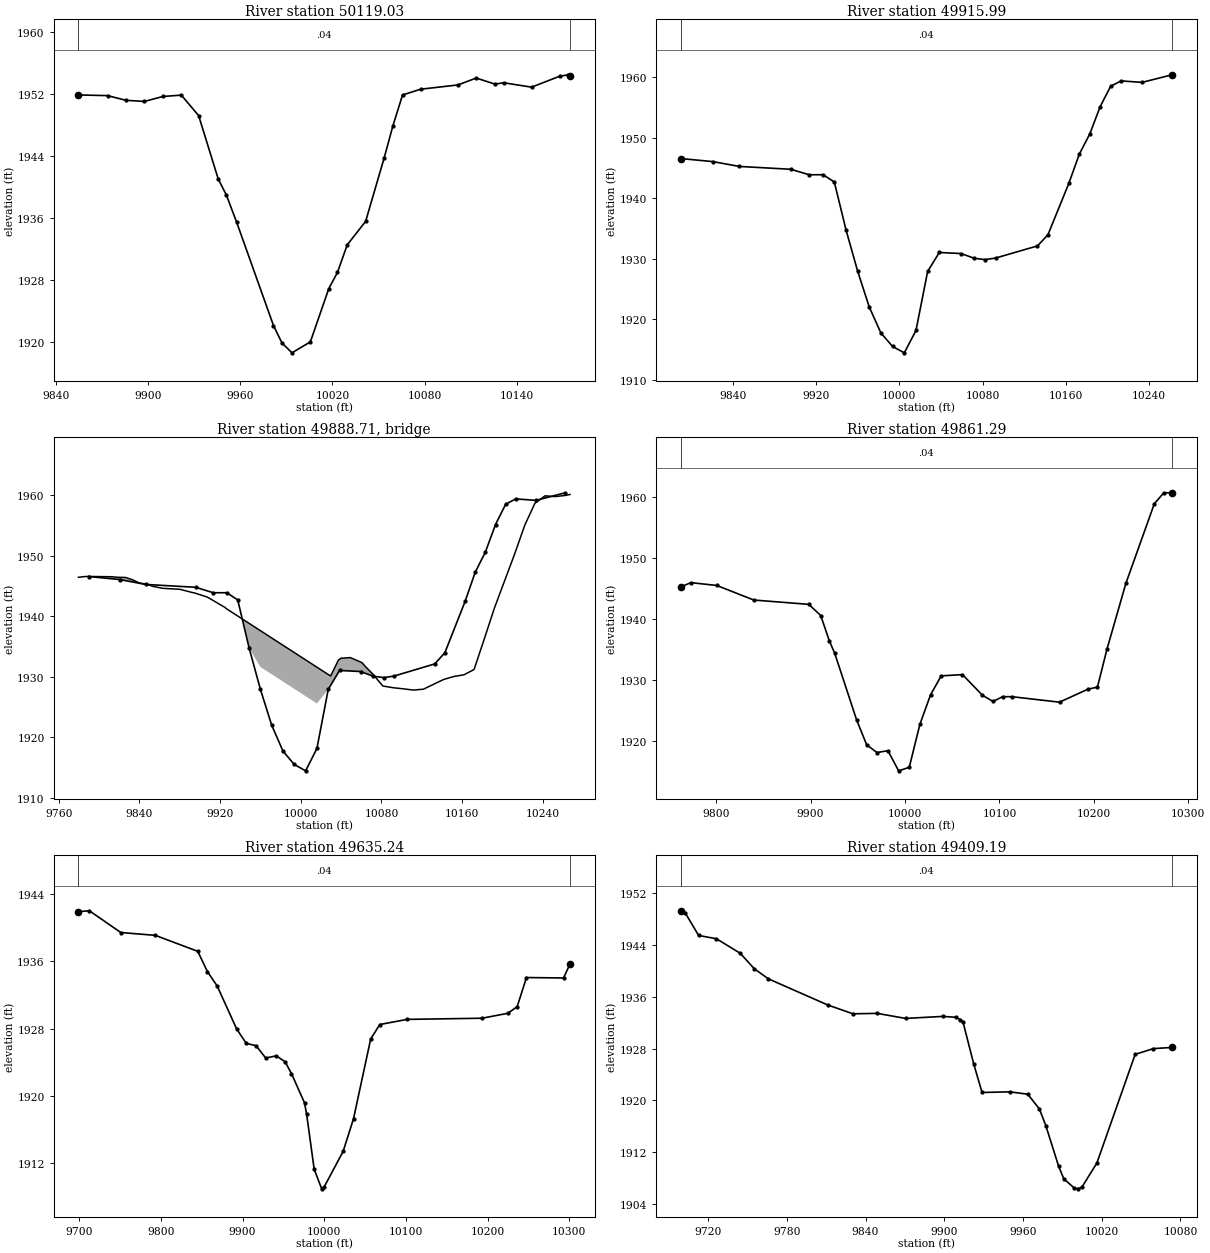
Type RM Length L Ch R = 1 ,50119.03,203.032000,203.032000,203.032000
XS GIS Cut Line= 2
696688.303122252784990.812451214696511.219788909784724.145784542
#Sta/Elev= 30
9854.5651951.8649873.5461951.777 9885.551951.1739897.5541951.0279909.5591951.665
9921.5631951.8439932.8431949.1999945.5711941.056 9950.921938.9639957.5751935.478
9981.5831922.1639987.0731919.9289993.5871918.64910005.59 1920.06 10017.61926.928
10023.231929.001 10029.6 1932.56 10041.61935.59210053.611943.72910059.381947.913
10065.61 1951.8610077.461952.60410101.621953.14910113.611954.04110125.631953.267
10131.691953.42610149.641952.86610167.841954.26710173.651954.46110174.671954.326
#Mann= 3 , 0 , 0
9854.565    0.04       09854.565    0.04       010174.67    0.04       0
#XS Ineff= 2 , 0
       0                               0
Bank Sta=9854.565,10174.67
Exp/Cntr=0.3,0.1

Type RM Length L Ch R = 1 ,49915.99,54.709500,54.709500,54.709500
XS GIS Cut Line= 4
696807.053122252784815.812451214696707.053122252784726.229117885
696571.636455595784657.479117885696386.219788909784638.729117885
#Sta/Elev= 30
9789.7231946.5289820.9141946.0169846.182 1945.229895.8491944.7489913.3111943.842
9926.6961943.8499937.498 1942.669948.7861934.7139959.9281927.9099971.143 1921.96
9982.3581917.6739993.5731915.45610004.791914.408   100161918.10310027.221927.868
10038.431930.99810059.241930.82410072.081930.03410082.521929.81910092.571930.079
10132.781932.08310142.831933.92310162.931942.42110172.981947.25110183.031950.574
10193.081955.12410203.13 1958.4810213.181959.35810233.291959.11610262.21 1960.37
#Mann= 3 , 0 , 0
9789.723    0.04       09789.723    0.04       010262.21    0.04       0
#XS Ineff= 2 , 0
       0                10048.35       0
Bank Sta=9789.723,10262.21
Exp/Cntr=0.3,0.1

Type RM Length L Ch R = 3 ,49888.71,,,
BEGIN DESCRIPTION:
END DESCRIPTION:
Bridge Culvert--1,0,-1,-1, 0
Deck Dist Width WeirC Skew NumUp NumDn MinLoCord MaxHiCord MaxSubmerge Is_Ogee
15.051650,24.606200,2.6,0, 58, 58, , , 0.95, 0, 0,0,,
 9779.56 9785.74 9788.79 9799.29 9803.61 9812.84 9818.42 9826.40 9833.24 9839.95
 9848.05 9853.50 9862.87 9867.06 9877.68 9880.61 9892.49 9894.17 9907.31 9907.72
 9912.28 9920.06 9925.00 9925.70 9937.59 9937.5910029.5710032.7310032.7310037.35
10039.8110049.0810058.9510060.8110063.7710071.2810081.3410091.3910101.4410111.50
10121.5510131.6010136.7110141.6610151.7110161.7610171.8110181.8710191.9210201.97
10212.0310222.0810232.1310234.2210242.1910252.2410262.2910266.93
 1946.40 1946.52 1946.54 1946.52 1946.51 1946.49 1946.40 1946.37 1945.98 1945.46
 1945.21 1944.90 1944.58 1944.54 1944.44 1944.40 1943.88 1943.84 1943.13 1943.09
 1942.65 1941.88 1941.41 1941.27 1939.99 1939.99 1930.08 1931.15 1931.15 1932.73
 1933.02 1933.13 1932.42 1932.27 1931.70 1930.43 1928.43 1928.15 1927.97 1927.76
 1927.90 1928.71 1929.12 1929.51 1930.00 1930.28 1931.16 1936.18 1941.29 1945.77
 1950.25 1955.02 1958.64 1958.89 1959.87 1959.74 1959.93 1960.09
  946.40  946.52  946.54  946.52  946.51  946.49  946.40  946.37  945.98  945.46
  945.21  944.90  944.58  944.54  944.44  944.40  943.88  943.84  943.13  943.09
  942.65  941.88  941.41  941.27  939.99 1933.99 1924.08 1925.15  931.15  932.73
  933.02  933.13  932.42  932.27  931.70  930.43  928.43  928.15  927.97  927.76
  927.90  928.71  929.12  929.51  930.00  930.28  931.16  936.18  941.29  945.77
  950.25  955.02  958.64  958.89  959.87  959.74  959.93  960.09
 9779.56 9785.74 9788.79 9799.29 9803.61 9812.84 9818.42 9826.40 9833.24 9839.95
 9848.05 9853.50 9862.87 9867.06 9877.68 9880.61 9892.49 9894.17 9907.31 9907.72
 9912.28 9920.06 9921.12 9921.12 9925.00 9925.7010016.2610016.2610029.5710037.35
10039.8110049.0810058.9510060.8110063.7710071.2810081.3410091.3910101.4410111.50
10121.5510131.6010136.7110141.6610151.7110161.7610171.8110181.8710191.9210201.97
10212.0310222.0810232.1310234.2210242.1910252.2410262.2910266.93
 1946.40 1946.52 1946.54 1946.52 1946.51 1946.49 1946.40 1946.37 1945.98 1945.46
 1945.21 1944.90 1944.58 1944.54 1944.44 1944.40 1943.88 1943.84 1943.13 1943.09
 1942.65 1941.88 1941.78 1941.78 1941.41 1941.27 1931.51 1931.51 1930.08 1932.73
 1933.02 1933.13 1932.42 1932.27 1931.70 1930.43 1928.43 1928.15 1927.97 1927.76
 1927.90 1928.71 1929.12 1929.51 1930.00 1930.28 1931.16 1936.18 1941.29 1945.77
 1950.25 1955.02 1958.64 1958.89 1959.87 1959.74 1959.93 1960.09
  946.40  946.52  946.54  946.52  946.51  946.49  946.40  946.37  945.98  945.46
  945.21  944.90  944.58  944.54  944.44  944.40  943.88  943.84  943.13  943.09
  942.65  941.88  941.78 1935.78 1935.41 1935.27 1925.51  931.51  930.08  932.73
  933.02  933.13  932.42  932.27  931.70  930.43  928.43  928.15  927.97  927.76
  927.90  928.71  929.12  929.51  930.00  930.28  931.16  936.18  941.29  945.77
  950.25  955.02  958.64  958.89  959.87  959.74  959.93  960.09
BR Coef=-1 , 0 , 0 ,, 0 ,,,0.8,0,1,0,
WSPro=,,,, 1 ,,,, 0 ,,,, 0 ,,,,-1 ,-1 ,-1 , 0 , 0 , 0 , 0 , 0
BC Design=,, 0 ,, 0 ,,,,,,

Type RM Length L Ch R = 1 ,49861.29,226.047700,226.047700,226.047700
XS GIS Cut Line= 4
696838.303122252784792.895784542696729.969788909784678.312451214
696586.219788909784603.312451214696386.219788909784584.562451214
#Sta/Elev= 30
9762.2641945.225 9773.131945.9559800.653 1945.499839.8511943.0999898.0741942.394
9910.748 1940.569919.9511936.3599925.5571934.3689948.7311923.4519959.3951919.351
 9970.351918.0839981.9531918.3849993.2321915.08110004.511915.66110015.791922.711
10027.071927.54310038.351930.66110060.91 1930.8710082.09 1927.4710093.361926.461
 10103.41927.25310113.45 1927.2410163.671926.345 10193.81928.47910203.84 1928.81
10213.891935.01310233.971945.835 10264.11958.89610274.151960.69510282.97 1960.68
#Mann= 3 , 0 , 0
9762.264    0.04       09762.264    0.04       010282.97    0.04       0
#XS Ineff= 2 , 0
       0                10033.54       0
Bank Sta=9762.264,10282.97
Exp/Cntr=0.3,0.1

Type RM Length L Ch R = 1 ,49635.24,226.047800,226.047800,226.047800
XS GIS Cut Line= 6
697021.339832718784850.684617211696995.989948489784803.547765007
696973.883610004784766.928786883696848.172874742784570.320994564
696780.595487057784433.426006366 696724.08321216784327.987171827
#Sta/Elev= 30
9699.0141941.9079712.399 1942.019750.8861939.4269793.1491939.0899845.1311937.189
9857.0141934.7719868.8961933.0699892.6611927.9819904.5431926.2429916.4261925.977
9928.3081924.5099941.3531924.7639952.0731924.0639959.8671922.6589975.8381919.181
9978.3811917.8589987.7211911.2749996.8951908.9539999.6081909.12410023.171913.411
10035.841917.28810056.911926.77510068.061928.48910101.521929.09910193.191929.236
10224.941929.82410236.281930.61810247.631934.07310293.011934.02110300.97 1935.68
#Mann= 3 , 0 , 0
9699.014    0.04       09699.014    0.04       010300.97    0.04       0
#XS Ineff= 2 , 0
       0                               0
Bank Sta=9699.014,10300.97
Exp/Cntr=0.3,0.1

Type RM Length L Ch R = 1 ,49409.19,226.047700,226.047700,226.047700
XS GIS Cut Line= 6
697186.600327139784688.266502002697179.228343369784661.920776527
697162.174972571  784617.8056439697127.222375738784555.600837297
697086.426392829  784502.4719514696976.323508171784384.360817385
#Sta/Elev= 30
9699.0591949.2739702.4511949.0049712.8351945.4639726.4161944.9559744.5581942.713
9755.2791940.323    97661938.7699811.2321934.7379830.3871933.3779848.9041933.442
9870.5841932.6629898.6751932.975 9908.861932.8429912.1391932.4829914.2191932.158
9922.4081925.6669928.7971921.2389949.8941921.3359963.6371920.9729972.531 1918.68
 9977.381916.1219987.1091909.8749991.1231907.894    99991906.50910001.681906.368
10004.871906.62710016.28 1910.3510045.461927.11710059.361928.00510073.631928.187
#Mann= 3 , 0 , 0
9699.059    0.04       09699.059    0.04       010073.63    0.04       0
#XS Ineff= 2 , 0
       0                               0
Bank Sta=9699.059,10073.63
Exp/Cntr=0.3,0.1

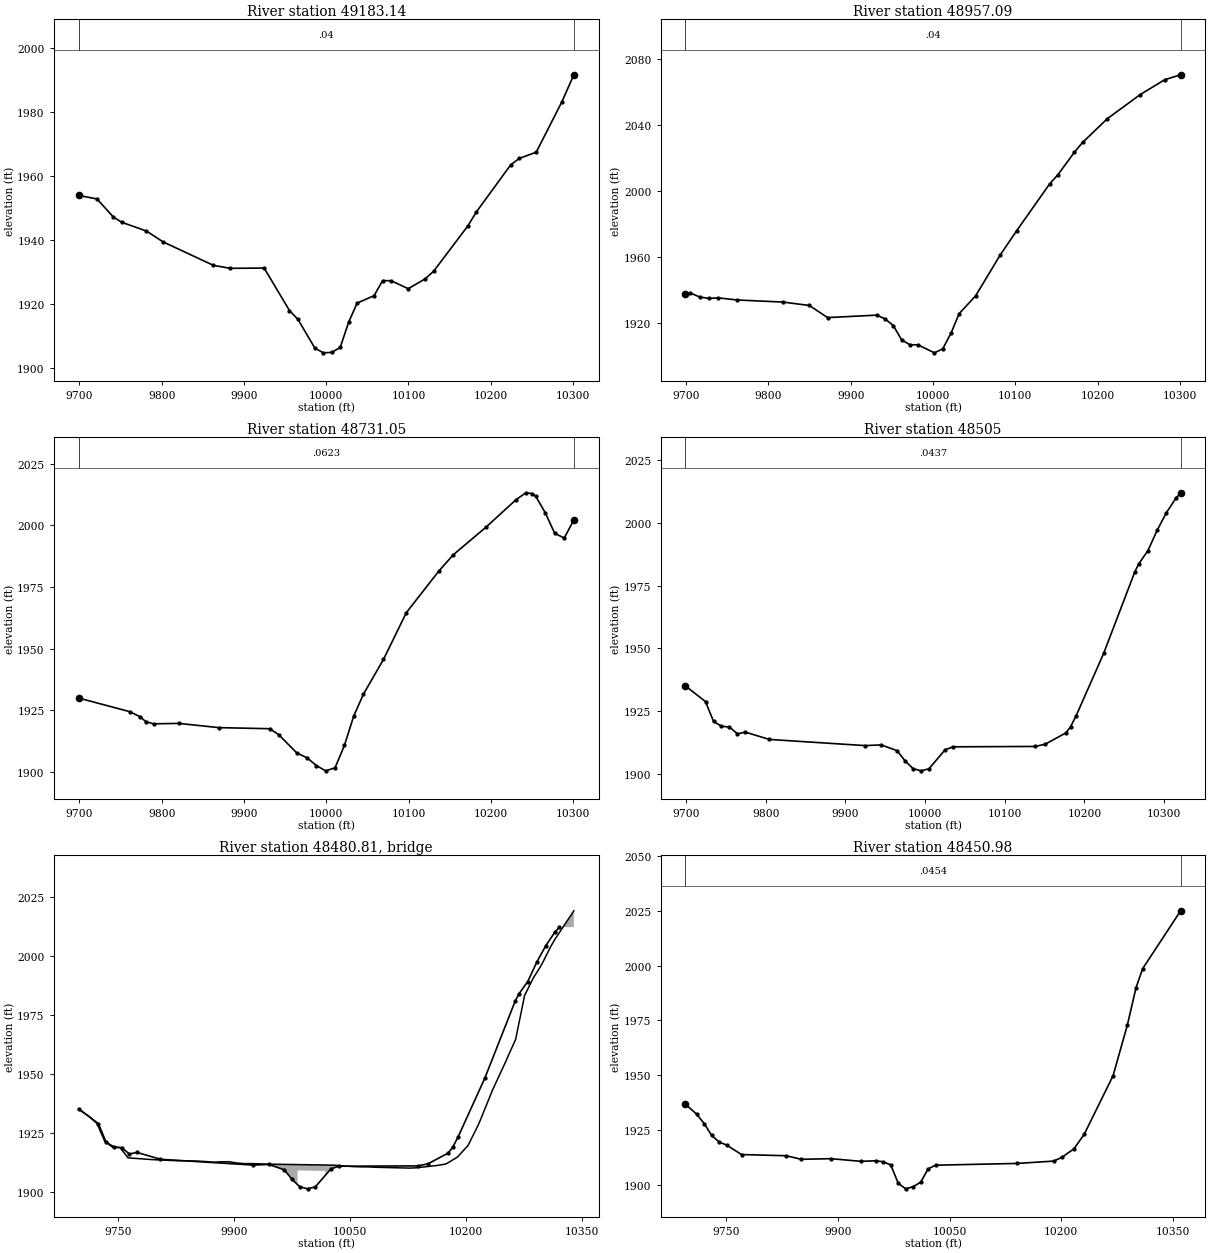
Type RM Length L Ch R = 1 ,49183.14,226.047800,226.047800,226.047800
XS GIS Cut Line= 6
697264.307226349784627.277583897697264.906297344784599.926326705
697262.426192439784552.687183336697250.808318739784482.251342072
697202.583681364784279.650179313697136.878419187784040.903945421
#Sta/Elev= 30
 9699.031954.0089721.313 1952.919741.3351947.2479751.349 1945.649781.453 1942.89
9801.6441939.5119862.8431932.1889883.4021931.2539924.521 1931.34 9955.361918.085
9965.6391915.3219986.1991906.3619996.4781904.88310006.751905.03110017.031906.563
10027.311914.48810037.591920.40710058.191922.72410068.571927.41510078.94 1927.38
10099.681924.89910120.421927.983 10130.81930.41810172.281944.53210182.661948.905
10224.141963.50510234.511965.54310255.261967.48210286.371983.16910300.99 1991.65
#Mann= 3 , 0 , 0
 9699.03    0.04       0 9699.03    0.04       010300.99    0.04       0
#XS Ineff= 2 , 0
       0                               0
Bank Sta=9699.03,10300.99
Exp/Cntr=0.3,0.1

Type RM Length L Ch R = 1 ,48957.09,226.047700,226.047700,226.047700
XS GIS Cut Line= 6
697352.173914983784580.224775762697411.683773592784463.935092525
697431.417034797784393.056965435697436.193949233784334.580904222
697434.888195648784210.160819579697439.290361494783995.807225418
#Sta/Elev= 30
9699.0761937.5479705.0241938.055 9716.411935.6019727.7951934.7359739.181 1935.07
9761.9521933.789 9817.541932.5319849.7181930.4539871.8391923.0879931.7011924.588
9941.7231922.3089951.7331918.2519961.7441909.6259971.7451906.5999981.746 1906.52
10001.751901.66910011.751904.10610021.75 1913.4810031.751925.48410051.751936.301
10081.751961.20510101.761975.92810141.762004.34110151.772009.87510171.772023.529
10181.772029.51110211.78 2043.9410251.792058.61310281.792067.68910300.992070.656
#Mann= 3 , 0 , 0
9699.076    0.04       09699.076    0.04       010300.99    0.04       0
#XS Ineff= 2 , 0
       0                               0
Bank Sta=9699.076,10300.99
Exp/Cntr=0.3,0.1

Type RM Length L Ch R = 1 ,48731.05,226.047800,226.047800,226.047800
XS GIS Cut Line= 6
697398.080319879784549.765564804697515.208812575784441.085690274
697670.211945447784349.539130476697720.365947898784311.925013594
697781.065485743784247.329412415 697840.51633562784154.909954996
#Sta/Elev= 30
9699.0811930.0359761.119 1924.529773.725 1922.45 9780.741920.4789790.1311919.573
9820.7221919.7479869.6711918.0339931.3591917.5959942.2241915.189 9963.99 1907.83
9976.7911905.7669988.0491902.6599999.3071900.51710010.691901.73610022.091910.818
10033.491922.79710045.251931.62510069.57 1945.6910097.311964.63910136.461981.351
10154.471988.14610193.751999.18210230.412010.37310242.632013.24810249.972012.951
10254.592011.81610266.142005.16310277.691996.77210289.25  1994.9 10300.9 2002.24
#Mann= 3 , 0 , 0
9699.081  0.0623       09699.081  0.0623       0 10300.9  0.0623       0
#XS Ineff= 2 , 0
       0                               0
Bank Sta=9699.081,10300.9
Exp/Cntr=0.3,0.1

Type RM Length L Ch R = 1 ,   48505,54.014900,54.014900,54.014900
XS GIS Cut Line= 4
697359.830899984784608.833284557697784.830899984784581.055506766
697841.775344461784535.222173437697904.275344461784429.666617885
#Sta/Elev= 30
9699.1361935.0569724.3591928.815 9734.381920.9399744.4021919.0049754.4231918.663
9764.444 1915.979774.4661916.632 9804.531913.7329924.7861911.2719944.8281911.558
9964.8711909.2569974.8921905.1719984.9141902.0859994.9351901.21110004.961902.044
   100251909.59810035.021910.788 10138.11910.93310150.651911.81310176.61 1916.31
10182.551918.74810189.44 1923.05 10224.11947.99910263.351980.60510268.131983.701
10279.75    198910291.371997.19610302.992004.16410314.612009.81410320.812012.068
#Mann= 3 , 0 , 0
9699.136  0.0437       09699.136  0.0437       010320.81  0.0437       0
#XS Ineff= 2 , 0
       0                               0
Bank Sta=9699.136,10320.81
Exp/Cntr=0.3,0.1

Type RM Length L Ch R = 3 ,48480.81,,,
BEGIN DESCRIPTION:
END DESCRIPTION:
Bridge Culvert--1,0,-1,-1, 0
Deck Dist Width WeirC Skew NumUp NumDn MinLoCord MaxHiCord MaxSubmerge Is_Ogee
10.603300,32.808300,2.6,0, 52, 52, , , 0.95, 0, 0,0,,
 9698.78 9702.56 9712.59 9722.61 9732.63 9742.66 9752.68 9762.70 9792.77 9822.84
 9852.91 9862.94 9872.96 9882.98 9893.01 9903.03 9913.05 9923.08 9943.12 9981.96
 9981.9610018.0410018.0410027.8610053.3810063.4010073.4210083.4510127.5510135.53
10162.1410172.5210175.4510188.7510202.0510202.8510215.3610218.0910234.2310252.50
10254.5410263.9910274.8410275.4810286.9610295.1510298.4510309.9410315.4610332.92
10335.7710339.37
 1935.09 1934.09 1931.83 1928.84 1921.29 1918.87 1918.60 1914.34 1913.61 1913.17
 1912.96 1912.78 1912.49 1912.68 1912.71 1912.18 1911.89 1911.91 1911.68 1911.48
 1911.48 1911.30 1911.30 1911.25 1910.64 1910.52 1910.51 1910.34 1909.99 1910.13
 1911.09 1911.65 1912.00 1914.67 1919.40 1919.81 1928.02 1930.05 1943.09 1955.99
 1957.63 1964.41 1981.76 1982.97 1990.57 1994.77 1996.65 2004.12 2007.19 2015.81
 2017.13 2018.99
  935.09  934.09  931.83  928.84  921.29  918.87  918.60  914.34  913.61  913.17
  912.96  912.78  912.49  912.68  912.71  912.18  911.89  911.91  911.68  911.48
 1908.98 1908.80  911.30  911.25  910.64  910.52  910.51  910.34  909.99  910.13
  911.09  911.65  912.00  914.67  919.40  919.81  928.02  930.05  943.09  955.99
  957.63  964.41  981.76  982.97  990.57  994.77  996.65 1004.12 1007.19 1015.81
 1017.13 1018.99
 9698.78 9702.56 9712.59 9722.61 9732.63 9742.66 9752.68 9762.70 9792.77 9822.84
 9852.91 9862.94 9872.96 9882.98 9893.01 9903.03 9913.05 9923.08 9943.12 9981.96
 9981.9610018.0410018.0410027.8610053.3810063.4010073.4210083.4510127.5510135.53
10162.1410172.5210175.4510188.7510202.0510202.8510215.3610218.0910234.2310252.50
10254.5410263.9910274.8410275.4810286.9610295.1510298.4510309.9410315.4610332.92
10335.7710339.37
 1935.09 1934.09 1931.83 1928.84 1921.29 1918.87 1918.60 1914.34 1913.61 1913.17
 1912.96 1912.78 1912.49 1912.68 1912.71 1912.18 1911.89 1911.91 1911.68 1911.48
 1911.48 1911.30 1911.30 1911.25 1910.64 1910.52 1910.51 1910.34 1909.99 1910.13
 1911.09 1911.65 1912.00 1914.67 1919.40 1919.81 1928.02 1930.05 1943.09 1955.99
 1957.63 1964.41 1981.76 1982.97 1990.57 1994.77 1996.65 2004.12 2007.19 2015.81
 2017.13 2018.99
  935.09  934.09  931.83  928.84  921.29  918.87  918.60  914.34  913.61  913.17
  912.96  912.78  912.49  912.68  912.71  912.18  911.89  911.91  911.68  911.48
 1908.98 1908.80  911.30  911.25  910.64  910.52  910.51  910.34  909.99  910.13
  911.09  911.65  912.00  914.67  919.40  919.81  928.02  930.05  943.09  955.99
  957.63  964.41  981.76  982.97  990.57  994.77  996.65 1004.12 1007.19 1015.81
 1017.13 1018.99
BR Coef=-1 , 0 , 0 ,, 0 ,,,0.8,0,1,0,
WSPro=,,,, 1 ,,,, 0 ,,,, 0 ,,,,-1 ,-1 ,-1 , 0 , 0 , 0 , 0 , 0
BC Design=,, 0 ,, 0 ,,,,,,

Type RM Length L Ch R = 1 ,48450.98,272.595100,272.595100,272.595100
XS GIS Cut Line= 5
697359.830899984784662.999951214697658.442011118784643.555506766
697804.275344461784631.055506766697866.775344461784562.999951214
697930.664233357784453.277729005
#Sta/Elev= 30
9695.3461936.7539710.5471932.1289720.5681927.847 9730.59 1922.479740.6111919.434
9750.6321918.0699770.6741913.7129830.801 1913.179850.8441911.5489890.9281911.829
9931.0131910.6169951.0561910.8789961.0771910.3889971.0981908.9399981.1191900.573
 9991.141898.04510001.171899.02710011.211901.07410021.241907.17910031.281908.851
10140.961909.65810189.911910.72910201.171912.49410217.071916.37310230.731922.919
10269.581949.724 10288.91973.09510300.47 1990.0410309.321998.69110360.33 2025.13
#Mann= 3 , 0 , 0
9695.346  0.0454       09695.346  0.0454       010360.33  0.0454       0
#XS Ineff= 2 , 0
       0                               0
Bank Sta=9695.346,10360.33
Exp/Cntr=0.3,0.1