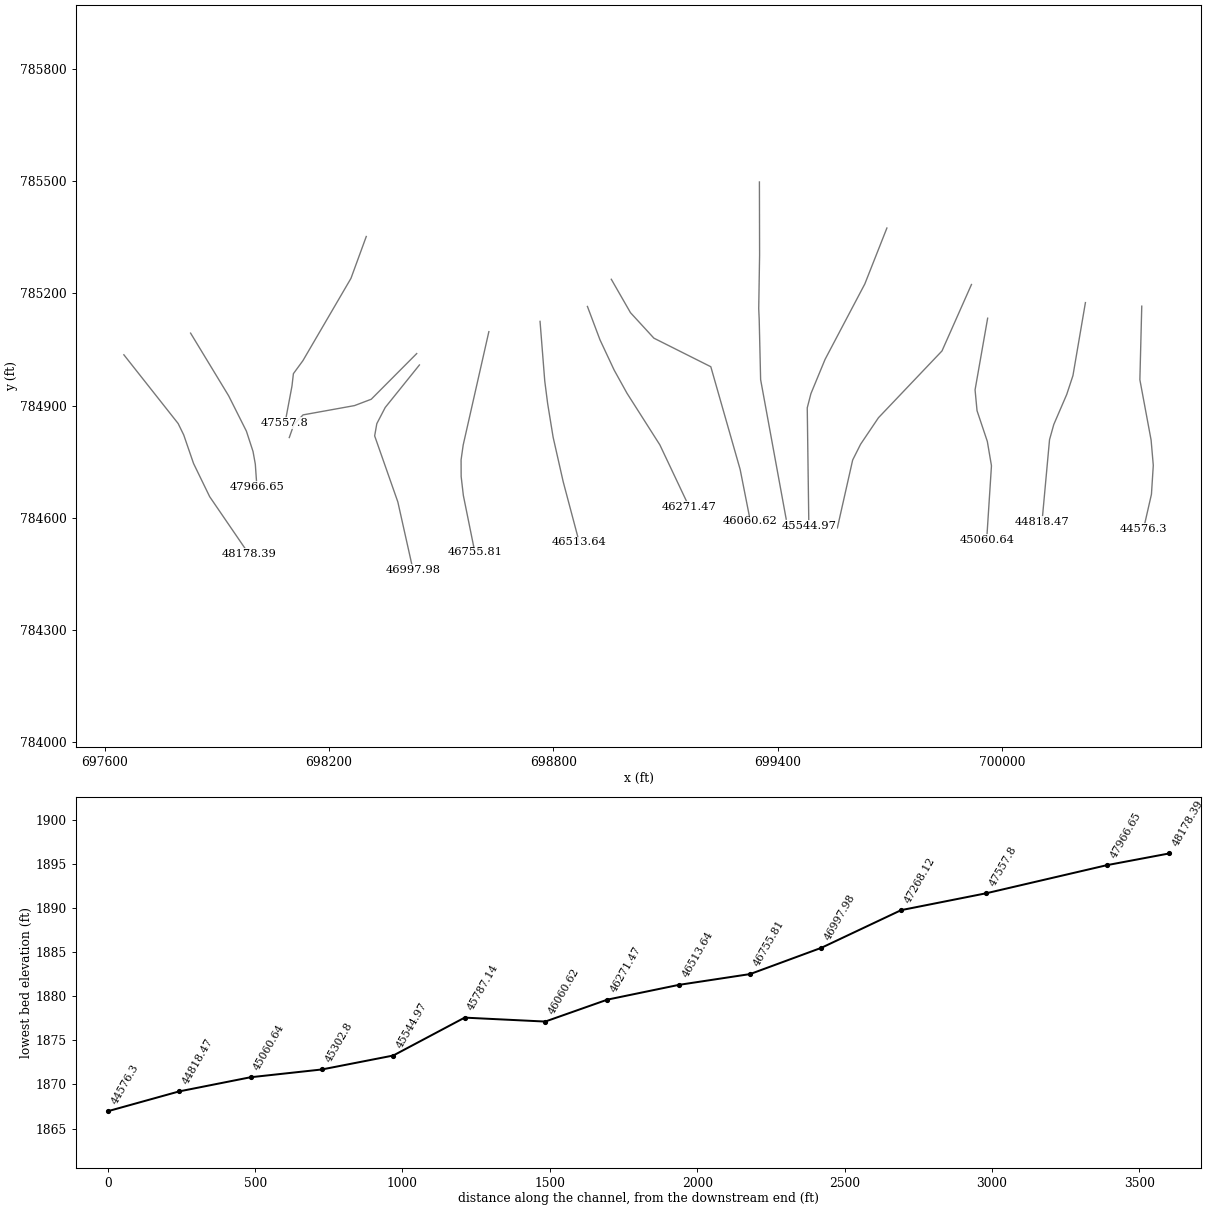
HEC-RAS study 14536_ras.prj: 14536

--- 14536_ras.g01 (geometry) --- (continued)

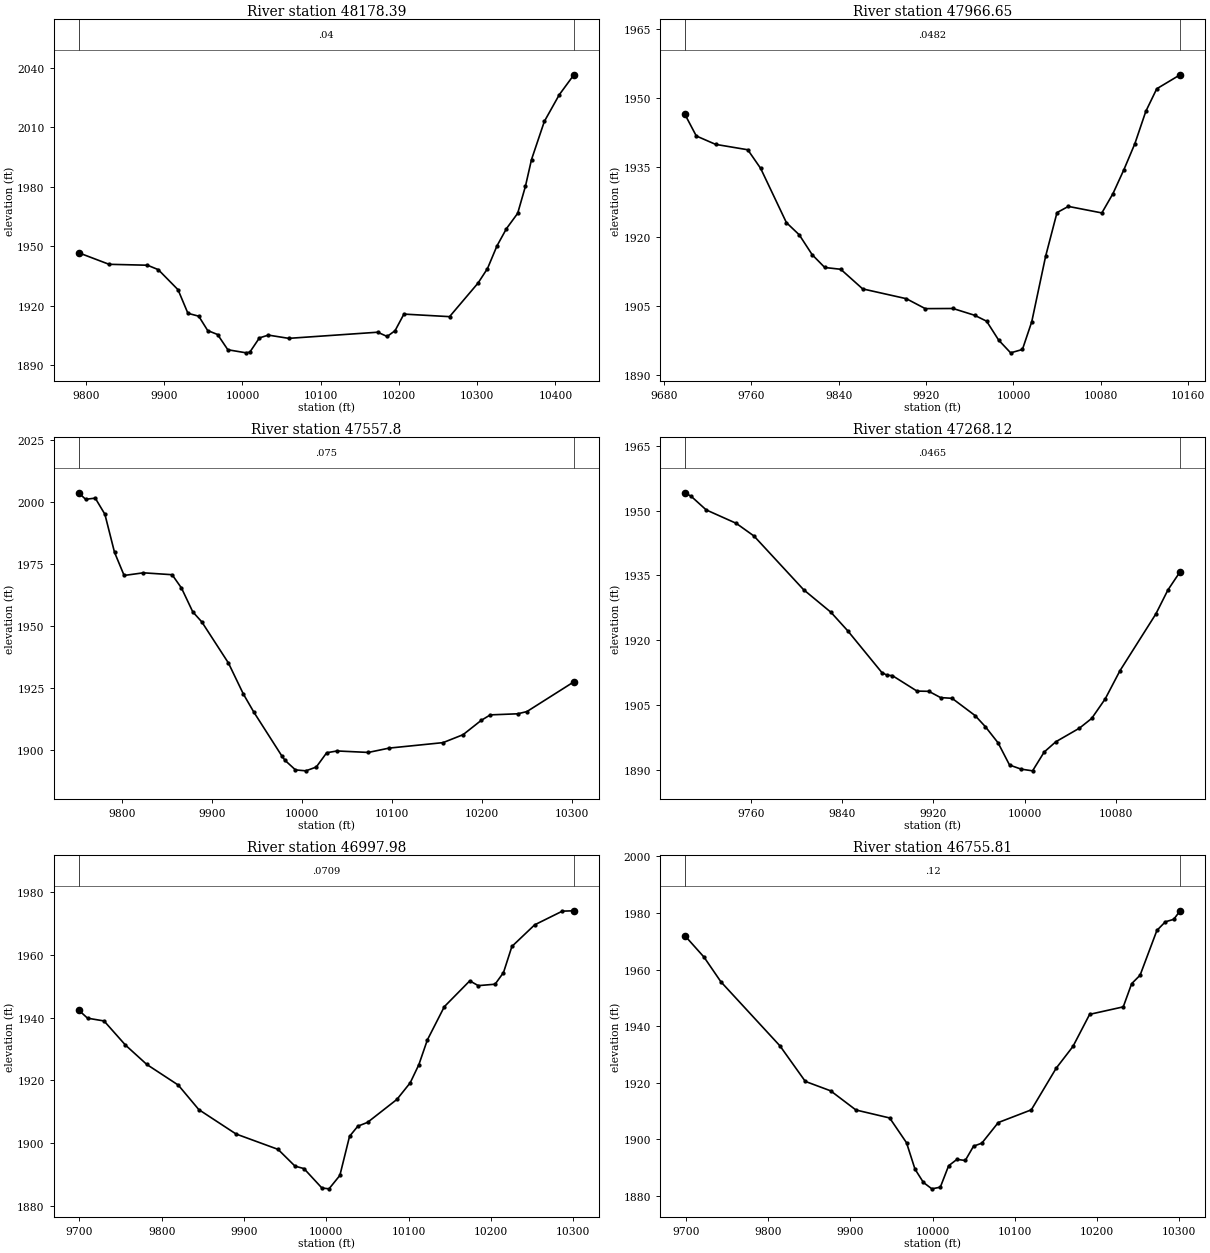
Type RM Length L Ch R = 1 ,48178.39,211.740300,211.740300,211.740300
XS GIS Cut Line= 6
697651.699978878785035.946233104697796.766319289 784852.24085323
697811.758002206 784821.58488592 697837.97975181784745.408704678
697881.094977095784656.621790493697985.583681687784503.815099994
#Sta/Elev= 30
9790.6391946.6799829.5191940.8519878.6411940.3839892.4371938.1589917.6951928.024
9930.3241916.1329944.1361914.6819955.5811907.4379968.2541905.4299981.3611897.739
10004.831896.18810009.491896.56510021.69 1903.7210033.121905.13510059.181903.495
10172.87 1906.5910184.92 1904.4410195.05 1907.3510206.381915.73310264.721914.442
10301.071931.35810313.181938.696 10325.31950.12810337.411958.83110351.751966.554
10361.641980.15310369.461993.70610385.872012.941 10404.9 2026.3710423.652036.453
#Mann= 3 , 0 , 0
9790.639    0.04       09790.639    0.04       010423.65    0.04       0
#XS Ineff= 2 , 0
       0                               0
Bank Sta=9790.639,10423.65
Exp/Cntr=0.3,0.1

Type RM Length L Ch R = 1 ,47966.65,408.851800,408.851800,408.851800
XS GIS Cut Line= 6
697830.079647707785093.910248815697931.941427965784926.115303136
697979.325581816784831.713955333697997.018120947784777.488552075
698003.137012414784743.606429149698007.352229028784683.643810504
#Sta/Elev= 30
9699.0171946.5249709.5191941.8089727.2021939.9919756.6681938.8229768.4551934.795
9792.0291923.0569803.8161920.4069815.6551916.1039827.1781913.3349841.8231912.948
  9861.91908.7019901.8711906.5829919.2211904.4289944.6321904.4589964.4111902.991
9975.4081901.7089986.4041897.6249997.4011894.858 10008.21895.58610016.741901.586
10029.471915.78710039.871925.22210050.281926.55910080.941925.14710091.111929.322
10101.151934.51910111.181940.143 10121.21947.13510131.221952.02710152.631955.056
#Mann= 3 , 0 , 0
9699.017  0.0482       09699.017  0.0482       010152.63  0.0482       0
#XS Ineff= 2 , 0
       0                               0
Bank Sta=9699.017,10152.63
Exp/Cntr=0.3,0.1

Type RM Length L Ch R = 1 , 47557.8,289.673900,289.673900,289.673900
XS GIS Cut Line= 6
698299.831643492785352.284596741698258.842778891785240.248366892
698130.411003202785020.274793655 698105.00000003784985.519489646
698101.133156598784952.186456427698082.590661258784853.586744368
#Sta/Elev= 30
9751.2652003.5639759.0642000.938 9769.77 2001.419780.4761994.9389791.1821979.626
9801.8881970.292  9823.31971.3589855.2841970.5959865.6851965.2439878.2481955.657
9888.283 1951.629917.9141935.0789934.6021922.5399946.1821915.3059977.4141897.627
9980.9211895.885  9992.51892.05510004.081891.67710015.661893.20910027.241898.954
10038.821899.67610073.561899.08210096.721900.82710156.661903.02510178.991906.227
10199.131911.97810209.271914.195 10239.81914.63110249.971915.52210302.291927.504
#Mann= 3 , 0 , 0
9751.265   0.075       09751.265   0.075       010302.29   0.075       0
#XS Ineff= 2 , 0
       0                               0
Bank Sta=9751.265,10302.29
Exp/Cntr=0.3,0.1

Type RM Length L Ch R = 1 ,47268.12,270.145200,270.145200,270.145200
XS GIS Cut Line= 6
698434.625517949785039.203389713698313.140183564784917.115142988
698268.279698599784900.102627566698130.816805837784875.292720927
698106.234514912784849.477219318698093.935330419784814.678167917
#Sta/Elev= 30
9701.9981954.1489707.5331953.3399720.7011950.1889747.0371947.0789762.6111944.139
9806.1421931.7029830.1051926.4759844.8331922.1839874.7681912.5139879.5451911.871
9883.8461911.8279905.5291908.2259915.9381908.1699926.2371906.718 9936.311906.552
9956.455 1902.569965.455 1899.999976.601 1896.259986.6741891.1049996.7461890.156
10006.861889.75710017.051894.11410027.231896.48710047.961899.64310058.67 1901.89
10070.531906.41110083.461912.93610114.921926.07610125.491931.62910136.221935.871
#Mann= 3 , 0 , 0
9701.998  0.0465       09701.998  0.0465       010136.22  0.0465       0
#XS Ineff= 2 , 0
       0                               0
Bank Sta=9701.998,10136.22
Exp/Cntr=0.3,0.1

Type RM Length L Ch R = 1 ,46997.98,242.167700,242.167700,242.167700
XS GIS Cut Line= 6
 698441.93416111785008.749127268698350.391866785784894.966962137
698327.991649727 784851.76000268698322.242246529784819.099236007
698384.205442942 784642.56792368698424.760545249784461.233973258
#Sta/Elev= 30
9699.1371942.4349709.9811939.8459730.0261938.962 9756.041931.2779782.0531925.095
9820.2121918.5429845.2151910.7199890.4421902.9589941.4471898.0659962.0871892.721
9972.9451891.9439994.6721885.77810003.351885.49510016.551889.75910028.311902.209
10038.381905.44610050.171906.65810085.881913.97710102.011919.25510112.541925.043
 10122.91932.935 10143.51943.512 10174.41951.735 10184.71950.20710205.161950.668
10215.37 1954.3710225.591962.68710253.231969.57110286.881973.93410300.951974.051
#Mann= 3 , 0 , 0
9699.137  0.0709       09699.137  0.0709       010300.95  0.0709       0
#XS Ineff= 2 , 0
       0                               0
Bank Sta=9699.137,10300.95
Exp/Cntr=0.3,0.1

Type RM Length L Ch R = 1 ,46755.81,242.167700,242.167700,242.167700
XS GIS Cut Line= 6
698627.580658774785097.801411425 698558.93811088784794.680683868
698553.303995132784754.905262635698553.520921546784710.346623355
698559.397959265784659.832248485698590.232109753784507.438000729
#Sta/Elev= 30
9699.022 1971.999722.3991964.3779742.9031955.6599814.6691933.0189845.4251920.477
9876.182 1917.159906.9381910.3779947.9471907.5579968.4521898.7949978.7041889.485
9988.9561884.769 9999.211882.51310009.491883.094 10019.61890.672 10029.71892.924
 10039.81892.533 10049.91897.594 10059.91898.645 10079.91905.93310120.071910.429
10150.321925.15210170.641932.81210190.961944.172 10231.81946.81610242.031955.016
10252.261958.00310272.721973.84810282.951976.86910293.171977.74810300.911980.768
#Mann= 3 , 0 , 0
9699.022    0.12       09699.022    0.12       010300.91    0.12       0
#XS Ineff= 2 , 0
       0                               0
Bank Sta=9699.022,10300.91
Exp/Cntr=0.3,0.1

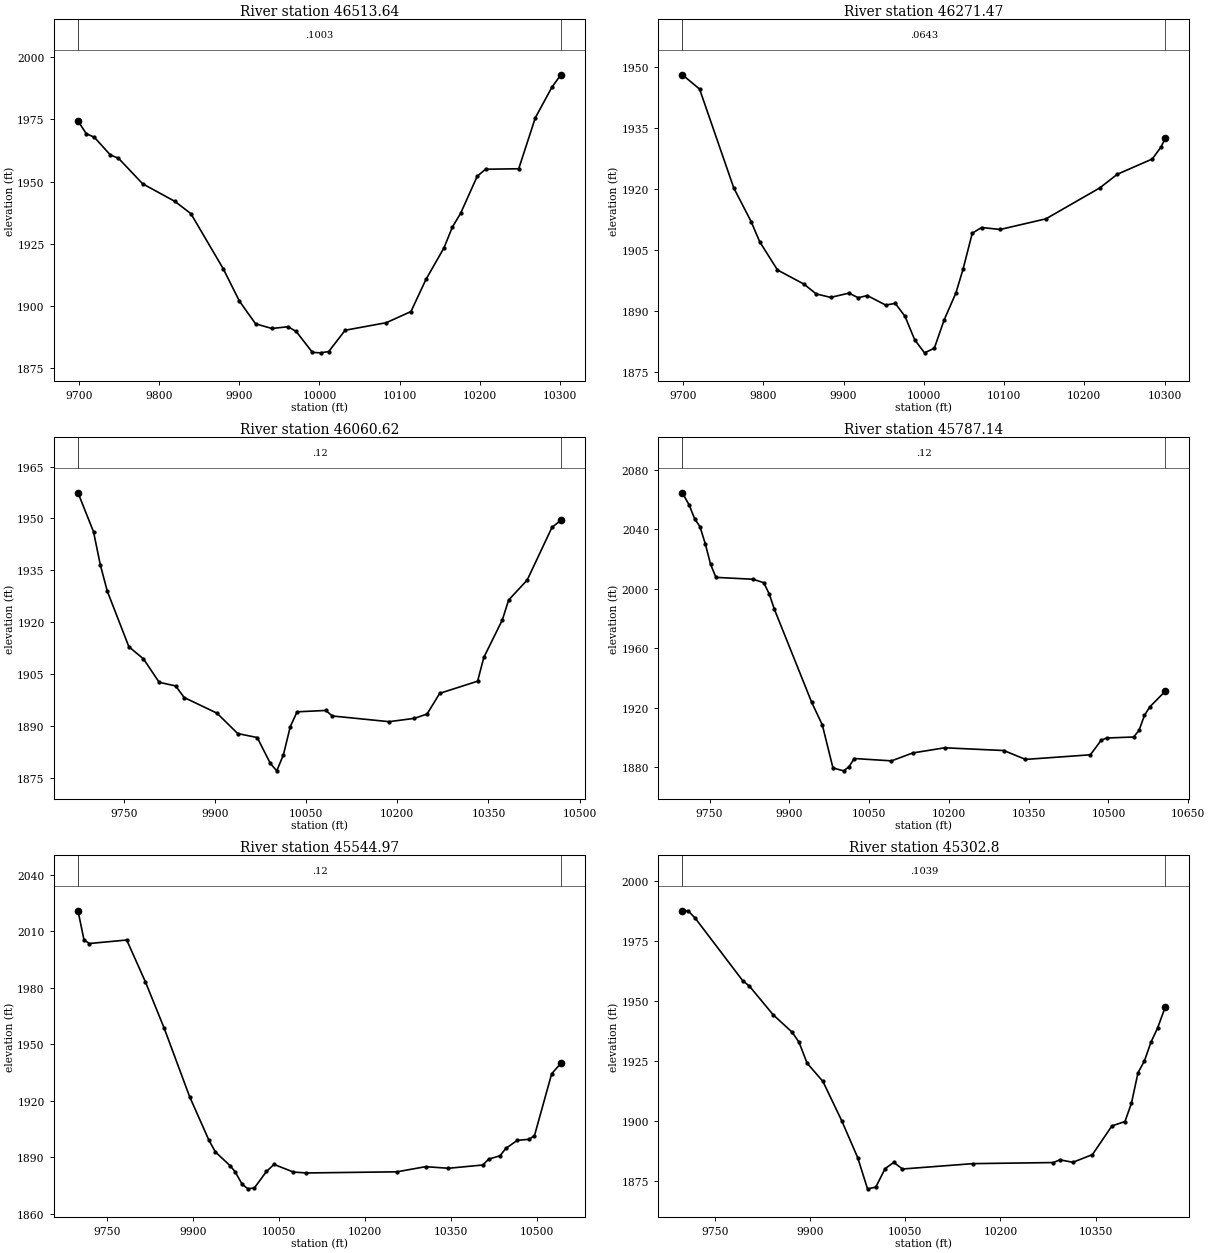
Type RM Length L Ch R = 1 ,46513.64,242.167800,242.167800,242.167800
XS GIS Cut Line= 6
698764.437918623 785125.31840521698777.041368726784965.745542995
698784.802985803784905.311147809698799.366277204784815.816169816
698826.277071299784696.786997224698869.420271117784534.165865658
#Sta/Elev= 30
9699.0121974.3659709.351 1969.269719.3721967.8469739.4121960.7039749.4331959.424
9779.507 1949.189819.6771942.1119839.7621937.1619880.014 1915.079900.1781902.087
9920.3441892.947 9940.611891.0689960.8751891.7629971.008 1889.869991.2741881.464
 10001.41881.28610011.541881.80310032.041890.356 10083.31893.38510114.061897.856
10132.731910.74610155.281923.45910165.621931.72610175.971937.30610196.661952.168
   10207    195510248.391955.18610269.081975.65310289.771987.92710300.981992.922
#Mann= 3 , 0 , 0
9699.012  0.1003       09699.012  0.1003       010300.98  0.1003       0
#XS Ineff= 2 , 0
       0                               0
Bank Sta=9699.012,10300.98
Exp/Cntr=0.3,0.1

Type RM Length L Ch R = 1 ,46271.47,210.855200,210.855200,210.855200
XS GIS Cut Line= 6
698891.138075746785165.178713928698924.698101368785075.974404023
698962.502014577784995.271784684 698996.88087852784933.186695416
699084.784745113784795.113124479699162.857396086784630.111272897
#Sta/Elev= 30
9699.0771948.0569720.4771944.535 9763.091920.2059784.6711911.9399795.4861906.929
9817.571 1900.01  9850.71896.5149865.8431894.1159883.8391893.264  9906.71894.312
9918.131 1893.189929.562 1893.719952.4231891.3729964.4071891.7929976.514 1888.59
 9988.621882.80810000.871879.61510013.061880.75210025.241887.69310040.021894.392
10048.75 1900.1410060.361909.06610071.981910.463 10095.21909.98110152.191912.604
10219.231920.20510241.051923.56110284.691927.329 10295.6 1930.2710300.931932.468
#Mann= 3 , 0 , 0
9699.077  0.0643       09699.077  0.0643       010300.93  0.0643       0
#XS Ineff= 2 , 0
       0                               0
Bank Sta=9699.077,10300.93
Exp/Cntr=0.3,0.1

Type RM Length L Ch R = 1 ,46060.62,273.480200,273.480200,273.480200
XS GIS Cut Line= 6
698954.967145473785237.869477734699006.232367754   785148.590296
699068.845066845785080.401380673699221.024816334785004.040950552
699299.502230197784729.308506981 699326.85546577784590.588526294
#Sta/Elev= 30
9674.9311957.4219700.4881946.1439711.6631936.5859723.049 1929.04 9758.581912.967
9782.6431909.4559808.4251902.6999835.3521901.6539849.7451898.2829903.4871893.783
 9937.621887.8959969.7731886.7449991.1751879.28310001.85 1877.1310012.791881.779
10024.011889.86910035.231894.17110082.59 1894.5710092.991892.97510186.591891.324
10228.191892.28810248.991893.53310269.791899.507 10332.11903.013 10342.31909.865
10372.871920.74910383.071926.43310413.641932.21810454.411947.427 10469.11949.496
#Mann= 3 , 0 , 0
9674.931    0.12       09674.931    0.12       0 10469.1    0.12       0
#XS Ineff= 2 , 0
       0                10078.36       0
Bank Sta=9674.931,10469.1
Exp/Cntr=0.3,0.1

Type RM Length L Ch R = 1 ,45787.14,242.167700,242.167700,242.167700
XS GIS Cut Line= 6
 699350.98460606785498.040836759699351.452479033785302.083362696
699349.136959622785159.228360319699350.406638874785130.841351983
699354.208701432784969.626219988699422.591790497784596.449933916
#Sta/Elev= 30
9699.0072064.4059712.048 2055.949722.0482046.8849732.0482041.6489742.048  2030.1
9752.0482016.2679762.0482007.5649832.0482006.3029852.0482003.9579862.0481996.572
9872.0481986.0349942.0581923.6189962.0621908.4249982.066 1879.5210002.071877.576
10012.071880.26410022.071885.85910092.111884.28110132.121889.59910192.131893.058
10303.39 1891.2210344.051885.25310466.051888.35210486.38 1898.1410496.551899.634
10547.381900.31410557.551904.78610567.721914.89210577.881920.58810606.911931.097
#Mann= 3 , 0 , 0
9699.007    0.12       09699.007    0.12       010606.91    0.12       0
#XS Ineff= 2 , 0
       0                10172.25       0
Bank Sta=9699.007,10606.91
Exp/Cntr=0.3,0.1

Type RM Length L Ch R = 1 ,45544.97,242.167700,242.167700,242.167700
XS GIS Cut Line= 6
699691.848587573785374.898985475699632.797836602785225.322520435
699526.534335613785023.699268967699488.662324071 784932.00848943
699478.883833289784894.152641922699483.159669399784578.865711033
#Sta/Elev= 30
 9699.042020.8889709.5722005.3189719.0922003.516 9784.052005.3659816.6561983.146
9849.3731958.5759893.8241922.1849927.4321899.1079938.7851892.8589964.394 1885.58
9972.8441882.4819985.5161875.6869995.551 1873.2810006.861873.80210027.881882.487
10040.941886.24910075.021882.18410097.461881.70910255.431882.31210305.431885.044
10345.441884.20110405.441885.93810415.441889.03110435.451890.84210445.451894.721
10465.45 1899.0210485.451899.55810495.451901.46510525.451934.35910541.591939.941
#Mann= 3 , 0 , 0
 9699.04    0.12       0 9699.04    0.12       010541.59    0.12       0
#XS Ineff= 2 , 0
       0                10141.25       0
Bank Sta=9699.04,10541.59
Exp/Cntr=0.3,0.1

Type RM Length L Ch R = 1 , 45302.8,242.167800,242.167800,242.167800
XS GIS Cut Line= 6
699917.945575237785223.880254164699839.164579868785046.291045964
699669.274431586784867.664788306699621.587611109784796.908828676
699600.324965447784754.650399879699559.357968658784573.004303396
#Sta/Elev= 30
9699.054 1987.499708.4611987.3799719.0551984.4789793.8711958.4449804.6711956.096
9841.9211944.2079871.9581936.9179882.7411932.7489895.5081924.0249920.369 1916.45
9949.9681900.0969975.1691884.7239990.6771871.70110003.641872.39210018.451880.141
10032.07 1882.7310045.68 1879.9610156.541882.19510283.461882.64710293.711883.781
10314.211882.75410344.971885.96410375.721897.90910396.221899.72610406.471907.396
10416.731919.98710426.981925.04310437.231932.80810447.481938.57410459.78 1947.49
#Mann= 3 , 0 , 0
9699.054  0.1039       09699.054  0.1039       010459.78  0.1039       0
#XS Ineff= 2 , 0
       0                10138.92       0
Bank Sta=9699.054,10459.78
Exp/Cntr=0.3,0.1

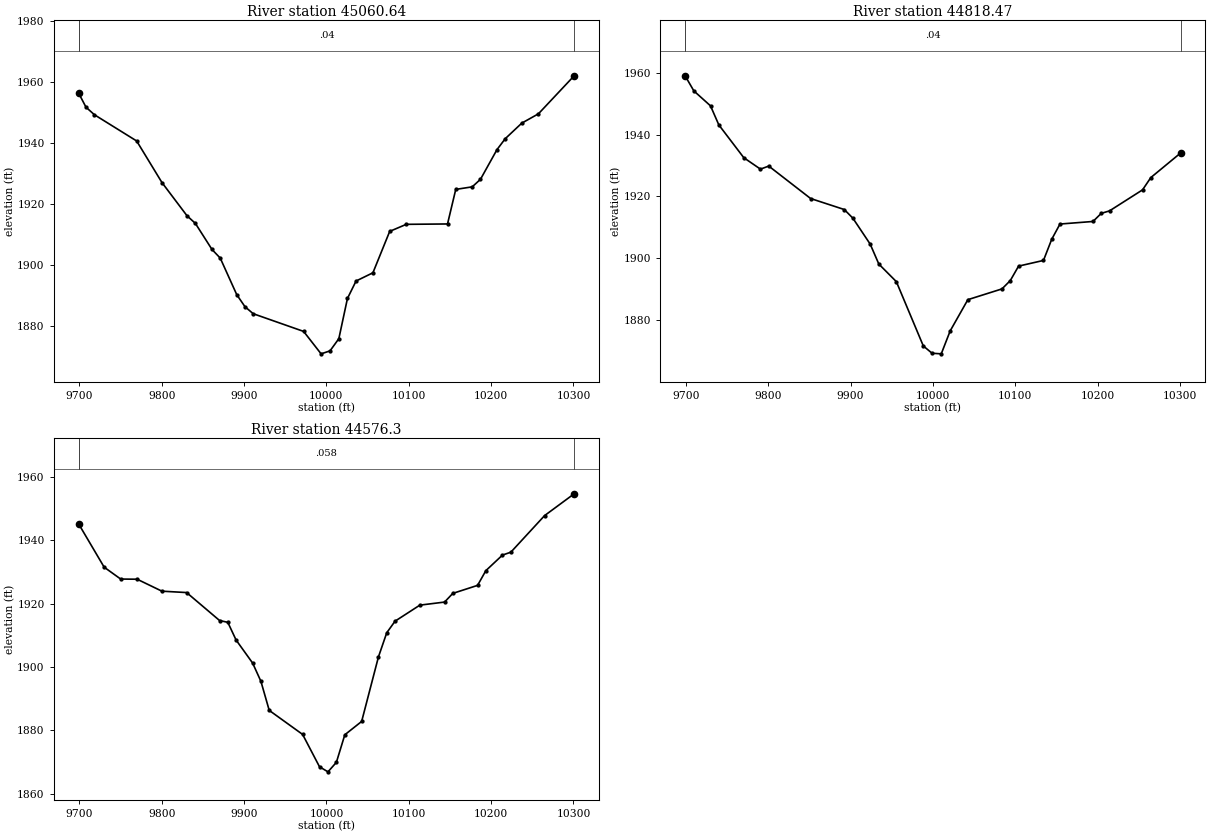
Type RM Length L Ch R = 1 ,45060.64,242.167700,242.167700,242.167700
XS GIS Cut Line= 6
699961.221834672785133.751731459699927.587260441784942.190900028
699932.836775558784886.495861844699960.379833434 784804.27838535
699971.414191741784739.272652778 699958.66126292  784541.9676268
#Sta/Elev= 30
9699.1021956.3989708.0731951.7559718.323 1949.289769.5721940.6799800.3211927.026
9830.7581916.1269840.8651913.6419861.0761905.0719871.0951902.2399891.1321890.239
9901.141 1886.289911.1451883.9859972.3541878.1789993.5651870.81810004.411871.793
10015.121875.78810025.581888.99410036.051894.72210056.521897.41810076.891911.008
10097.041913.32210147.121913.44510157.121924.78710177.121925.62510187.151928.105
10207.221937.85410217.261941.43910237.331946.539 10257.51949.58710300.941962.078
#Mann= 3 , 0 , 0
9699.102    0.04       09699.102    0.04       010300.94    0.04       0
#XS Ineff= 2 , 0
       0                               0
Bank Sta=9699.102,10300.94
Exp/Cntr=0.3,0.1

Type RM Length L Ch R = 1 ,44818.47,242.167700,242.167700,242.167700
XS GIS Cut Line= 6
700222.639566075785175.523498832700189.305722193784980.423231952
700172.726085992784930.110710778700138.014872044784849.488102662
700126.676593635784808.953214997700106.545017361784588.949775545
#Sta/Elev= 30
9699.0641958.9669709.7031954.0839729.9231949.2589740.0321943.1129770.3611932.519
 9790.581928.835 9800.69 1929.82 9851.511919.3489892.3991915.7949902.7881913.019
9923.8461904.6399934.3751898.1919955.6351892.5189988.4061871.753    99991869.406
10010.191869.21410021.031876.62310042.491886.70110083.911890.17310094.011892.855
 10104.11897.52910134.331899.36610144.361906.19810154.381911.11310194.481911.941
 10204.51914.55510214.531915.35910254.651922.144 10264.71926.10810300.921934.048
#Mann= 3 , 0 , 0
9699.064    0.04       09699.064    0.04       010300.92    0.04       0
#XS Ineff= 2 , 0
       0                               0
Bank Sta=9699.064,10300.92
Exp/Cntr=0.3,0.1

Type RM Length L Ch R = 1 , 44576.3,242.167700,242.167700,242.167700
XS GIS Cut Line= 6
700373.271338551785165.956262718700368.231201847784969.239552941
700398.262902025784807.896924282700404.101958532784740.347517511
 700399.15670975784662.933830581700377.979904682784570.249611447
#Sta/Elev= 30
9699.0711945.0839730.0841931.4459750.1221927.7099770.1591927.6529800.2151923.885
9830.2311923.4499870.2481914.6429880.2581914.0719890.2671908.5159910.391 1901.24
9920.4741895.4759930.5571886.3269971.1071878.7569991.6261868.563 10001.91866.967
10012.131869.96810022.361878.64110042.811882.84710063.221903.19110073.291910.787
10083.371914.43510113.481919.484 10143.51920.45410153.511923.18610183.591925.713
10193.651930.34910213.851935.26410224.021936.16910264.971947.69110300.921954.572
#Mann= 3 , 0 , 0
9699.071   0.058       09699.071   0.058       010300.92   0.058       0
#XS Ineff= 2 , 0
       0                               0
Bank Sta=9699.071,10300.92
Exp/Cntr=0.3,0.1