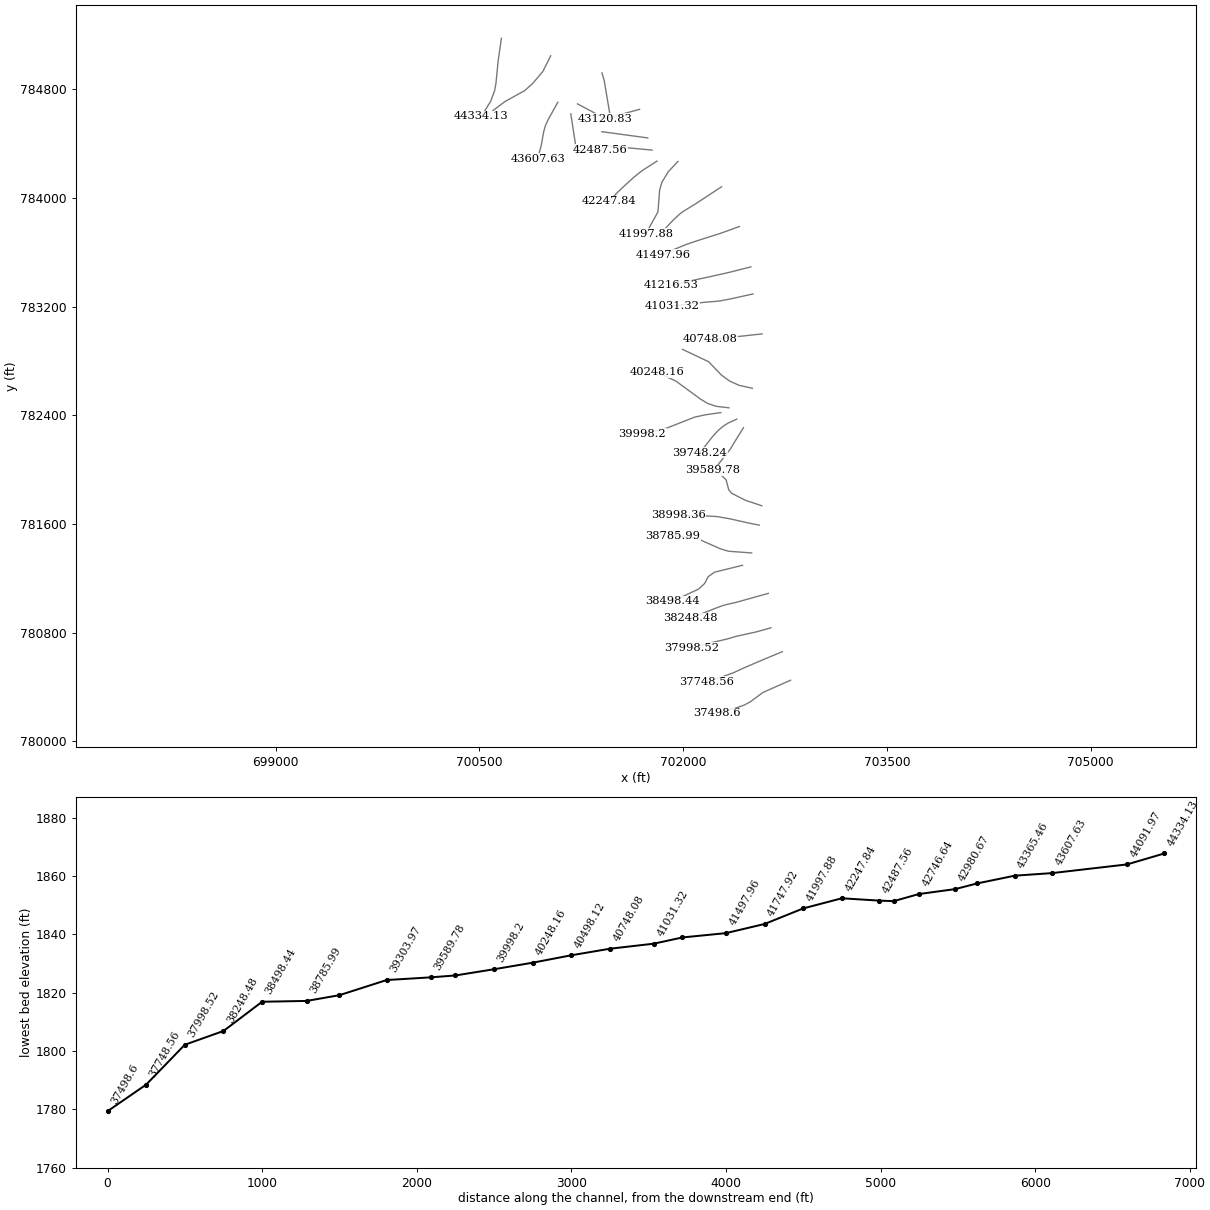
HEC-RAS study 14536_ras.prj: 14536

--- 14536_ras.g01 (geometry) --- (continued)

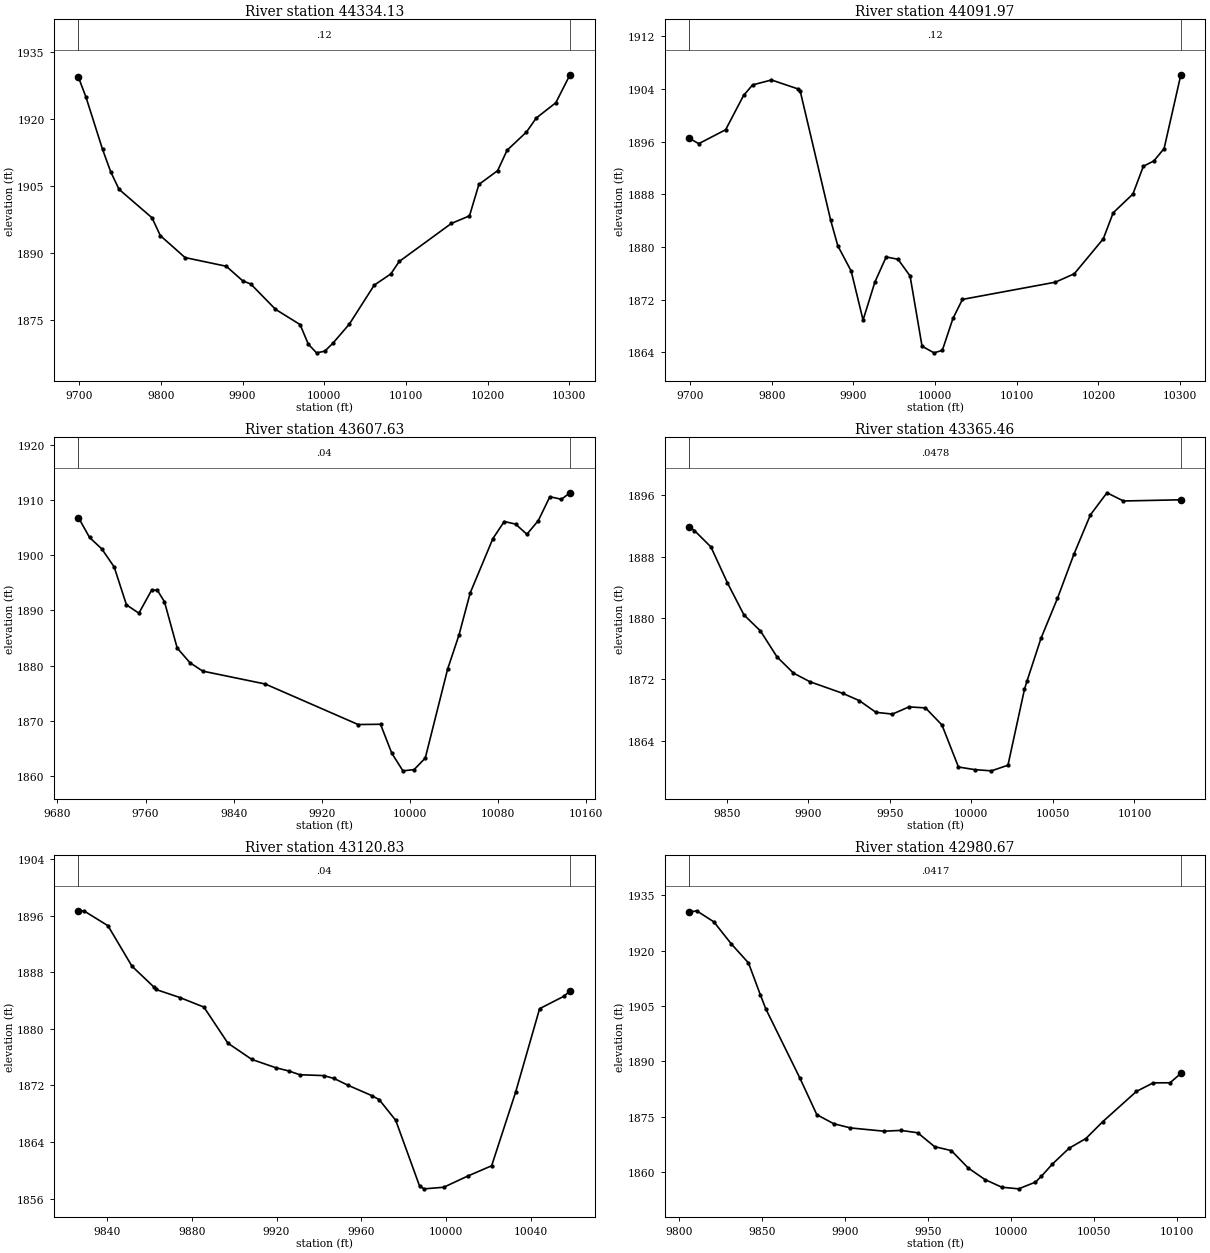
Type RM Length L Ch R = 1 ,44334.13,242.167700,242.167700,242.167700
XS GIS Cut Line= 6
700662.475440979785174.215879606700638.841856566785009.393438108
700622.209312502 784841.26275871700612.524783597784788.797515502
700584.065029732784711.633284485700515.489907527784600.457524087
#Sta/Elev= 30
9699.0271929.3339708.337 1924.849728.5421913.2059738.6441908.1329748.7461904.265
9789.1561897.8959799.2581893.9199829.5651889.0039880.0011887.062  9900.1 1883.82
 9910.151883.076  9940.31877.4349970.4491874.0169980.4991869.6289990.5491867.699
10000.591868.06110010.641869.85710030.731874.12610061.191882.83410081.531885.346
10091.811888.12710155.651896.63310177.841898.32810189.34 1905.3510212.341908.441
10223.841912.98510247.651917.08510259.61 1920.2110283.521923.61410300.911929.876
#Mann= 3 , 0 , 0
9699.027    0.12       09699.027    0.12       010300.91    0.12       0
#XS Ineff= 2 , 0
       0                               0
Bank Sta=9699.027,10300.91
Exp/Cntr=0.3,0.1

Type RM Length L Ch R = 1 ,44091.97,484.335500,484.335500,484.335500
XS GIS Cut Line= 6
701025.502033254785045.599035221 700967.58673464784930.354599269
 700894.38631253784843.794175265700833.505170194784788.874898216
700690.722931343784709.994011393700599.444199872784642.052496393
#Sta/Elev= 30
9699.1171896.512 9710.741895.692 9743.641897.8069765.5721903.0089776.6291904.614
 9799.761905.3649832.6151903.9899834.921 1903.689872.2251884.0679880.9521880.186
9897.336 1876.349911.8721868.9059926.3961874.6919940.1751878.4939954.6641878.133
 9969.411875.6089984.0811864.9329998.7531863.92810008.911864.30310021.911869.145
10033.521872.04210147.291874.65710170.461875.93610205.991881.24410218.071885.194
10242.231888.04610255.011892.25910267.911893.07210280.421894.953 10300.91906.153
#Mann= 3 , 0 , 0
9699.117    0.12       09699.117    0.12       0 10300.9    0.12       0
#XS Ineff= 2 , 0
       09967.827                       0
Bank Sta=9699.117,10300.9
Exp/Cntr=0.3,0.1

Type RM Length L Ch R = 1 ,43607.63,242.167700,242.167700,242.167700
XS GIS Cut Line= 6
701078.064276161784704.046646324 701007.29316029784576.346949883
700986.813930818784532.119609498700974.214035649784488.142467638
700956.577827706784388.932991289700929.627842698784287.604082807
#Sta/Elev= 30
9699.1131906.8239709.2151903.2249720.3821901.1389731.5491897.8859742.7151891.019
9753.9831889.507 9765.581893.6979770.727 1893.679777.1771891.5989788.7731883.195
 9800.371880.5329811.9661879.0169868.718 1876.689953.0331869.3429973.3541869.388
9983.5151864.1779993.6761860.95510003.821861.17510013.971863.26910034.291879.394
10044.491885.49710054.781893.18210075.361903.01910085.651906.11310095.941905.646
10106.231903.80310116.581906.27210127.081910.60410137.591910.14110145.361911.317
#Mann= 3 , 0 , 0
9699.113    0.04       09699.113    0.04       010145.36    0.04       0
#XS Ineff= 2 , 0
       0                               0
Bank Sta=9699.113,10145.36
Exp/Cntr=0.3,0.1

Type RM Length L Ch R = 1 ,43365.46,244.629100,244.629100,244.629100
XS GIS Cut Line= 2
701173.511455595784618.138840094701219.344788909784320.222173437
#Sta/Elev= 29
9827.0211891.9069830.1961891.4169840.3141889.2769850.4321884.5869860.549 1880.41
9870.6671878.3199880.7851874.9439890.9021872.816 9901.02 1871.699921.2551870.165
9931.3731869.2149941.4911867.6969951.608 1867.479961.7261868.4079971.8441868.278
9981.9611866.0499992.0791860.564 10002.21860.21710012.311860.06410022.431860.796
10032.551870.697 10034.1 1871.7710042.671877.34810052.781882.569 10062.91888.343
10073.021893.47610083.141896.34710093.261895.27610128.441895.432
#Mann= 3 , 0 , 0
9827.021  0.0478       09827.021  0.0478       010128.44  0.0478       0
#XS Ineff= 2 , 0
       0                               0
Bank Sta=9827.021,10128.44
Exp/Cntr=0.3,0.1

Type RM Length L Ch R = 1 ,43120.83,140.158700,140.158700,140.158700
XS GIS Cut Line= 2
701222.687671393784691.648373783701427.678122282784582.722173437
#Sta/Elev= 28
9826.4511896.681 9829.071896.6649840.394 1894.579851.7181888.8559861.9311885.953
9863.0421885.5619874.3661884.421 9885.691883.0739897.014 1877.989908.3381875.675
9919.6631874.5019925.864 1874.049930.9871873.5139942.3111873.3919947.1751872.984
9953.6351872.0419964.9591870.5659968.4861869.9939976.2831867.0689987.6071857.734
9989.7971857.3899998.9311857.61310010.261859.18910021.58 1860.65 10032.91871.044
10044.231882.84710055.55 1884.5810058.581885.332
#Mann= 3 , 0 , 0
9826.451    0.04       09826.451    0.04       010058.58    0.04       0
#XS Ineff= 2 , 0
       0                               0
Bank Sta=9826.451,10058.58
Exp/Cntr=0.3,0.1

Type RM Length L Ch R = 1 ,42980.67,234.033200,234.033200,234.033200
XS GIS Cut Line= 3
701402.807697833784919.232461229701419.560619414784862.792148635
701458.928122282784628.555506781
#Sta/Elev= 30
9806.0441930.3899810.4591930.798 9820.891927.7929831.3221921.8579841.7531916.668
9848.8911908.0329852.1841904.228 9872.821885.394 9882.961875.554  9893.11873.114
9903.2411871.9669923.5211871.0829933.661  1871.39943.802 1870.659953.9421866.901
9964.0821865.8199974.2221861.1189984.363 1857.979994.5031855.90610004.641855.466
10014.781857.28410018.411858.89510024.921862.14410035.061866.466 10045.21869.097
10055.341873.65510075.621881.84510085.771884.17910095.911884.19710102.441886.718
#Mann= 3 , 0 , 0
9806.044  0.0417       09806.044  0.0417       010102.44  0.0417       0
#XS Ineff= 2 , 0
       0                               0
Bank Sta=9806.044,10102.44
Exp/Cntr=0.3,0.1

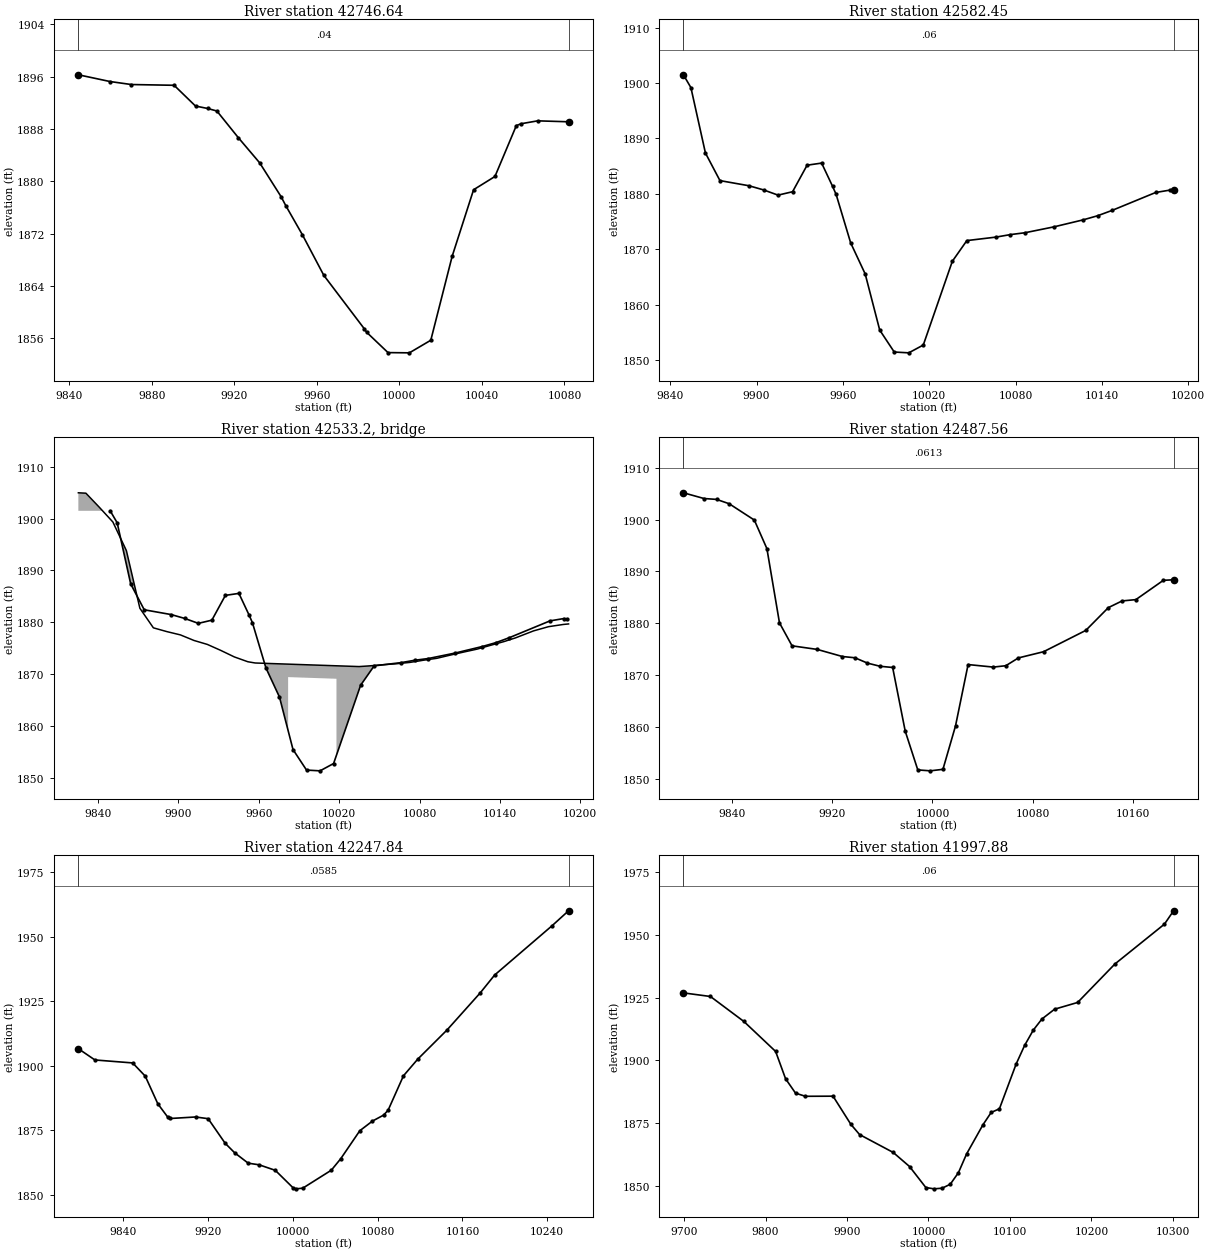
Type RM Length L Ch R = 1 ,42746.64,164.192400,164.192400,164.192400
XS GIS Cut Line= 2
701679.761455566784651.472173452701450.594788909784588.972173423
#Sta/Elev= 25
9844.4391896.305 9859.741895.2759870.1051894.8139890.8351894.6989901.2011891.525
9907.0431891.1549911.5661890.7649921.9311886.6959932.2961882.8399942.6621877.672
9945.0491876.2349953.0271871.8239963.3921865.6269983.0551857.4379984.1231856.932
9994.4881853.81710004.851853.78210015.221855.70810025.581868.55310035.951878.722
10046.311880.75310056.681888.54110059.071888.82410067.041889.26110081.981889.116
#Mann= 3 , 0 , 0
9844.439    0.04       09844.439    0.04       010081.98    0.04       0
#XS Ineff= 2 , 0
       0                               0
Bank Sta=9844.439,10081.98
Exp/Cntr=0.3,0.1

Type RM Length L Ch R = 1 ,42582.45,94.890500,94.890500,94.890500
XS GIS Cut Line= 3
701740.178122222784441.055506766701402.678122252784486.888840094
701402.673102081784486.873662785
#Sta/Elev= 30
9849.1931901.4839854.418 1899.17 9864.511887.3769874.602  1882.49894.7851881.473
9904.8771880.7259914.9691879.7829925.0611880.3969935.1531885.1799945.244 1885.56
9952.8171881.3929955.3361879.9049965.4281871.171 9975.521865.5719985.6111855.451
9995.7031851.491 10005.81851.34510015.891852.75310036.071867.85210046.161871.586
10066.351872.21210076.441872.66610086.531872.99910106.711874.062 10126.91875.318
10136.991876.06110147.081877.02710177.361880.25910187.451880.69710189.811880.618
#Mann= 3 , 0 , 0
9849.193    0.06       09849.193    0.06       010189.81    0.06       0
#XS Ineff= 2 , 0
       0                               0
Bank Sta=9849.193,10189.81
Exp/Cntr=0.3,0.1

Type RM Length L Ch R = 3 , 42533.2,,,
BEGIN DESCRIPTION:
END DESCRIPTION:
Bridge Culvert--1,0,-1,-1, 0
Deck Dist Width WeirC Skew NumUp NumDn MinLoCord MaxHiCord MaxSubmerge Is_Ogee
20.870500,53.149500,2.6,0, 41, 41, , , 0.95, 0, 0,0,,
 9825.45 9831.08 9841.15 9851.22 9861.29 9871.35 9881.42 9891.49 9901.56 9909.13
 9911.63 9921.70 9931.77 9941.84 9951.91 9957.40 9981.96 9981.9610018.0410018.04
10034.8910042.5310052.6010062.6610072.7310080.3010082.8010092.8710102.9410113.01
10123.0810133.1510143.2210146.3910151.6310154.0010165.1010174.6010176.2110187.32
10191.22
 1904.96 1904.88 1902.15 1899.32 1893.81 1882.69 1878.92 1878.19 1877.56 1876.76
 1876.49 1875.72 1874.56 1873.31 1872.38 1872.14 1871.92 1871.92 1871.60 1871.60
 1871.45 1871.58 1871.80 1871.99 1872.25 1872.56 1872.67 1873.04 1873.66 1874.25
 1874.82 1875.56 1876.28 1876.55 1876.98 1877.22 1878.33 1879.02 1879.14 1879.57
 1879.67
  904.96  904.88  902.15  899.32  893.81  882.69  878.92  878.19  877.56  876.76
  876.49  875.72  874.56  873.31  872.38  872.14  871.92 1869.42 1869.10  871.60
  871.45  871.58  871.80  871.99  872.25  872.56  872.67  873.04  873.66  874.25
  874.82  875.56  876.28  876.55  876.98  877.22  878.33  879.02  879.14  879.57
  879.67
 9825.45 9831.08 9841.15 9851.22 9861.29 9871.35 9881.42 9891.49 9901.56 9909.13
 9911.63 9921.70 9931.77 9941.84 9951.91 9957.40 9981.96 9981.9610018.0410018.04
10034.8910042.5310052.6010062.6610072.7310080.3010082.8010092.8710102.9410113.01
10123.0810133.1510143.2210146.3910151.6310154.0010165.1010174.6010176.2110187.32
10191.22
 1904.96 1904.88 1902.15 1899.32 1893.81 1882.69 1878.92 1878.19 1877.56 1876.76
 1876.49 1875.72 1874.56 1873.31 1872.38 1872.14 1871.92 1871.92 1871.60 1871.60
 1871.45 1871.58 1871.80 1871.99 1872.25 1872.56 1872.67 1873.04 1873.66 1874.25
 1874.82 1875.56 1876.28 1876.55 1876.98 1877.22 1878.33 1879.02 1879.14 1879.57
 1879.67
  904.96  904.88  902.15  899.32  893.81  882.69  878.92  878.19  877.56  876.76
  876.49  875.72  874.56  873.31  872.38  872.14  871.92 1869.42 1869.10  871.60
  871.45  871.58  871.80  871.99  872.25  872.56  872.67  873.04  873.66  874.25
  874.82  875.56  876.28  876.55  876.98  877.22  878.33  879.02  879.14  879.57
  879.67
BR Coef=-1 , 0 , 0 ,, 0 ,,,0.8,0,1,0,
WSPro=,,,, 1 ,,,, 0 ,,,, 0 ,,,,-1 ,-1 ,-1 , 0 , 0 , 0 , 0 , 0
BC Design=,, 0 ,, 0 ,,,,,,

Type RM Length L Ch R = 1 ,42487.56,239.718000,239.718000,239.718000
XS GIS Cut Line= 3
701771.428122222784351.472173437701451.396963865784381.663792178
 701387.57559675784352.567064375
#Sta/Elev= 30
9801.0651905.1559817.5661904.047 9827.611903.8779837.6541903.0399857.7431899.892
9867.7881894.3799877.8321880.0589887.8761875.6379907.9651874.9469928.0541873.578
9938.0981873.3349948.143  1872.39958.1871871.6939968.2321871.4629978.2761859.185
9988.3211851.7069998.3651851.52710008.411851.82110018.451860.182 10028.51872.025
10048.591871.53710058.63  1871.810068.681873.30510088.761874.49710122.521878.611
10140.541883.00510151.531884.29610162.521884.548 10184.51888.27210192.661888.375
#Mann= 3 , 0 , 0
9801.065  0.0613       09801.065  0.0613       010192.66  0.0613       0
#XS Ineff= 2 , 0
       0                               0
Bank Sta=9801.065,10192.66
Exp/Cntr=0.3,0.1

Type RM Length L Ch R = 1 ,42247.84,249.959800,249.959800,249.959800
XS GIS Cut Line= 6
 701808.15826043784270.461403871701698.910274366784200.503014974
701639.636231512784153.136561606701578.328560043784097.961681591
701511.338247147784034.019505498701456.035387725783973.474083929
#Sta/Elev= 30
9797.5081906.6459813.133 1902.289848.757 1901.139860.6311896.0149872.5061885.291
9881.8091880.153 9884.381879.591 9908.131880.1799920.004 1879.529936.064 1869.99
9945.0251866.3039957.8141862.2689968.1481861.6399983.3911859.49710000.211852.703
10003.111852.32210009.351852.58710036.261859.54410045.171864.00310063.161874.847
10075.071878.58410085.591880.89910089.881882.80510104.361896.14110117.841902.593
10145.491913.90510176.781928.26110190.421935.20310244.591954.301 10260.21960.112
#Mann= 3 , 0 , 0
9797.508  0.0585       09797.508  0.0585       0 10260.2  0.0585       0
#XS Ineff= 2 , 0
       0                               0
Bank Sta=9797.508,10260.2
Exp/Cntr=0.3,0.1

Type RM Length L Ch R = 1 ,41997.88,249.959800,249.959800,249.959800
XS GIS Cut Line= 6
701962.698660824784268.179348065701891.696311143784192.881042271
701844.216995159784115.205544949701827.414125628 784057.25110073
701814.951577186783896.347158645701726.223285395783735.918347683
#Sta/Elev= 30
 9699.151926.9239732.3751925.4849773.4161915.5319812.3671903.5959824.5911892.704
9836.8141886.9759848.9031885.7239882.8621885.7699904.7961874.5259915.4241870.476
9956.6951863.3549976.7421857.7519996.7511849.37710006.761848.85110016.761849.107
10026.771850.68210036.771855.28210046.781862.737 10066.91874.37910076.991879.286
10087.091880.73210107.681898.61710118.021905.98310128.651912.07410139.281916.517
10154.851920.42610183.121923.10910228.921938.44610289.681954.314 10300.91959.633
#Mann= 3 , 0 , 0
 9699.15    0.06       0 9699.15    0.06       0 10300.9    0.06       0
#XS Ineff= 2 , 0
       0                               0
Bank Sta=9699.15,10300.9
Exp/Cntr=0.3,0.1

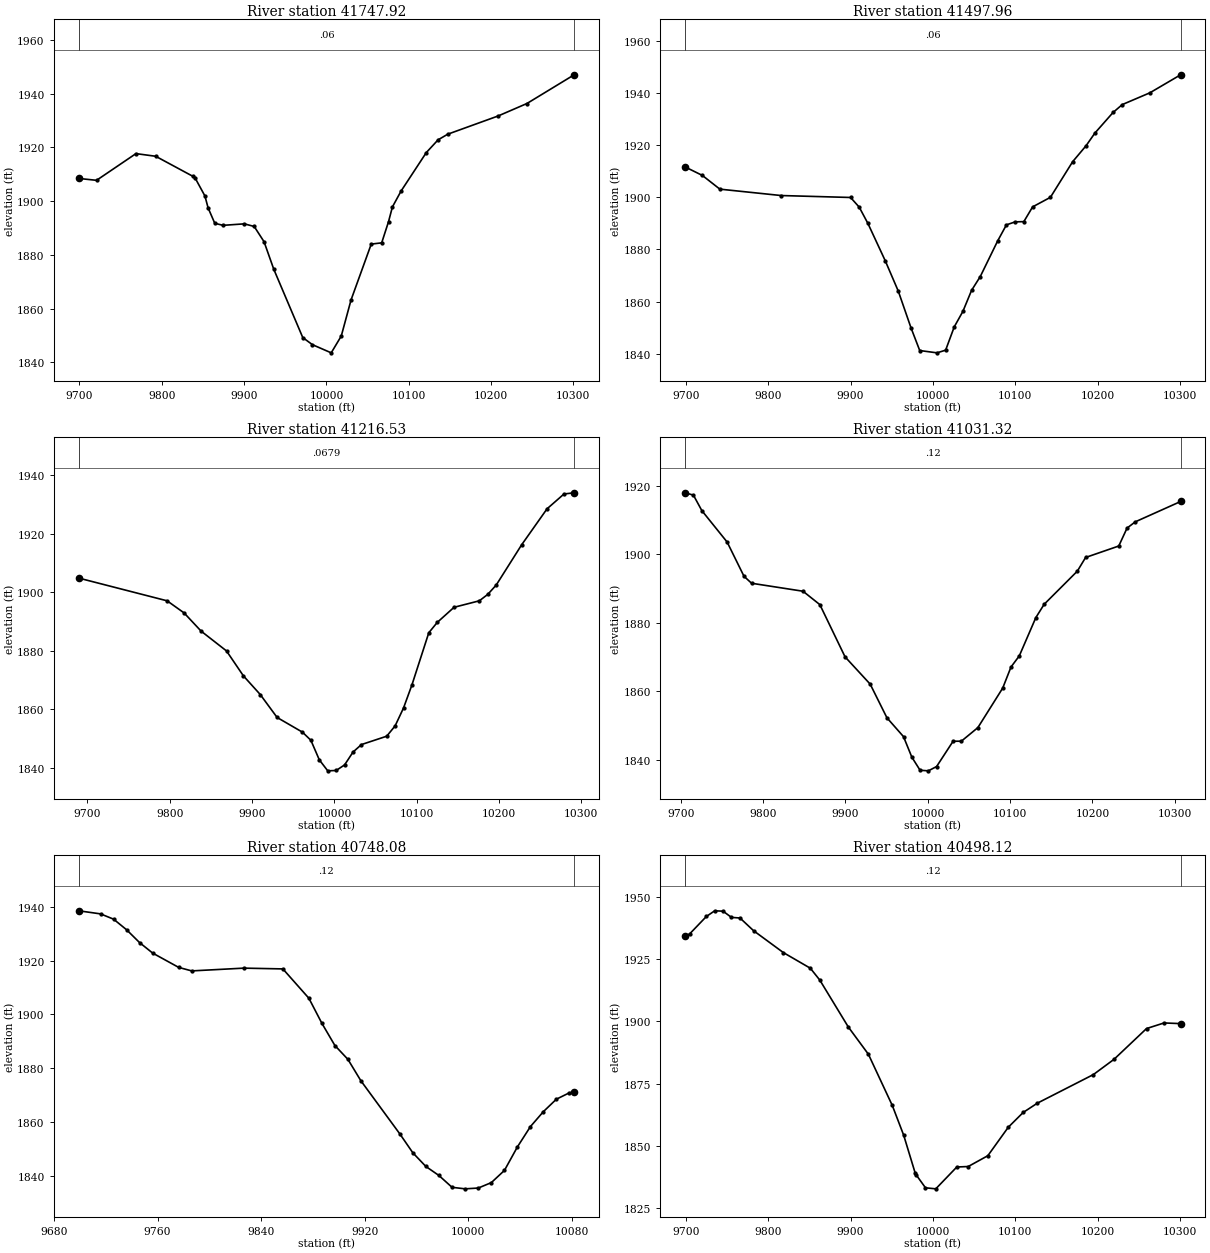
Type RM Length L Ch R = 1 ,41747.92,249.959800,249.959800,249.959800
XS GIS Cut Line= 6
702283.175046207784081.432541695702092.521054157783956.014166851
702008.059908921783904.503535597701980.228009037783884.695949937
701930.108836883783839.031441267 701811.63998008783713.233628972
#Sta/Elev= 30
9699.0141908.4689720.769 1907.769768.6481917.7089792.5871916.7229838.0881909.206
9840.4661908.6539852.4361901.9279856.2841897.4879864.4051891.7539874.4791890.997
9900.3151891.5499912.2841890.5749924.254 1884.89 9936.051874.6529971.2661849.208
9983.0041846.55210005.841843.51210018.051849.77410029.911863.19810054.461884.013
10067.14 1884.4710075.421892.32910080.181897.85810090.751903.79510121.361918.102
10135.611922.83210147.431924.94510208.54 1931.7210243.591936.36910300.961947.067
#Mann= 3 , 0 , 0
9699.014    0.06       09699.014    0.06       010300.96    0.06       0
#XS Ineff= 2 , 0
       0                               0
Bank Sta=9699.014,10300.96
Exp/Cntr=0.3,0.1

Type RM Length L Ch R = 1 ,41497.96,281.434500,281.434500,281.434500
XS GIS Cut Line= 6
702414.720307158783789.011072771702279.193208199783739.961802003
702090.179288698783679.727017089702019.201459762783655.202061378
701936.694898684 783621.31632318701851.527255499783578.904274435
#Sta/Elev= 30
9699.0161911.5919719.988 1908.339741.2571903.0769815.701 1900.63 9900.041899.886
9910.5391896.1749921.0371889.9729942.0341875.7259957.9681864.031 9973.531849.873
9984.0281841.26210005.011840.381 10015.51841.40610025.981850.34310036.471856.271
10047.011864.31510057.591869.61410078.751883.28210089.331889.39910099.91 1890.54
10110.491890.63910121.161896.28610142.781899.947 10169.81913.59510186.031919.679
10196.841924.56710218.881932.44810230.051935.46410263.571939.97110300.961946.882
#Mann= 3 , 0 , 0
9699.016    0.06       09699.016    0.06       010300.96    0.06       0
#XS Ineff= 2 , 0
       0                               0
Bank Sta=9699.016,10300.96
Exp/Cntr=0.3,0.1

Type RM Length L Ch R = 1 ,41216.53,185.203800,185.203800,185.203800
XS GIS Cut Line= 6
702499.218215015783491.738095594702338.863883569783451.113758711
702207.581830415783421.560725023702205.629665308783421.125924613
702023.570483688783381.998612902701912.984711859783355.247148388
#Sta/Elev= 30
9689.256  1904.89796.7671897.0199817.3981892.876 9838.031886.6639868.887 1879.89
9889.387 1871.389909.8881864.9869930.3881857.1399961.1391852.1219971.3891849.347
 9981.641842.6549991.8871838.89710002.121839.02110012.341840.92510022.571845.312
 10032.81847.87510063.491850.73510073.711854.25810083.941860.38510094.171868.282
10114.631886.10210124.861889.62510145.311894.808   101761897.02210186.281899.219
10196.571902.42410227.431916.172 10258.31928.47810278.871933.53810291.241933.955
#Mann= 3 , 0 , 0
9689.256  0.0679       09689.256  0.0679       010291.24  0.0679       0
#XS Ineff= 2 , 0
       0                               0
Bank Sta=9689.256,10291.24
Exp/Cntr=0.3,0.1

Type RM Length L Ch R = 1 ,41031.32,283.241100,283.241100,283.241100
XS GIS Cut Line= 6
702514.874985892783292.347759673702342.818459745783254.504331936
702274.142982468783241.587257714702241.241719502783237.624878792
 702159.35610409783231.391043179701920.335344264783203.409467037
#Sta/Elev= 30
9705.2261917.9189715.337 1917.239725.5761912.7079756.2931903.5339776.7711893.551
9785.983 1891.519848.4441889.1859868.9221885.2729899.5261870.0349930.0521862.071
9950.4031852.2479970.5561846.7399980.6281840.7749990.6711836.936 10000.71836.764
10010.721838.01310030.781845.40510040.811845.41610060.881849.38110091.061860.917
10101.131867.073 10111.21870.31410131.331881.504 10141.41885.37210181.671895.037
10191.741899.03710232.02 1902.3810242.081907.60710252.151909.44810307.191915.375
#Mann= 3 , 0 , 0
9705.226    0.12       09705.226    0.12       010307.19    0.12       0
#XS Ineff= 2 , 0
       0                               0
Bank Sta=9705.226,10307.19
Exp/Cntr=0.3,0.1

Type RM Length L Ch R = 1 ,40748.08,249.959800,249.959800,249.959800
XS GIS Cut Line= 6
702581.849777916782998.351490285702432.928003045 782981.95587585
702308.457620997782970.351735108702254.294882145782961.877087754
702216.797180718782959.346253298702201.232485353782959.005624624
#Sta/Elev= 30
9699.0131938.5149715.9651937.3589726.025 1935.399736.0861931.4399746.146 1926.65
9756.2071922.7699776.3271917.4389786.3881916.139 9826.63 1917.179856.7971916.879
9876.8841905.9629886.9271896.6379896.9711888.3789907.0141883.2369917.0571875.253
9947.1881855.4519957.2311848.4249967.2741843.3579977.3451840.0059987.4661835.606
9997.5871835.03710007.721835.33310017.841837.35910027.96  1841.910037.981850.648
10048.011858.19210058.031863.76310068.05 1868.3910078.051870.76410081.821871.138
#Mann= 3 , 0 , 0
9699.013    0.12       09699.013    0.12       010081.82    0.12       0
#XS Ineff= 2 , 0
       0                               0
Bank Sta=9699.013,10081.82
Exp/Cntr=0.3,0.1

Type RM Length L Ch R = 1 ,40498.12,249.959800,249.959800,249.959800
XS GIS Cut Line= 6
702510.432708843 782597.97988002702414.085888957782619.255280767
702344.459992381782650.083837771702282.705369021782694.855703394
702188.198302892782793.413752646701996.137080533782884.457746898
#Sta/Elev= 30
9699.1311934.1599704.6471935.0789724.955 1942.079735.1091944.3649745.2631944.197
9755.4171941.7119765.8011941.4679782.2431936.3819818.3471927.6149851.2191921.312
9862.7311916.5489897.2921897.7549921.7181886.8029950.7591866.2349964.5671854.318
9978.3761839.2999980.1011838.2429991.0551833.20710003.561832.79410029.081841.557
10042.931841.74810066.781846.08910091.581857.50310109.72 1863.4510126.921867.172
10194.981878.65110220.021884.76710259.461897.10210280.781899.358 10300.91899.088
#Mann= 3 , 0 , 0
9699.131    0.12       09699.131    0.12       0 10300.9    0.12       0
#XS Ineff= 2 , 0
       0                               0
Bank Sta=9699.131,10300.9
Exp/Cntr=0.3,0.1

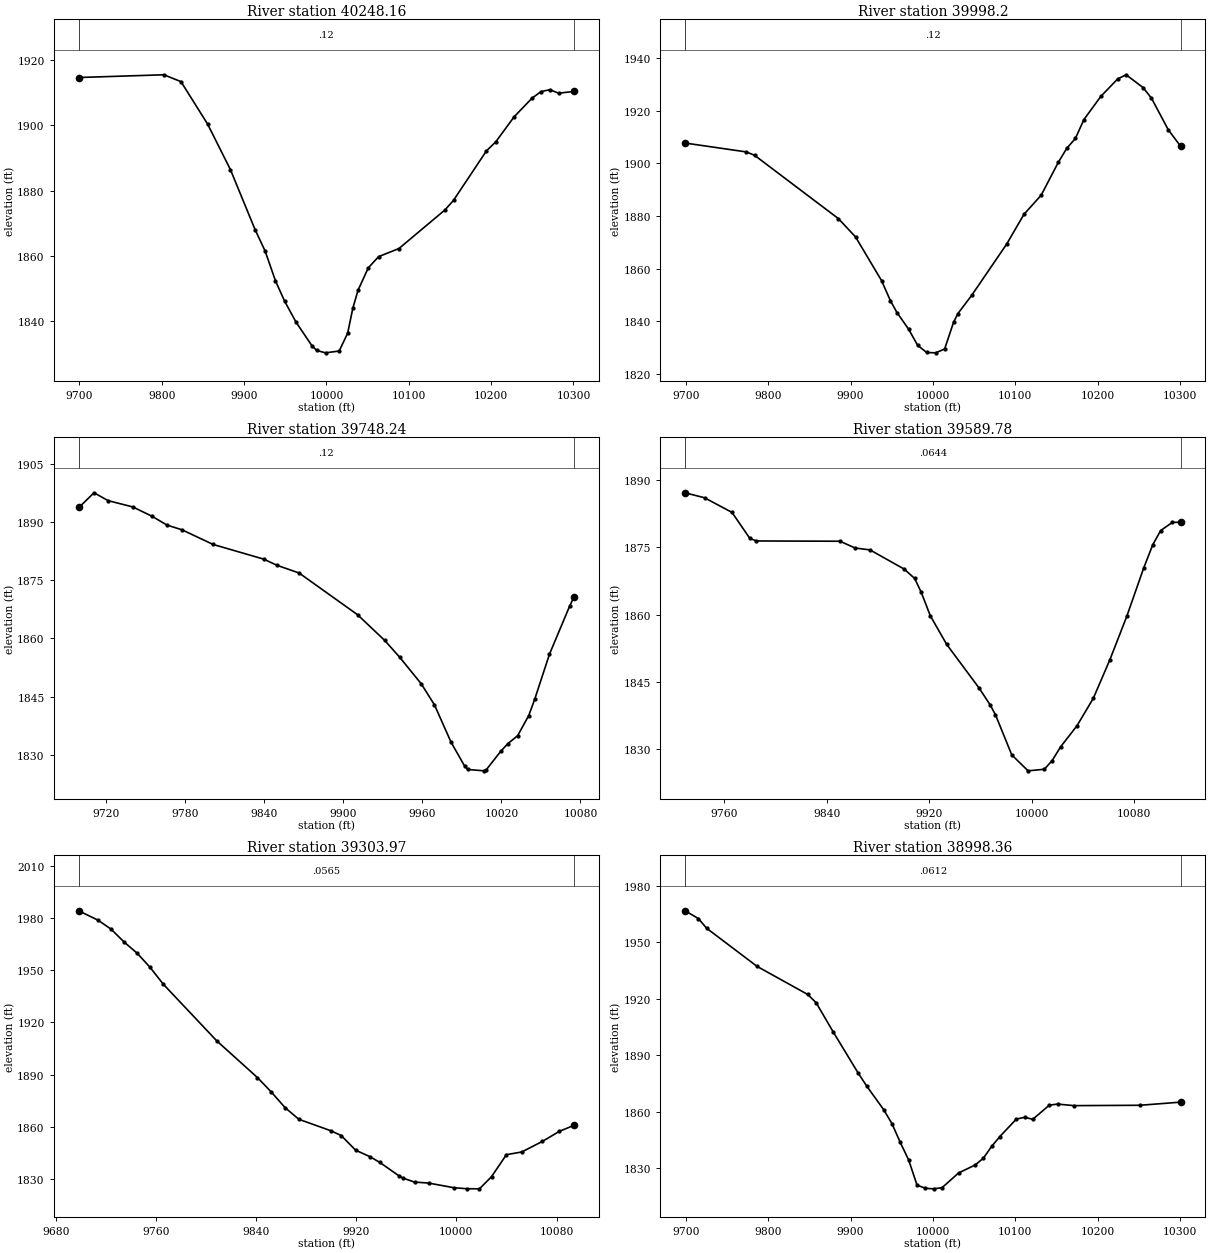
Type RM Length L Ch R = 1 ,40248.16,249.959900,249.959900,249.959900
XS GIS Cut Line= 6
702337.364217235782454.227492543702242.982369646782465.208148985
702181.711896197782486.334136568702129.395445276  782517.4314618
701948.689280227782649.853537471701807.586540463782717.695356792
#Sta/Elev= 30
9699.074 1914.699802.5171915.5319823.3421913.4369855.6231900.458 9883.391886.471
9913.3681868.0469925.5381861.4979938.067 1852.399949.1891846.1349963.1271839.663
9982.383 1832.459988.1861830.979 9998.981830.24810015.53 1830.8110025.811836.268
10032.091843.89310038.361849.39510050.91 1856.3310063.451859.75610088.131862.241
10144.121874.10510154.391877.02410194.441892.20310205.641894.93310228.031902.644
10249.661908.32510260.481910.35510271.291910.95810282.111909.88410300.951910.435
#Mann= 3 , 0 , 0
9699.074    0.12       09699.074    0.12       010300.95    0.12       0
#XS Ineff= 2 , 0
       0                               0
Bank Sta=9699.074,10300.95
Exp/Cntr=0.3,0.1

Type RM Length L Ch R = 1 , 39998.2,249.959800,249.959800,249.959800
XS GIS Cut Line= 6
702278.477638113782419.286762264702165.889056967782402.922031126
702086.578496382 782386.09196296701884.015593257782306.407758032
 701807.70023465 782285.01981058701700.290170345782261.826682158
#Sta/Elev= 30
9699.0781907.7429773.3281904.3769783.4331903.0939885.3181879.0069906.1051872.057
9937.6591855.472 9948.55 1847.769956.4161843.3149970.509 1837.029981.4891830.879
9992.468 1828.1410003.391828.00310014.291829.45510025.191839.64510030.381842.906
10047.041849.799 10089.5 1869.2710110.761880.69510131.561887.90810152.331900.395
10162.721905.766 10173.11909.47810183.491916.67810204.061925.49310224.521932.124
10234.751933.69110255.211928.85110265.441924.849 10285.91912.80210300.951906.519
#Mann= 3 , 0 , 0
9699.078    0.12       09699.078    0.12       010300.95    0.12       0
#XS Ineff= 2 , 0
       0                               0
Bank Sta=9699.078,10300.95
Exp/Cntr=0.3,0.1

Type RM Length L Ch R = 1 ,39748.24,158.459900,158.459900,158.459900
XS GIS Cut Line= 6
702395.822349535782371.403221891702328.167169953782339.975675252
702295.420782311782318.626099698702259.945426571782288.902149249
702218.763559515782244.044543916702122.595262049782122.299258963
#Sta/Elev= 30
9699.107 1893.919699.994 1893.969710.7741897.5339721.5551895.4989740.2531893.882
9754.932 1891.46 9766.121889.2159777.5451887.9929801.1841884.2179839.4961880.444
9849.6421878.846 9866.451876.856 9910.811866.1099931.4181859.4919942.6861855.194
9959.1461848.3139969.1881842.8839981.778 1833.279992.0661827.1199994.3671826.226
10006.951825.87610008.531826.16210019.551830.92810024.971832.89910032.321834.925
10040.761840.13310045.271844.302 10056.51855.94510071.761868.28910075.241870.792
#Mann= 3 , 0 , 0
9699.107    0.12       09699.107    0.12       010075.24    0.12       0
#XS Ineff= 2 , 0
       0                               0
Bank Sta=9699.107,10075.24
Exp/Cntr=0.3,0.1

Type RM Length L Ch R = 1 ,39589.78,285.815500,285.815500,285.815500
XS GIS Cut Line= 5
702444.264542609782307.937069982702378.186595649782201.010937661
702348.151165247782150.551414549702261.779293299782040.698137596
702220.800940245781993.165759116
#Sta/Elev= 30
9729.3571887.1489744.5651886.0319766.0031882.7749779.8321877.0189785.0261876.419
9850.3641876.3579862.0491874.8519873.6861874.4319900.3851870.1659908.5991868.072
9913.7761864.9589920.8371859.7519933.5581853.407    9959 1843.639967.4111839.975
9971.7211837.7059984.4411828.7729997.162 1825.2310009.881825.58210015.951827.517
 10022.61830.59210035.321835.25910048.051841.35710061.041849.96810074.241859.644
10087.451870.40710094.531875.58310100.651878.72710109.841880.56310116.281880.583
#Mann= 3 , 0 , 0
9729.357  0.0644       09729.357  0.0644       010116.28  0.0644       0
#XS Ineff= 2 , 0
       0                               0
Bank Sta=9729.357,10116.28
Exp/Cntr=0.3,0.1

Type RM Length L Ch R = 1 ,39303.97,305.604000,305.604000,305.604000
XS GIS Cut Line= 6
702579.872719637781733.115937006 702458.68015635781773.399435569
702358.365725006781824.667927132702336.325710428 781850.25551849
702316.967127037781923.200164025702285.076880429781954.480327393
#Sta/Elev= 30
9698.1791984.2629713.6671978.8699724.081 1973.719734.4941966.2969744.9081959.879
9755.3221951.6559765.8551942.0099808.558 1909.429841.0531888.318 9852.071880.047
9863.0881871.0619874.1061864.3269899.5441857.7599907.9661854.981 9919.481846.546
9931.0851842.7679938.7541839.5339954.1071831.8079957.5211830.4269966.6231828.182
9977.7921827.6389998.2221824.92810008.331824.37310018.451824.30610028.131831.349
10039.981843.95310052.281845.51410068.79 1851.6210082.331857.40410094.12 1860.88
#Mann= 3 , 0 , 0
9698.179  0.0565       09698.179  0.0565       010094.12  0.0565       0
#XS Ineff= 2 , 0
       0                               0
Bank Sta=9698.179,10094.12
Exp/Cntr=0.3,0.1

Type RM Length L Ch R = 1 ,38998.36,212.373800,212.373800,212.373800
XS GIS Cut Line= 6
702560.813626555781590.595572233702485.605963135781605.283805557
702344.766702038  781637.1037175 702248.04357591781653.737048422
 702151.18965966781659.521663556701965.460913853781661.834309204
#Sta/Elev= 30
9699.0181966.636 9715.131962.5099725.3191957.3129786.5191937.1199848.0321922.221
9858.2841917.8129878.7881902.4599909.5441880.3379919.7961873.5299940.1111861.199
9950.2681853.7499960.4241843.7139970.5811834.4489980.7371821.1179990.8941819.404
10001.051819.11710011.15 1819.7310031.281827.54510051.35 1831.7510061.381835.405
10071.391841.608 10081.4 1846.8810101.411856.12610111.421857.05910121.421856.019
10141.431863.50210151.43 1864.0910171.431863.25610251.431863.44810300.981865.118
#Mann= 3 , 0 , 0
9699.018  0.0612       09699.018  0.0612       010300.98  0.0612       0
#XS Ineff= 2 , 0
       0                               0
Bank Sta=9699.018,10300.98
Exp/Cntr=0.3,0.1

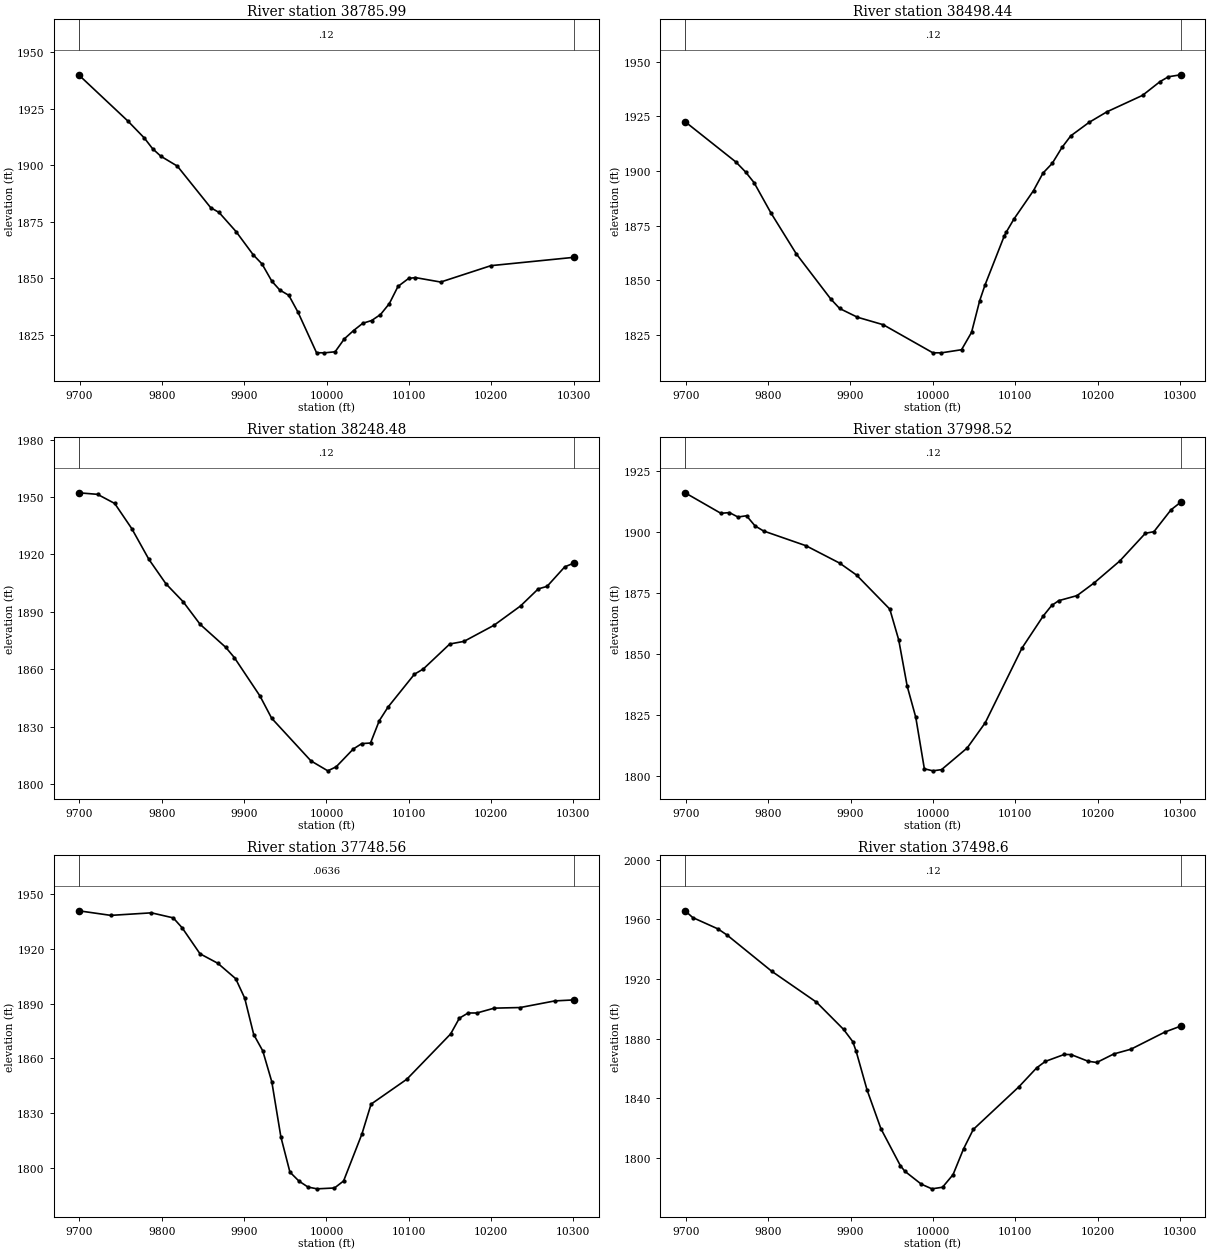
Type RM Length L Ch R = 1 ,38785.99,287.545800,287.545800,287.545800
XS GIS Cut Line= 6
 702504.79212771781385.753032859702332.810928219781398.344622034
702273.756087881781416.726840273702110.243441523781488.905313995
702018.285821708 781506.95113359701924.277379131781513.597252164
#Sta/Elev= 30
9698.869 1939.969758.6751919.532 9778.681912.0239788.6831907.3189798.7051903.992
9818.796 1899.619859.2721881.2619869.4181879.1539890.0721870.7069910.9711860.428
9921.596 1856.419933.5441848.7859943.1611844.8899954.1441842.5479965.3111835.095
9987.8181817.1989997.3231817.14510010.391817.61110021.581823.31510032.771826.981
10043.961830.19310054.751831.42210065.491834.05210076.221838.87810086.761846.482
10099.571849.98110107.711850.39310138.621848.41310199.671855.65610300.74 1859.34
#Mann= 3 , 0 , 0
9698.869    0.12       09698.869    0.12       010300.74    0.12       0
#XS Ineff= 2 , 0
       0                               0
Bank Sta=9698.869,10300.74
Exp/Cntr=0.3,0.1

Type RM Length L Ch R = 1 ,38498.44,249.959800,249.959800,249.959800
XS GIS Cut Line= 6
702437.598061537781294.902837011  702231.4624229781244.044293702
702185.546658669781211.732385051702158.202817773781160.119994076
702112.956926655781119.037627329701921.567789096781029.870949223
#Sta/Elev= 30
9699.2351922.5069760.9991904.0589772.7841899.4729782.9711894.651 9803.441880.803
9834.2151862.1139876.041 1841.499886.8561837.1339908.4851833.1419939.828 1829.71
10000.021816.88810010.391816.86810034.851818.29410046.991826.22310056.88 1840.71
10063.351847.87910086.461870.05310089.071871.998 10098.51878.04210122.21 1891.01
10133.731899.01610144.971903.46710156.76 1910.7210167.471916.041 10189.71922.191
10211.441927.04110254.561934.53310275.871940.83410285.961943.02710300.831943.942
#Mann= 3 , 0 , 0
9699.235    0.12       09699.235    0.12       010300.83    0.12       0
#XS Ineff= 2 , 0
       0                               0
Bank Sta=9699.235,10300.83
Exp/Cntr=0.3,0.1

Type RM Length L Ch R = 1 ,38248.48,249.959800,249.959800,249.959800
XS GIS Cut Line= 6
702627.203523372781087.883884333702389.208643504781021.617300578
702320.406567578781006.070322898 702292.53467599780998.252074093
702252.755471254780983.962074638702054.351469613780906.091169404
#Sta/Elev= 30
9699.0221952.205 9722.071951.3829742.8311946.6249763.5921933.4579784.3521917.414
9805.1131904.6029825.8741895.3079846.6351883.4289877.7761871.3919888.1571866.058
9919.2981845.9719933.4591834.3649981.2031812.056 10001.71806.84410011.92 1808.97
10032.621818.25110043.011821.09410053.571821.384 10064.2 1833.0310074.831840.161
10106.911857.35910117.651860.06410149.881873.15810167.111874.51910203.591882.945
10235.821893.03810257.311901.95210268.051903.27610289.54 1913.4910300.971915.519
#Mann= 3 , 0 , 0
9699.022    0.12       09699.022    0.12       010300.97    0.12       0
#XS Ineff= 2 , 0
       0                               0
Bank Sta=9699.022,10300.97
Exp/Cntr=0.3,0.1

Type RM Length L Ch R = 1 ,37998.52,249.959800,249.959800,249.959800
XS GIS Cut Line= 6
 702646.85839217780834.640435088 702537.24779334780804.151663722
702388.147180992780771.145066226702325.031581968780752.212404449
702186.080791229 780720.27551461 702063.73390272780686.312705845
#Sta/Elev= 30
9699.0441916.0849742.4911907.6719752.8711907.962 9763.251906.153 9773.631906.669
 9784.011902.5129794.3891900.4229845.844 1894.399886.8121887.2519907.2971882.368
 9947.69  1868.49958.5071855.8199968.8081836.8429979.2351824.0769989.6631802.966
10000.11 1802.1310010.57 1802.6310041.721811.50910063.621821.83510108.261852.448
10134.061865.59110144.321869.90110152.911871.87210175.121873.94210195.871879.139
10227.011888.11810258.141899.48110268.521900.14310289.281909.10710300.971912.195
#Mann= 3 , 0 , 0
9699.044    0.12       09699.044    0.12       010300.97    0.12       0
#XS Ineff= 2 , 0
       0                               0
Bank Sta=9699.044,10300.97
Exp/Cntr=0.3,0.1

Type RM Length L Ch R = 1 ,37748.56,249.959800,249.959800,249.959800
XS GIS Cut Line= 6
702731.041371076780659.088003241702550.975917572780583.869390946
 702443.26017245780537.073014411702369.126543945780503.016793022
702286.615656328 780472.91407895702172.652641875780435.755138561
#Sta/Elev= 30
9699.0161940.9989738.0761938.4769787.4531939.8739813.9381937.1089824.7751931.654
 9846.451917.4139868.1251912.189  9889.81903.7519900.7281893.1169911.7191873.083
9922.7091864.1319933.6991847.1449944.6891816.956 9955.681797.647 9966.671792.711
 9977.661789.4399988.6751788.46710009.81 1788.9410020.861792.77810043.131818.534
10054.261834.92710097.671848.59210150.891873.42710161.54 1882.0910172.181884.938
 10182.81884.92910203.841887.587 10235.41887.92310277.47 1891.5610300.971892.111
#Mann= 3 , 0 , 0
9699.016  0.0636       09699.016  0.0636       010300.97  0.0636       0
#XS Ineff= 2 , 0
       0                               0
Bank Sta=9699.016,10300.97
Exp/Cntr=0.3,0.1

Type RM Length L Ch R = 1 , 37498.6,209.275700,209.275700,209.275700
XS GIS Cut Line= 6
702791.297609373780448.884026406702589.294650156780359.305331775
702494.588097653780289.736347083702451.231898548780266.256789074
702383.016963789780241.815794378702246.719167177780204.656250473
#Sta/Elev= 30
9699.069 1965.689708.3661961.1269739.0191953.5259750.0251949.4249804.3531925.126
9858.6641904.4249891.6231886.1479902.6931878.0179906.8051871.581 9920.081845.603
9936.9131819.6399960.4651794.9529966.0041791.1159985.892  1782.59998.8621779.348
10011.721780.418 10024.51788.85110037.291806.15710049.041819.114 10104.61847.789
10126.031860.39710136.541864.72910159.671869.42210167.971869.303 10188.71864.822
10199.071864.027 10219.81869.74510240.531872.91110281.991884.46210300.94 1888.37
#Mann= 3 , 0 , 0
9699.069    0.12       09699.069    0.12       010300.94    0.12       0
#XS Ineff= 2 , 0
       0                               0
Bank Sta=9699.069,10300.94
Exp/Cntr=0.3,0.1