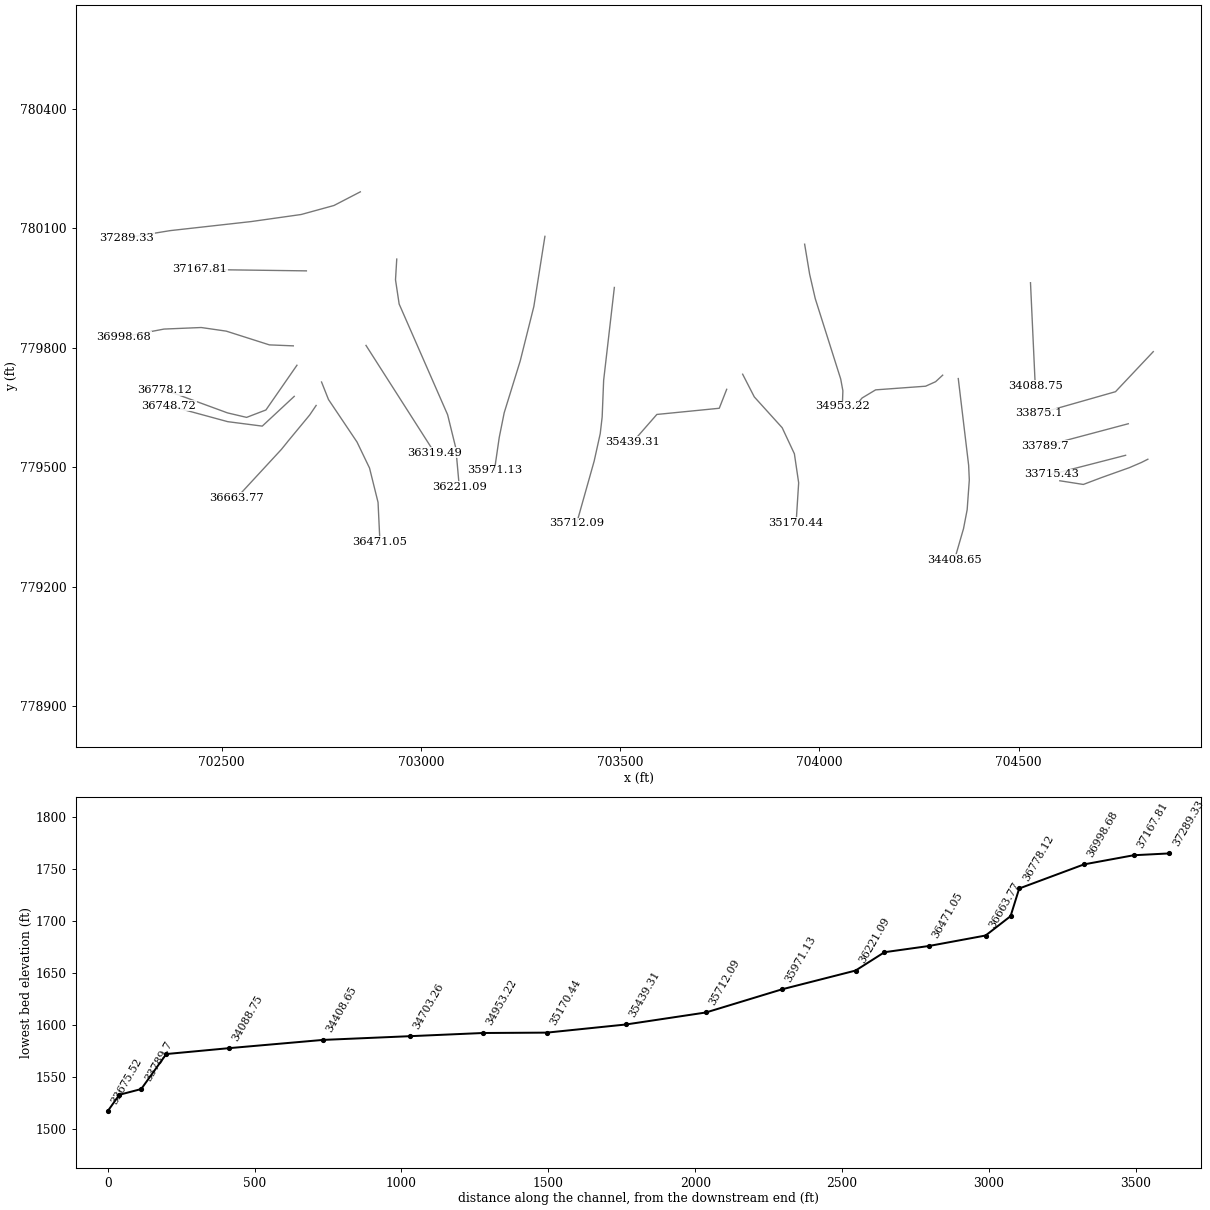
HEC-RAS study 14536_ras.prj: 14536

--- 14536_ras.g01 (geometry) --- (continued)

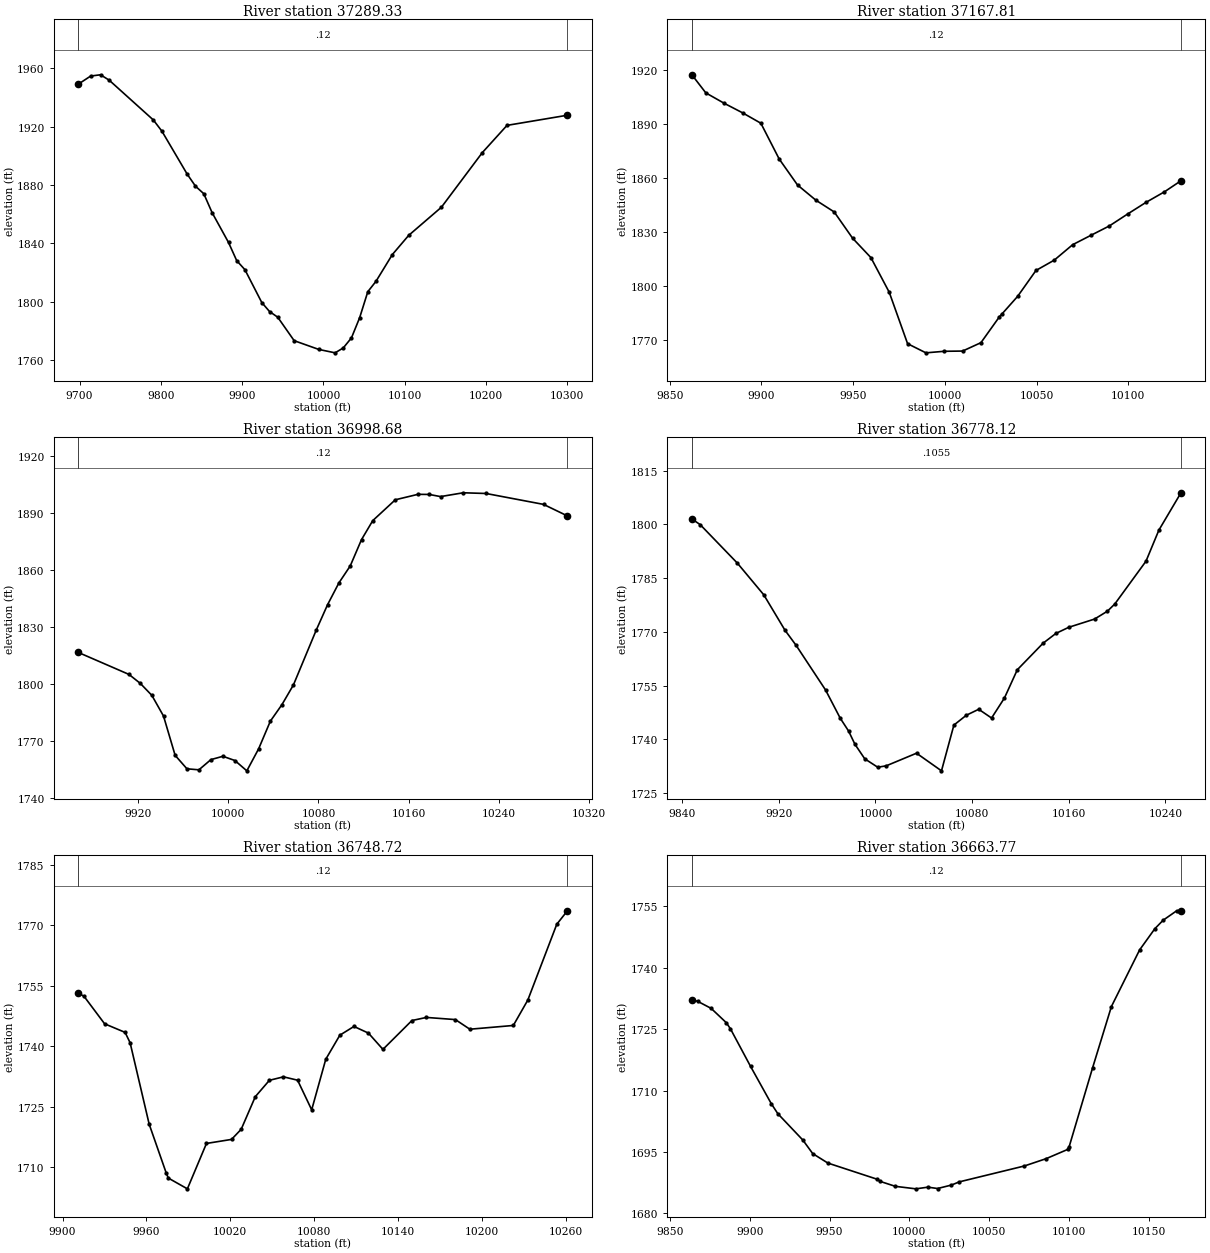
Type RM Length L Ch R = 1 ,37289.33,121.516100,121.516100,121.516100
XS GIS Cut Line= 6
702847.994506088780191.087583069702781.800305743780156.798078723
702699.553693446780134.197739257702573.821744402780116.434531188
702370.849175766780093.754103873702261.649357166780075.881904936
#Sta/Elev= 30
9698.3851949.202 9713.591954.7569725.7431955.6329736.3621951.935 9790.731924.631
9801.2631916.9519832.3211887.5289842.5791879.2179852.8371874.0169863.0231861.077
9883.221 1840.639893.3211828.145 9903.421821.9329924.1741799.4169933.7181793.239
9943.8171789.3329964.0161773.2449994.2831767.24510014.41  1764.910024.47 1768.28
10034.531775.15810044.591788.96210054.661806.84210064.721813.95910084.841832.304
10104.97 1845.4810145.211864.76910195.571902.23910225.97 1920.9310300.291927.888
#Mann= 3 , 0 , 0
9698.385    0.12       09698.385    0.12       010300.29    0.12       0
#XS Ineff= 2 , 0
       0                               0
Bank Sta=9698.385,10300.29
Exp/Cntr=0.3,0.1

Type RM Length L Ch R = 1 ,37167.81,169.127800,169.127800,169.127800
XS GIS Cut Line= 2
 702712.61771664779992.744514555702445.945578992779996.300143063
#Sta/Elev= 29
9862.0581917.3259869.676 1907.289879.6771901.5259889.6781896.2469899.6791890.462
9909.6791870.612 9919.681856.1969929.6811847.7819939.6821841.2529949.6831826.723
9959.684 1815.959969.6851796.7269979.6861768.2119989.6871763.1399999.6871763.998
10009.691764.12710019.691768.78210029.691783.03110031.231784.78110039.691794.452
10049.691808.81210059.691814.56210069.691823.10310079.691828.322 10089.71833.503
 10099.71840.139 10109.71846.581 10119.71852.39810128.751858.566
#Mann= 3 , 0 , 0
9862.058    0.12       09862.058    0.12       010128.75    0.12       0
#XS Ineff= 2 , 0
       0                               0
Bank Sta=9862.058,10128.75
Exp/Cntr=0.3,0.1

Type RM Length L Ch R = 1 ,36998.68,220.564500,220.564500,220.564500
XS GIS Cut Line= 6
702679.809188458779804.556149819702619.796903755779807.013587233
702511.572348351779841.500271486 702448.66614949779850.586146339
702355.438774465 779846.70529586702254.301473456 779827.52525644
#Sta/Elev= 30
9866.9181816.7299911.9091805.1429921.984 1800.399932.1831794.1069942.5151783.233
9952.8471762.5069963.3161755.4269973.9491754.8899984.583 1760.279995.2161762.015
10005.861759.79210016.461754.352 10026.91765.91710037.331780.52510047.61 1789.22
10057.811799.61610078.071828.53410088.121841.90510098.17 1853.3710108.21  1862.3
10118.211876.15610128.211886.17810148.221897.14910168.281900.01710178.311899.962
10188.34 1898.83 10208.51900.83910228.751900.46510279.721894.72810300.921888.652
#Mann= 3 , 0 , 0
9866.918    0.12       09866.918    0.12       010300.92    0.12       0
#XS Ineff= 2 , 0
       0                               0
Bank Sta=9866.918,10300.92
Exp/Cntr=0.3,0.1

Type RM Length L Ch R = 1 ,36778.12,29.403700,29.403700,29.403700
XS GIS Cut Line= 5
702688.922276467779755.927418724702611.086135924779643.685447931
702562.579555601779625.072457761 702514.63700524779636.353057861
 702357.83666414779693.884118274
#Sta/Elev= 30
9848.0411801.5039854.9241799.9259885.6771789.1849907.569 1780.339925.1171770.442
9934.3541766.2099958.6921753.7679970.8621745.8769977.7621742.3039983.031  1738.6
9991.1491734.54610001.861732.20310008.871732.58510033.991736.11410054.651731.193
10064.921743.96510075.191746.70810085.461748.377 10096.11745.93710106.75 1751.52
10117.411759.41110138.711766.81110149.361769.55410160.011771.26510181.321773.557
10191.971775.75310198.041777.74110223.921789.71610234.581798.38310252.861808.813
#Mann= 3 , 0 , 0
9848.041  0.1055       09848.041  0.1055       010252.86  0.1055       0
#XS Ineff= 2 , 0
       0                 10031.6       0
Bank Sta=9848.041,10252.86
Exp/Cntr=0.3,0.1

Type RM Length L Ch R = 1 ,36748.72,84.947000,84.947000,84.947000
XS GIS Cut Line= 4
702682.133646667779677.804656714702601.882099688779603.152054891
702515.098450035779614.349945173702367.659561396779654.475718647
#Sta/Elev= 30
 9911.25 1753.219915.368 1752.38 9930.051745.5739944.7321743.4349948.3091740.859
9961.9661720.6189974.0961708.5719975.6241707.2679989.2821704.58810002.941715.861
10020.861716.85910027.791719.38410037.881727.47310047.961731.53710058.041732.399
10068.131731.56210078.211724.20610088.291736.76810098.371742.74610108.461744.908
10118.821743.25510129.191739.21910149.921746.38110160.28 1747.1510181.011746.615
10191.371744.22210222.461745.15310232.831751.45810253.551770.28110261.161773.632
#Mann= 3 , 0 , 0
 9911.25    0.12       0 9911.25    0.12       010261.16    0.12       0
#XS Ineff= 2 , 0
       09959.274        10026.72       0
Bank Sta=9911.25,10261.16
Exp/Cntr=0.3,0.1

Type RM Length L Ch R = 1 ,36663.77,192.723100,192.723100,192.723100
XS GIS Cut Line= 6
702737.125062776779654.996991917702720.671185937779630.786170645
702665.297200709779563.880499002702664.116827389779562.265965377
702649.823751988779544.646241433702537.413529368779422.978204484
#Sta/Elev= 30
9863.7061732.2159867.4861731.7849875.7931730.0849885.2771726.5939887.8841725.093
9900.4891715.915 9913.471706.8129917.5571704.3729933.2411697.9299939.4321694.619
9948.9251692.3099979.8271688.3579981.8271687.8189991.1831686.62610004.061686.014
10011.621686.42310017.651686.09410026.361686.94110031.261687.71610072.111691.603
10085.721693.38910099.341695.66610100.041696.22110114.781715.55510126.571730.529
10144.251744.363 10153.81749.54410158.981751.61210167.411753.90310170.161753.922
#Mann= 3 , 0 , 0
9863.706    0.12       09863.706    0.12       010170.16    0.12       0
#XS Ineff= 2 , 0
       0                10033.88       0
Bank Sta=9863.706,10170.16
Exp/Cntr=0.3,0.1

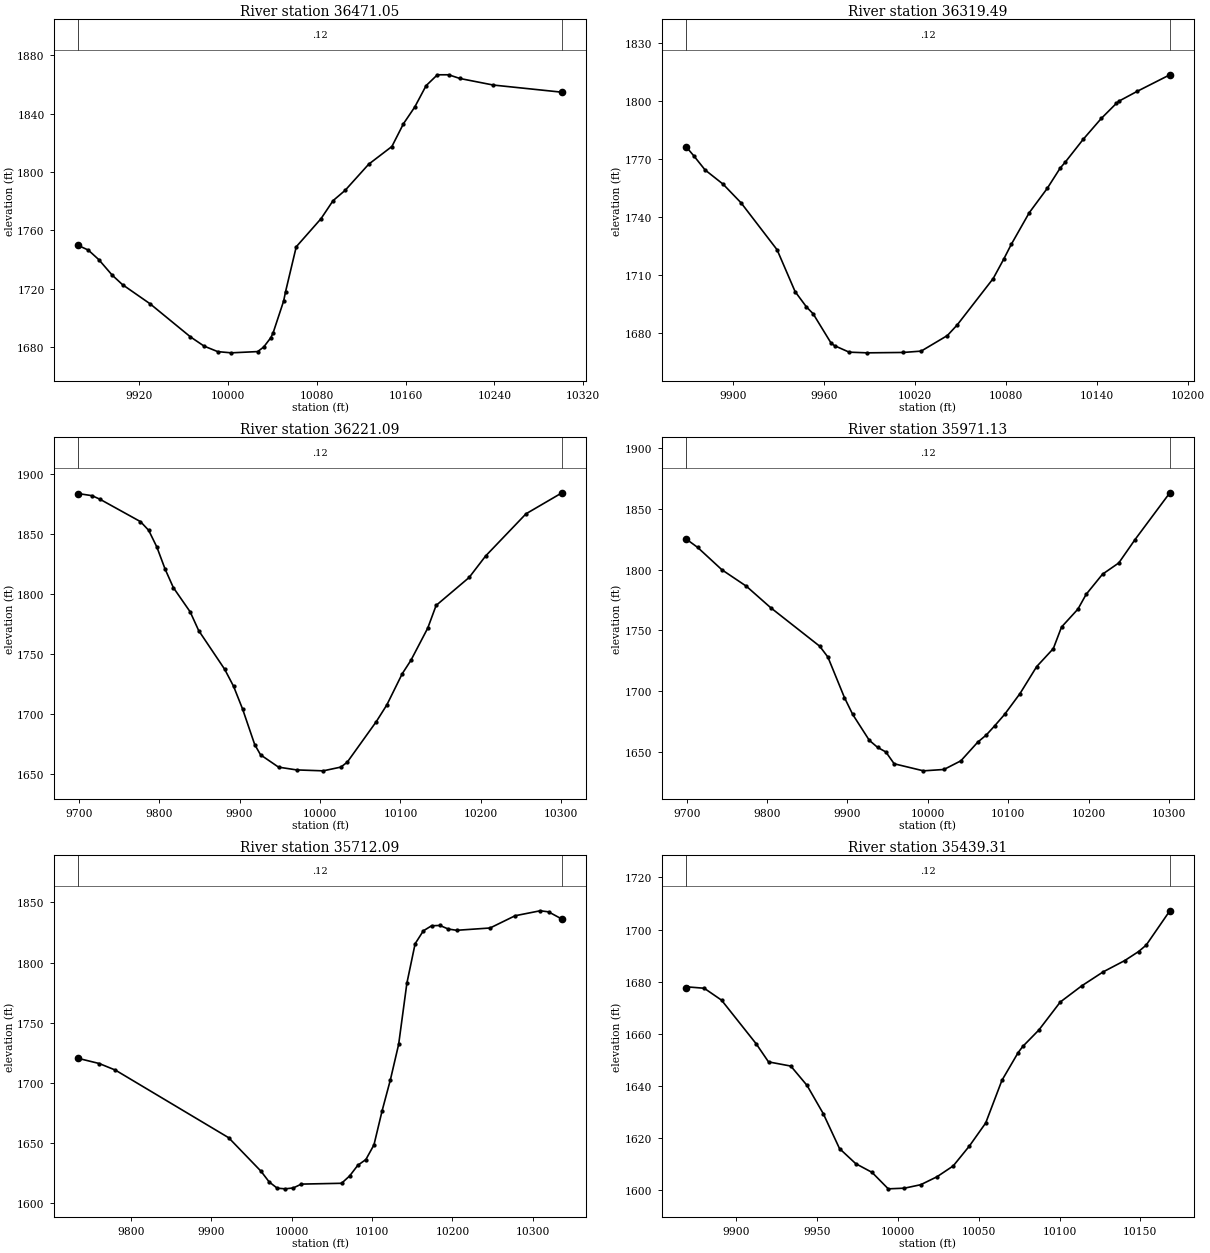
Type RM Length L Ch R = 1 ,36471.05,151.553000,151.553000,151.553000
XS GIS Cut Line= 6
702750.654160333 779713.84129136702768.105080644779669.840997505
702839.672894491779563.231273682702871.069107812779497.947660781
702892.457887434779411.771338259 702897.16016216779313.110676668
#Sta/Elev= 30
 9864.691749.6919873.9191746.4359883.4071739.8859895.4321729.2799904.7561722.732
9929.5871709.6139965.9921686.9129978.2781680.5829990.5651676.79310002.761675.959
10026.581676.81910031.991679.92810038.491686.40210040.591689.85510049.971711.444
10051.721717.89310061.361748.70110083.691767.98810094.57 1780.3610105.451787.428
10126.651805.33210147.561817.48610158.011833.12810168.191844.58410178.381859.197
10188.561866.67410198.74 1866.6810208.831864.14610238.941859.638 10300.91854.725
#Mann= 3 , 0 , 0
 9864.69    0.12       0 9864.69    0.12       0 10300.9    0.12       0
#XS Ineff= 2 , 0
       0                               0
Bank Sta=9864.69,10300.9
Exp/Cntr=0.3,0.1

Type RM Length L Ch R = 1 ,36319.49,98.406800,98.406800,98.406800
XS GIS Cut Line= 2
702862.233048588779805.647237375703033.934032798779536.897870749
#Sta/Elev= 30
9868.9451776.4269874.0851771.695 9881.581764.3399893.4471757.0059905.3131747.355
9929.0471723.1399940.9131701.561 9948.381693.664 9952.781690.1419964.6471674.954
9966.954 1673.649976.5131670.322 9988.381669.97110012.111670.16910023.981670.858
10041.251678.90210047.711684.35710071.451708.318 10078.41718.33810083.311725.872
10095.181742.24610107.051754.81710115.551765.25310118.911768.34710130.781780.164
10142.65 1790.8910152.691798.75210154.511799.92210166.381804.91710187.861813.438
#Mann= 3 , 0 , 0
9868.945    0.12       09868.945    0.12       010187.86    0.12       0
#XS Ineff= 2 , 0
       0                               0
Bank Sta=9868.945,10187.86
Exp/Cntr=0.3,0.1

Type RM Length L Ch R = 1 ,36221.09,249.959800,249.959800,249.959800
XS GIS Cut Line= 6
702939.396064493780022.365796466702936.264607288 779970.37638324
 702945.40643357779909.528731911703067.022254043779631.755598788
703087.568796047779548.174599903703096.392410194779450.310815942
#Sta/Elev= 30
9699.0591883.9339716.523 1882.149726.417 1879.139776.7031860.4699786.885 1853.24
9797.0671839.2469807.2491820.9519817.5581805.3899838.4851785.1269849.0621769.513
9881.3841737.1839892.4921722.9189903.6761703.9649918.769 1674.269926.0451665.698
9948.4131655.4279970.782 1653.1110003.981652.333   100261655.484 10033.91659.618
10070.06 1693.53 10083.11707.42410102.281733.491   101131744.61510133.951771.529
10144.381790.49510185.441813.84310205.831831.69310256.16 1867.0110300.94 1884.57
#Mann= 3 , 0 , 0
9699.059    0.12       09699.059    0.12       010300.94    0.12       0
#XS Ineff= 2 , 0
       0                               0
Bank Sta=9699.059,10300.94
Exp/Cntr=0.3,0.1

Type RM Length L Ch R = 1 ,35971.13,259.040100,259.040100,259.040100
XS GIS Cut Line= 6
703311.210437312780079.407085878703283.429766969 779903.34645443
703249.209785132779766.683099081703209.054307607779636.790956811
703196.625305358779574.977893975703184.549029572779492.130167622
#Sta/Elev= 30
9699.0261825.4889713.5731818.4389743.866 1799.949774.1581786.469 9804.461768.752
9865.456 1737.019875.6221728.0779896.2151694.7119906.5231680.7769927.1391659.488
9937.447 1653.699947.7551649.8819958.0631640.1669994.4761634.34910019.96 1635.47
10041.02  1642.610062.091658.04210072.621663.85410083.151671.48610095.331680.766
10114.611698.04910135.331720.23910156.021735.05210166.221752.81410186.621767.579
10196.821779.71710217.221796.34510237.431805.60210257.641824.85710300.961863.407
#Mann= 3 , 0 , 0
9699.026    0.12       09699.026    0.12       010300.96    0.12       0
#XS Ineff= 2 , 0
       0                               0
Bank Sta=9699.026,10300.96
Exp/Cntr=0.3,0.1

Type RM Length L Ch R = 1 ,35712.09,272.777700,272.777700,272.777700
XS GIS Cut Line= 6
703485.452078084779951.111199379703458.574445212779717.929596529
703454.866960962 779626.10373379703450.021070888779584.287493591
703434.807931377779515.448438104 703390.69999089779358.866632841
#Sta/Elev= 30
9734.2971720.5229760.5811716.2059780.7141710.7369921.6411654.5479961.9061626.671
9971.9611617.8549981.9891612.6319992.0171612.08710002.051612.85510012.051616.023
10062.071616.70610072.141622.83810082.211631.62610092.281636.43410102.341648.586
10112.571677.14410122.811702.76610133.051732.12210143.291782.92910153.541815.698
10163.781826.43510174.03 1830.6310184.411830.893 10194.81827.91110205.191826.865
10246.75 1828.7810277.921838.96110309.081843.08110319.471842.20310336.241836.136
#Mann= 3 , 0 , 0
9734.297    0.12       09734.297    0.12       010336.24    0.12       0
#XS Ineff= 2 , 0
       0                               0
Bank Sta=9734.297,10336.24
Exp/Cntr=0.3,0.1

Type RM Length L Ch R = 1 ,35439.31,268.866900,268.866900,268.866900
XS GIS Cut Line= 4
 703767.39584592 779695.53464967 703748.73269546779647.943616018
703592.111703485779632.436587095703532.240150124 779563.95943895
#Sta/Elev= 30
9868.7791677.6159869.354 1678.029880.0951677.4899890.8361672.9179912.3191656.131
9919.8991649.2329933.6991647.6279943.7481640.1999953.797 1629.359963.8451615.966
9973.8941610.1759983.9431606.8479993.9921600.52410004.04 1600.7810014.091602.109
10024.141605.15210034.191609.31410044.241616.98710054.291625.78910064.331642.148
10074.381652.80410077.291655.19510087.161661.44110100.451672.20710113.731678.409
10127.011683.777 10140.31688.09510148.86 1691.5510153.581694.01710168.251707.208
#Mann= 3 , 0 , 0
9868.779    0.12       09868.779    0.12       010168.25    0.12       0
#XS Ineff= 2 , 0
       0                               0
Bank Sta=9868.779,10168.25
Exp/Cntr=0.3,0.1

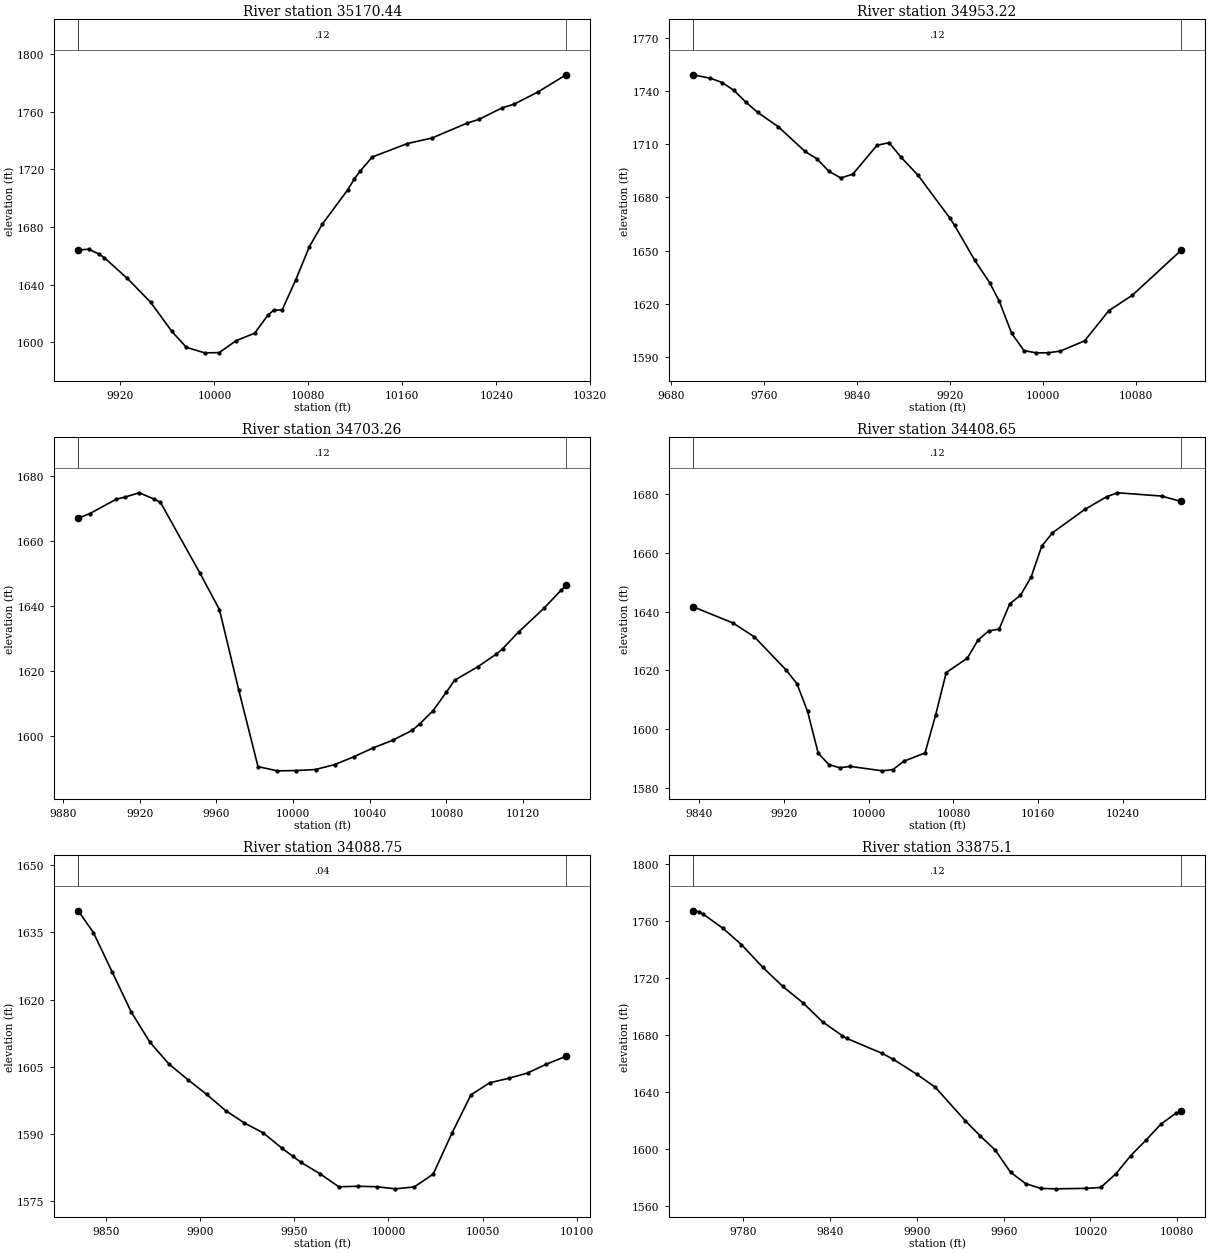
Type RM Length L Ch R = 1 ,35170.44,217.220300,217.220300,217.220300
XS GIS Cut Line= 6
703807.414059558779733.409797807 703836.65371054779676.430755792
703906.620934217779599.111833717703937.256940068779533.684444885
703947.977387305779460.870283521703941.601134235779360.952071814
#Sta/Elev= 30
  9884.1 1663.979892.9591664.5489902.0821661.0899906.4211658.5739925.8231644.356
9945.6761627.813 9963.821607.5269976.1561596.5279991.6741592.71110004.131592.859
10018.381601.12310034.251606.29410045.48 1618.7610050.371622.17710057.75 1622.56
10069.311643.39910080.881666.36210091.941681.96310113.351705.59210119.151713.267
10124.061718.65510134.331728.45310164.341737.81910185.031741.57910215.071751.933
10225.071754.50910245.111762.60810255.161765.10510275.251773.45810299.411785.473
#Mann= 3 , 0 , 0
  9884.1    0.12       0  9884.1    0.12       010299.41    0.12       0
#XS Ineff= 2 , 0
       0                               0
Bank Sta=9884.1,10299.41
Exp/Cntr=0.3,0.1

Type RM Length L Ch R = 1 ,34953.22,249.959800,249.959800,249.959800
XS GIS Cut Line= 6
703962.965478993780059.692583877703975.518711397779984.368751419
703989.622982849779923.037951046704053.498511017779721.285263552
704058.948000884779691.880264213704057.563775257779653.261222054
#Sta/Elev= 30
 9699.041749.1729713.9361747.1919724.0741744.7859734.2121740.3139744.3491733.721
9754.4871727.9759772.248 1719.869795.2771705.9359805.5391701.788  9815.81694.715
9826.0611691.0019836.3221693.1049857.1471709.3979867.5761710.8859878.0061702.538
 9892.491692.4969920.0231668.158 9923.921664.2069941.2191644.5459954.1241631.897
9962.4141621.3259973.0121603.326 9983.611593.6189994.1271592.35710004.511592.381
10014.931593.37810035.751599.12510056.421616.06510076.771624.82610118.661650.146
#Mann= 3 , 0 , 0
 9699.04    0.12       0 9699.04    0.12       010118.66    0.12       0
#XS Ineff= 2 , 0
       0                               0
Bank Sta=9699.04,10118.66
Exp/Cntr=0.3,0.1

Type RM Length L Ch R = 1 ,34703.26,294.606400,294.606400,294.606400
XS GIS Cut Line= 6
704309.394096073779731.008453496704291.586846782779714.586799012
704266.566221869779703.316321711704141.123153985779694.140558946
704107.177239118 779673.76719153704083.514968124779646.074737882
#Sta/Elev= 30
9887.9341667.1189894.027 1668.529907.7831672.9389912.2381673.5689919.7051674.911
  9927.31673.0319930.8031671.9799951.4681650.1199961.5951638.9399971.7171614.034
9981.7191590.587 9991.721589.28310001.731589.37310011.741589.69510021.75 1591.22
10031.771593.628 10041.81596.35310051.891598.68410062.21 1601.7710066.221603.827
10072.88 1607.6810079.911613.45310084.241617.16210096.451621.36710105.991625.207
10109.311626.85910117.621632.02610130.891639.34810139.751644.85210142.45 1646.39
#Mann= 3 , 0 , 0
9887.934    0.12       09887.934    0.12       010142.45    0.12       0
#XS Ineff= 2 , 0
       0                               0
Bank Sta=9887.934,10142.45
Exp/Cntr=0.3,0.1

Type RM Length L Ch R = 1 ,34408.65,319.905400,319.905400,319.905400
XS GIS Cut Line= 6
704348.510831594779722.487218887704374.532110661779504.959831819
704376.215151399779468.016110778704370.828734636779393.397961691
704361.701181144779345.900690764704338.967544883779267.482656494
#Sta/Elev= 30
 9834.071641.6639871.8141636.1239891.9511631.3999922.1531620.0219932.1651615.402
9942.1771605.9929952.2271591.7519962.347 1587.859972.4671586.7639982.5861587.227
10012.881585.71610022.961586.16510033.041588.96910053.211591.82710063.221604.766
10073.231619.23110093.251624.19310103.251630.31210113.261633.40910123.261634.076
 10133.31642.69710143.361645.58410153.421651.76710163.481662.35210173.651666.915
 10204.2 1674.8710224.731679.18310235.071680.55310276.761679.43710295.131677.594
#Mann= 3 , 0 , 0
 9834.07    0.12       0 9834.07    0.12       010295.13    0.12       0
#XS Ineff= 2 , 0
       0                               0
Bank Sta=9834.07,10295.13
Exp/Cntr=0.3,0.1

Type RM Length L Ch R = 1 ,34088.75,213.646800,213.646800,213.646800
XS GIS Cut Line= 2
704529.755727232779963.014984161704541.683952183779704.570109785
#Sta/Elev= 29
9835.4731639.8039843.4971634.9519853.5071626.1269863.5181617.2739873.5281610.466
9883.5391605.645 9893.551602.159 9903.561598.8619913.571 1595.269923.582 1592.49
9933.592 1590.269943.6031586.836 9949.221585.0619953.6141583.6929963.6241581.181
9973.6351578.2559983.6461578.3679993.6561578.26310003.671577.79510013.68 1578.22
10023.691581.069 10033.7 1590.2510043.71 1598.7410053.721601.45310063.731602.442
10073.741603.62610083.751605.59510093.76 1607.2910094.19 1607.37
#Mann= 3 , 0 , 0
9835.473    0.04       09835.473    0.04       010094.19    0.04       0
#XS Ineff= 2 , 0
       0                               0
Bank Sta=9835.473,10094.19
Exp/Cntr=0.3,0.1

Type RM Length L Ch R = 1 , 33875.1,85.401700,85.401700,85.401700
XS GIS Cut Line= 3
704837.901538968779790.055722088 704743.08328566779689.522052675
704551.624139637779634.988797441
#Sta/Elev= 30
9745.3621767.0839749.5911766.4339752.3121764.7339766.0581754.707 9778.74 1743.34
 9793.551727.3989807.2961714.0389821.0421702.7499834.7881689.2599848.5341679.446
9851.613 1677.589876.0261667.0979883.556 1663.059900.0641652.4289912.7561643.336
9933.5521619.805 9943.951609.1339954.3471599.1369964.7451583.7769975.1431575.848
 9985.541572.4539995.9381572.14310016.731572.47810027.131573.09710037.531582.624
10047.93 1595.4910058.321606.18310068.721617.51510079.121625.20510082.63 1626.38
#Mann= 3 , 0 , 0
9745.362    0.12       09745.362    0.12       010082.63    0.12       0
#XS Ineff= 2 , 0
       0                               0
Bank Sta=9745.362,10082.63
Exp/Cntr=0.3,0.1

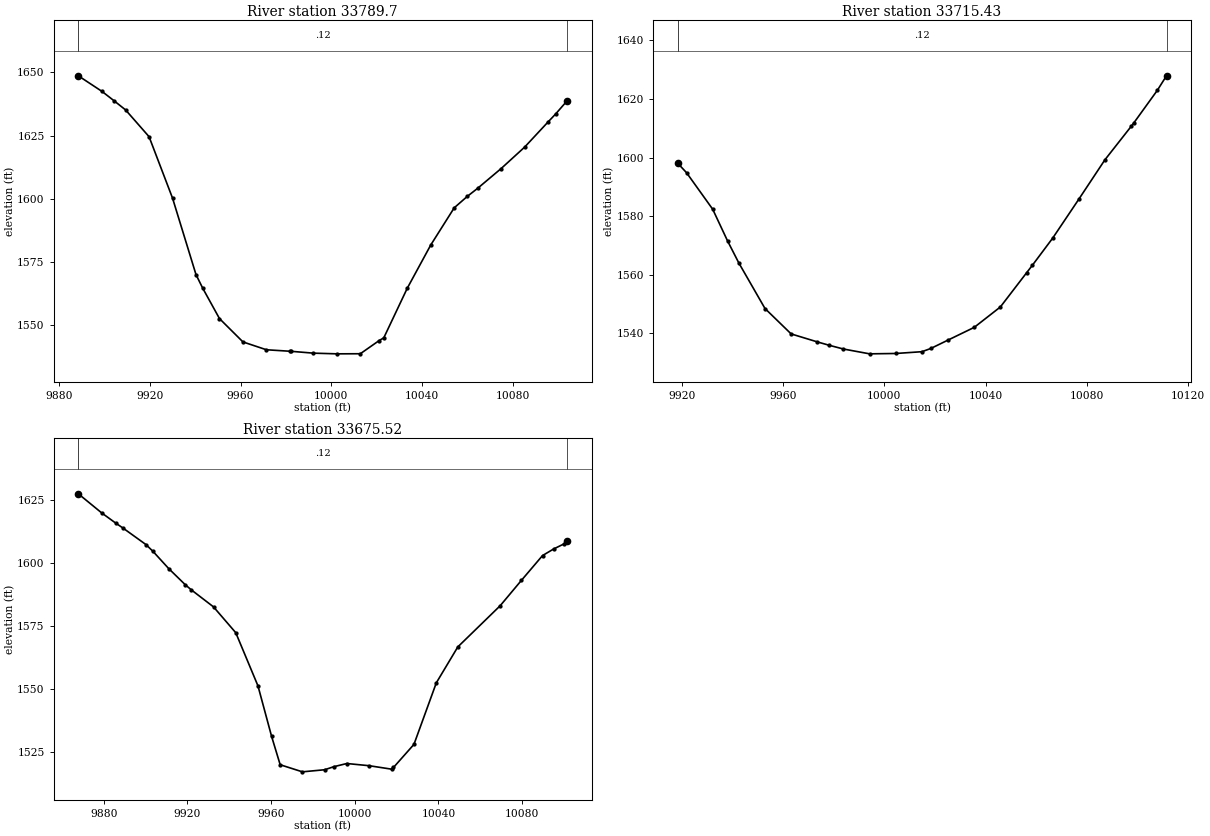
Type RM Length L Ch R = 1 , 33789.7,74.269800,74.269800,74.269800
XS GIS Cut Line= 2
704775.141802573779609.099030817704566.845382058779553.675129423
#Sta/Elev= 29
9888.472  1648.79888.6191648.6079898.9671642.4759904.4131638.6699909.3151635.169
9919.6631624.5619930.0111600.2119940.3591569.8939943.3031564.5349950.7071552.468
9961.0551543.2199971.4021540.113 9981.751539.5279982.1931539.5089992.0981538.771
10002.451538.49910012.791538.53810021.081543.74710023.141544.85210033.491564.508
10043.841581.63710054.191596.37610059.971600.91610064.531604.11410074.881611.942
10085.231620.43310095.581630.42310098.861633.52810104.021638.852
#Mann= 3 , 0 , 0
9888.472    0.12       09888.472    0.12       010104.02    0.12       0
#XS Ineff= 2 , 0
       0                               0
Bank Sta=9888.472,10104.02
Exp/Cntr=0.3,0.1

Type RM Length L Ch R = 1 ,33715.43,39.913200,39.913200,39.913200
XS GIS Cut Line= 2
704768.442210078779529.922028854704581.462674737779481.806773812
#Sta/Elev= 26
9918.3281598.1369921.8821594.8489932.2081582.3799938.0781571.5599942.5341564.023
9952.8591548.4889963.1851539.8159973.5111537.0969978.2051535.9399983.837 1534.66
9994.1631533.01610004.491533.13710014.811533.74610018.331534.84710025.141537.718
10035.471542.04810045.79 1549.0110056.121560.64710058.461563.27410066.441572.493
10076.771585.79110087.091599.26110097.421610.62710098.591611.95710107.751622.928
 10111.41627.929
#Mann= 3 , 0 , 0
9918.328    0.12       09918.328    0.12       0 10111.4    0.12       0
#XS Ineff= 2 , 0
       0                               0
Bank Sta=9918.328,10111.4
Exp/Cntr=0.3,0.1

Type RM Length L Ch R = 1 ,33675.52,28.243300,28.243300,28.243300
XS GIS Cut Line= 6
704824.245611753779520.031895266704808.282333374779512.000789717
704777.708344221779498.868454099704708.208514422779474.089825124
704662.349693179779456.763585582704603.313114554779466.005610347
#Sta/Elev= 30
9867.8871627.6429879.0831620.0329885.7571616.0039889.3291613.9789900.2131607.469
9903.4961604.8449911.0961597.9299919.0321591.4999921.9081589.4719932.5261582.705
9943.1441572.4629953.7621551.333 9960.281531.264 9964.381520.0089974.998 1517.19
9985.617 1518.029990.0221519.2359996.2471520.49710006.94 1519.6210017.631518.249
10018.541518.93210028.321528.09910039.011552.55110049.281566.80910069.521583.162
10079.641593.20610089.771603.09610095.091605.72110099.891607.674 10101.61608.976
#Mann= 3 , 0 , 0
9867.887    0.12       09867.887    0.12       0 10101.6    0.12       0
#XS Ineff= 2 , 0
       09899.543        10041.35       0
Bank Sta=9867.887,10101.6
Exp/Cntr=0.3,0.1