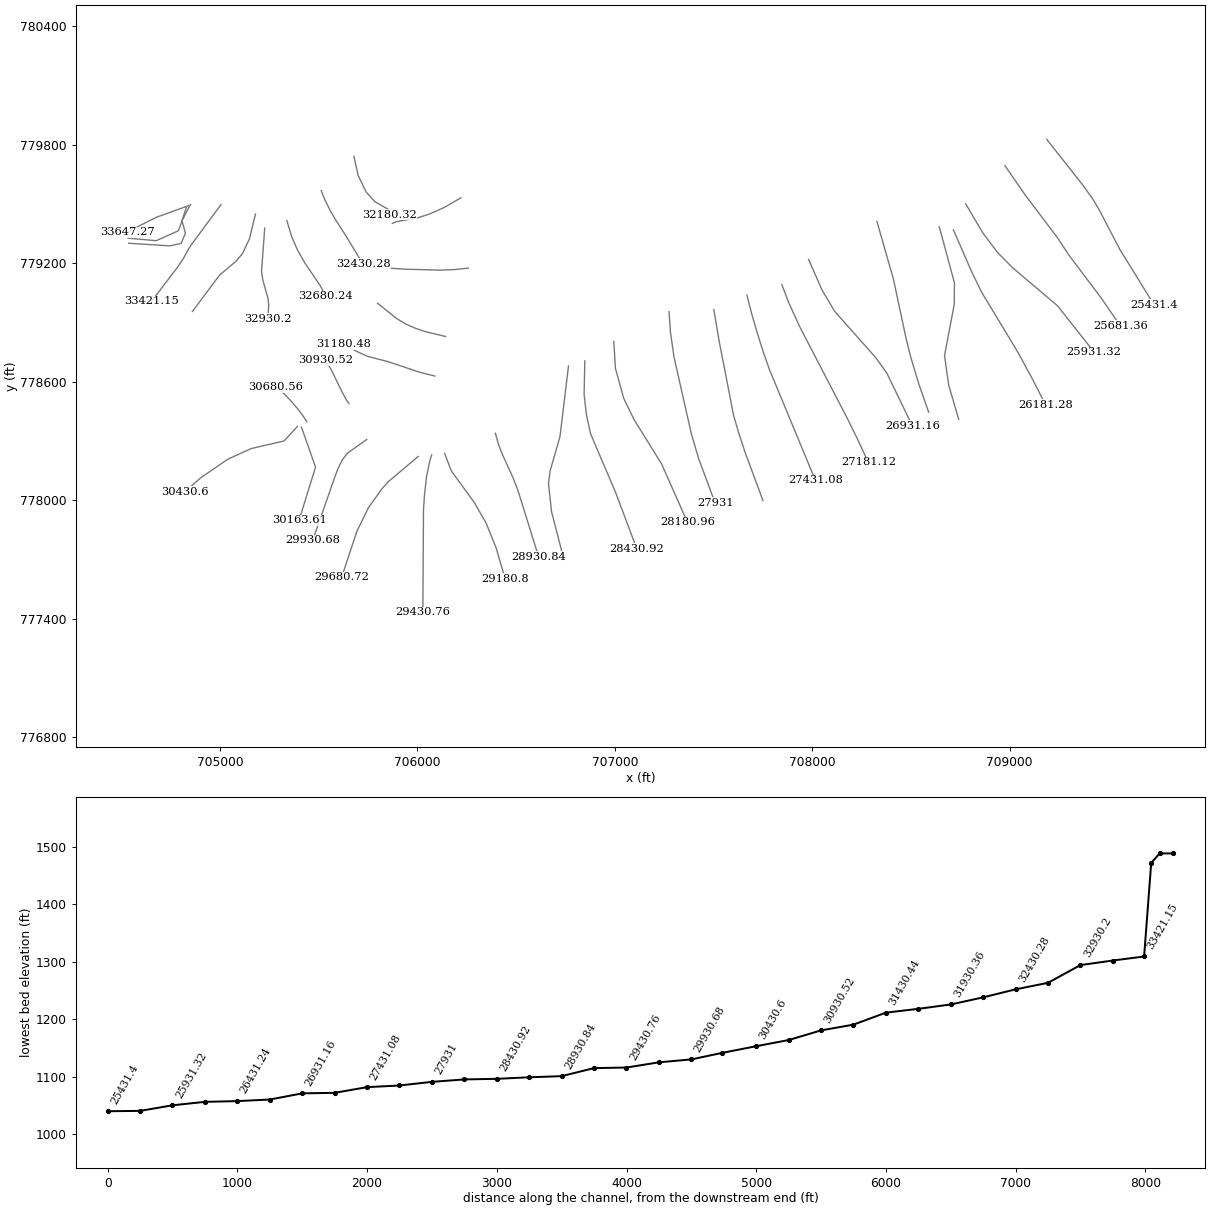
HEC-RAS study 14536_ras.prj: 14536

--- 14536_ras.g01 (geometry) --- (continued)

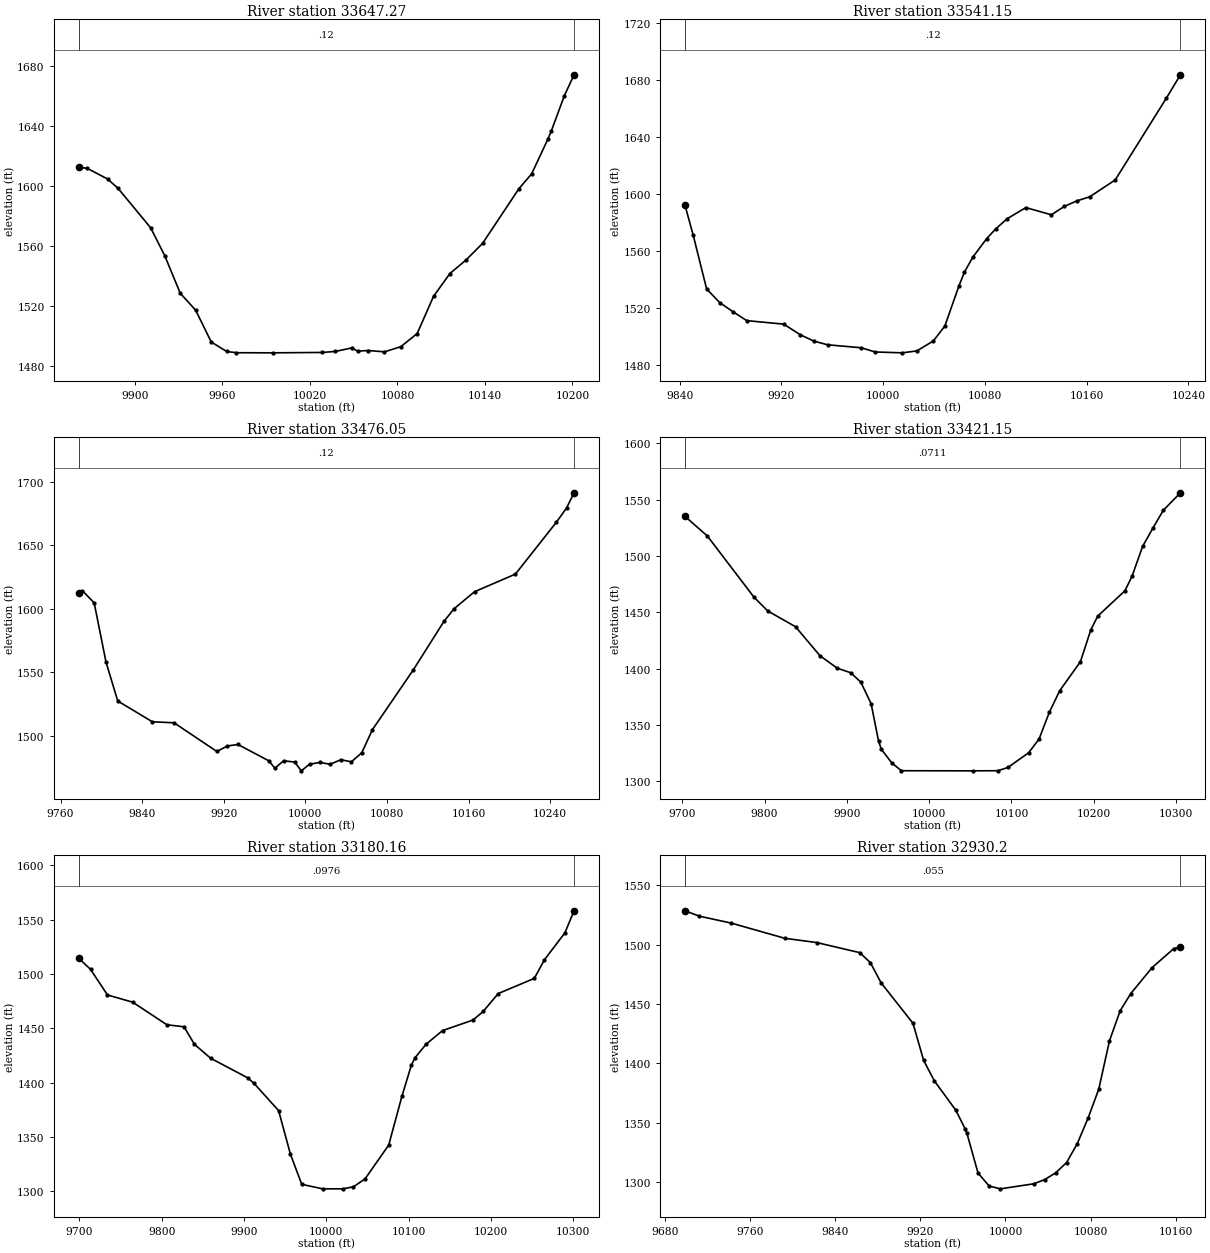
Type RM Length L Ch R = 1 ,33647.27,106.121900,106.121900,106.121900
XS GIS Cut Line= 3
704840.513904606779491.785099484 704675.50679249 779432.14397461
704529.054696981779357.923908122
#Sta/Elev= 30
9861.465 1612.289867.328 1611.559881.4261604.3689888.594 1598.119910.8441571.937
9920.4941553.3879931.127 1528.38 9941.761516.9819952.3931495.8559963.0271489.571
9969.6811488.7619994.9261488.67810028.521488.94310037.491489.605 10048.71491.954
10052.721489.79310059.911490.22610071.121489.33710082.331492.76810093.541501.502
10104.751526.26210115.961541.44810127.171550.61910138.391561.55210163.33 1598.01
10172.021607.83510183.231631.13510185.451636.23410194.441659.84710201.111673.834
#Mann= 3 , 0 , 0
9861.465    0.12       09861.465    0.12       010201.11    0.12       0
#XS Ineff= 2 , 0
       09897.103        10037.05       0
Bank Sta=9861.465,10201.11
Exp/Cntr=0.3,0.1

Type RM Length L Ch R = 1 ,33541.15,65.102900,65.102900,65.102900
XS GIS Cut Line= 5
704828.738542378779481.197719961704801.940172464779397.757340968
704788.540987492779364.259378612704677.084130943779314.316962004
704533.956473559779327.107093081
#Sta/Elev= 30
9844.2541592.2459850.7641571.0799861.2671533.523 9871.771523.8039882.2731517.422
9892.776 1511.329921.8861508.8629934.8621501.4349945.6331496.9519956.4031494.383
9982.8091492.2949993.7671489.34910015.071488.73510026.641490.10310039.531497.065
10048.561507.48210059.521535.31610063.981545.31810070.471555.67410081.431568.758
10088.441575.54910097.781582.86610112.281590.55810132.361585.523 10142.41591.348
10152.441595.28410162.481598.13610182.561609.96810222.721667.239 10233.81683.682
#Mann= 3 , 0 , 0
9844.254    0.12       09844.254    0.12       0 10233.8    0.12       0
#XS Ineff= 2 , 0
       09909.599        10036.64       0
Bank Sta=9844.254,10233.8
Exp/Cntr=0.3,0.1

Type RM Length L Ch R = 1 ,33476.05,54.904700,54.904700,54.904700
XS GIS Cut Line= 6
704850.664481342779498.251228079704807.421657205779415.419902936
 704825.00000006779351.930463329704803.158280194779300.308723196
704745.298163354779288.127645954 704537.61079669779301.526830912
#Sta/Elev= 30
9777.6661612.4179781.4161614.072 9792.951604.4459804.484 1558.049816.0181527.299
9849.9481510.948 9871.251510.1379913.191 1487.599923.5671491.9099933.9431493.066
9964.2771480.1729970.1351474.3539978.6561480.2479989.5651479.2459995.9891472.334
 10004.21477.55710014.271478.94310024.34 1477.5110034.71 1481.0410045.211479.461
10055.391486.62110065.711504.66210105.791551.67610135.85 1589.8610145.871599.936
10165.921613.265   102061627.13510246.081667.868 10256.11679.08210263.511691.129
#Mann= 3 , 0 , 0
9777.666    0.12       09777.666    0.12       010263.51    0.12       0
#XS Ineff= 2 , 0
       09867.829         10042.3       0
Bank Sta=9777.666,10263.51
Exp/Cntr=0.3,0.1

Type RM Length L Ch R = 1 ,33421.15,240.986800,240.986800,240.986800
XS GIS Cut Line= 6
705004.849711489779496.863051479704855.684820788779295.053176608
704839.295226887779269.780013224704815.456475609779225.112591284
704783.236650217779177.598323925  704654.1077823779008.435339311
#Sta/Elev= 30
9703.313  1535.3  9730.5 1517.87 9787.181463.5399804.0041451.2579837.6521437.311
9867.2871411.6019888.123  1400.69904.9471396.3679917.0271388.0439929.462 1369.02
9938.5951335.5219941.8971328.549 9954.331316.6039966.2481309.47410053.661309.373
10083.491309.484 10095.71312.36210120.86 1325.4410133.441337.49710146.021361.404
 10158.61380.51710183.771406.28110196.351434.47510204.891446.84810237.851469.232
10246.671482.46410259.251508.55810271.83 1524.8910284.411540.62110305.251556.246
#Mann= 3 , 0 , 0
9703.313  0.0711       09703.313  0.0711       010305.25  0.0711       0
#XS Ineff= 2 , 0
       09946.173        10040.79       0
Bank Sta=9703.313,10305.25
Exp/Cntr=0.3,0.1

Type RM Length L Ch R = 1 ,33180.16,249.959800,249.959800,249.959800
XS GIS Cut Line= 6
705179.820777861 779449.27732353705148.714065785779322.426107561
705113.277955252779248.273628682 705081.06212547779210.131268112
704997.017096423779139.114353312704860.531474221778956.035628654
#Sta/Elev= 30
9699.1181514.5869713.7181504.111 9734.17 1480.699764.8481474.0279806.3151453.274
9827.1271451.4239839.7791435.3379859.3571422.5389904.4481404.4869912.1681399.395
9942.0071374.3399956.4751334.0599970.1291306.5319995.4171302.417   10020 1302.38
 10032.91304.24310047.061311.58810075.771342.62610091.861387.62810103.311416.204
10107.95 1423.12   101211435.26310141.111447.92410178.211457.62610190.611465.604
10208.771481.971 10252.61495.902   10265 1513.14 10289.81537.81810300.911558.113
#Mann= 3 , 0 , 0
9699.118  0.0976       09699.118  0.0976       010300.91  0.0976       0
#XS Ineff= 2 , 0
       0                               0
Bank Sta=9699.118,10300.91
Exp/Cntr=0.3,0.1

Type RM Length L Ch R = 1 , 32930.2,249.959900,249.959900,249.959900
XS GIS Cut Line= 6
705226.601284113779378.414693922705210.467682981  779158.0982045
705216.628865461779116.485217522705243.119118572779022.535391214
705247.032089475 778987.52724151 705242.80021442778918.699706279
#Sta/Elev= 30
9699.0681528.5729712.5191524.0559742.5981518.1799792.7611505.4139822.9051501.787
9863.096 1493.339873.1381484.9429883.1411467.9979913.1521433.8119923.1681402.552
9933.2131385.3479953.4981360.4369962.1731344.778 9963.731341.405 9974.211307.758
9984.6911296.7539995.172 1294.4310026.62 1298.6810036.861302.23810047.111307.882
10057.351316.56110067.461332.59610077.521353.95110087.58 1378.3810097.631419.061
10107.631444.28210117.631458.84810137.631480.71210157.871496.61110164.241498.026
#Mann= 3 , 0 , 0
9699.068   0.055       09699.068   0.055       010164.24   0.055       0
#XS Ineff= 2 , 0
       0                               0
Bank Sta=9699.068,10164.24
Exp/Cntr=0.3,0.1

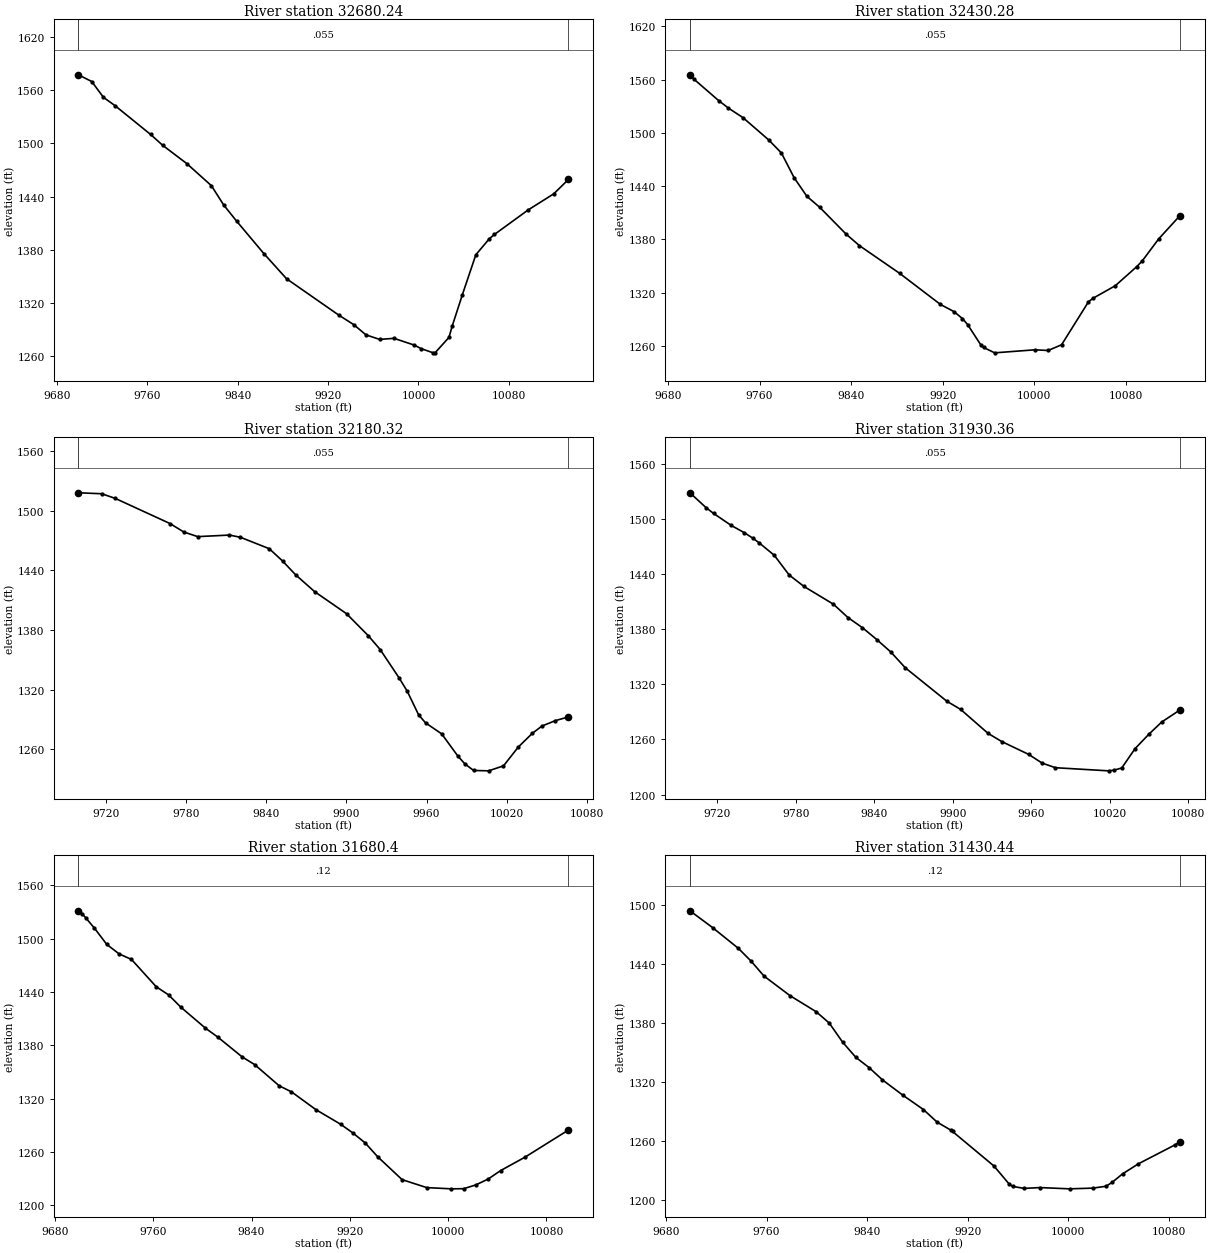
Type RM Length L Ch R = 1 ,32680.24,249.959800,249.959800,249.959800
XS GIS Cut Line= 6
705338.621211965779416.402819524705364.021718082779332.492878334
705393.095389565779266.038284604705430.844347989779199.943290238
705509.614520871779083.906696066705534.832717705779032.949228684
#Sta/Elev= 30
9699.089 1577.589710.9091569.9879721.2751552.1179731.6411542.6069763.0071510.187
 9773.581498.0599794.9821477.3359816.812 1452.349827.7271430.4489839.1421412.269
 9863.181375.7239883.3441347.1889929.6321306.0749942.8351295.3659953.538 1283.89
9965.6391278.7539978.3511279.958 9996.11  1272.410002.351268.35910012.811263.696
10014.661263.57610026.961280.94510029.991294.26510038.921329.43910050.781374.307
10062.64 1392.29 10067.21397.23510097.161425.01710119.761443.17310132.721459.397
#Mann= 3 , 0 , 0
9699.089   0.055       09699.089   0.055       010132.72   0.055       0
#XS Ineff= 2 , 0
       0                               0
Bank Sta=9699.089,10132.72
Exp/Cntr=0.3,0.1

Type RM Length L Ch R = 1 ,32430.28,249.959800,249.959800,249.959800
XS GIS Cut Line= 6
705512.676000973779568.306903959705530.048387825779524.206063037
705559.634896266779464.543274111705585.233972015 779421.04201721
705638.449598766779337.809115822705724.190150461779196.422650182
#Sta/Elev= 30
9699.0421565.3239702.5961560.3119724.0921536.3469732.6671527.8679745.587 1516.92
9767.8791492.0389779.0411477.2919790.2031449.3529801.3651428.4059812.5271416.129
9835.7131385.8129847.3161372.9099882.552 1341.639918.1591306.6869930.0281298.594
9937.3341290.8199941.8981284.0879953.7671260.5179955.8981258.2259965.5821252.202
 10000.61255.59810012.341254.85610024.091261.29710047.591309.61110051.651313.689
10071.091327.79810089.741349.154 10094.61355.62510108.961380.40510127.67 1406.78
#Mann= 3 , 0 , 0
9699.042   0.055       09699.042   0.055       010127.67   0.055       0
#XS Ineff= 2 , 0
       0                               0
Bank Sta=9699.042,10127.67
Exp/Cntr=0.3,0.1

Type RM Length L Ch R = 1 ,32180.32,249.959800,249.959800,249.959800
XS GIS Cut Line= 6
705678.227650434779742.223434344705699.984886229779644.802617207
705739.634385824779561.878296107 705783.89359194779512.315241471
705854.408271402779472.033859089 705857.37636289779445.231429979
#Sta/Elev= 30
9699.2021518.1979716.6751517.2259726.819 1512.559767.838 1487.229778.204 1478.68
9788.5711474.063 9812.361475.6269820.5441473.4089842.1611461.9199852.1131449.534
9861.9591435.5639876.1131418.7139900.032 1396.489916.3821374.2669925.2321360.397
9939.5451331.5649945.5831318.2049954.0091294.673 9959.231286.5689971.3211275.476
9983.4111253.1619988.6991245.2529995.181 1238.6710006.431238.28810017.591243.308
10028.76 1262.3810039.271276.12910046.341283.33910056.411288.82610066.231292.573
#Mann= 3 , 0 , 0
9699.202   0.055       09699.202   0.055       010066.23   0.055       0
#XS Ineff= 2 , 0
       0                               0
Bank Sta=9699.202,10066.23
Exp/Cntr=0.3,0.1

Type RM Length L Ch R = 1 ,31930.36,249.959800,249.959800,249.959800
XS GIS Cut Line= 6
706220.422651393779531.479890863 706135.12664009779482.288926817
706061.162849596779449.298218353706000.016721667779429.895691383
705894.439789531779410.941481789705872.783170371779401.771889263
#Sta/Elev= 30
9699.0621528.3659711.4861512.0789717.1381505.895 9730.66 1492.839740.5791485.003
9747.2271478.9339752.1551473.7119763.5411460.3869774.9281438.9449786.3151426.416
9808.7881407.1459819.8771392.6759830.9671381.5839841.948  1368.79852.7721354.999
 9863.68 1338.059895.5321301.5619906.0231292.7329927.006 1266.659937.4971257.733
9958.0831243.767 9968.31 1234.359978.5371229.28610019.111225.88710023.321226.622
10029.231228.98710039.341249.93910050.031265.82410059.811279.02710073.771292.142
#Mann= 3 , 0 , 0
9699.062   0.055       09699.062   0.055       010073.77   0.055       0
#XS Ineff= 2 , 0
       0                               0
Bank Sta=9699.062,10073.77
Exp/Cntr=0.3,0.1

Type RM Length L Ch R = 1 , 31680.4,249.959800,249.959800,249.959800
XS GIS Cut Line= 6
706257.978260282779175.651198619706188.464306194779168.075764897
706114.276273361779165.180384137 705958.54527341779169.395263065
705939.368580959 779170.02766611705859.816486922779174.911691261
#Sta/Elev= 30
9699.0421531.5149702.0381528.3549705.0531523.5629712.0971512.0159722.1561493.642
9732.2151482.9449742.2751476.7189762.3931445.9649772.4341436.8259782.4421422.945
9802.4571399.3049812.4651389.292 9832.481366.7829842.4881358.3059862.4951334.391
9872.4991327.5559892.5061307.3969912.5141291.0469922.5171281.1889932.5211269.984
9942.5251254.6129962.5321228.6619982.5391219.72910002.551218.32210012.551218.474
10022.561222.76610032.581229.383 10042.61238.80610062.64 1254.0810097.891284.592
#Mann= 3 , 0 , 0
9699.042    0.12       09699.042    0.12       010097.89    0.12       0
#XS Ineff= 2 , 0
       0                               0
Bank Sta=9699.042,10097.89
Exp/Cntr=0.3,0.1

Type RM Length L Ch R = 1 ,31430.44,249.959800,249.959800,249.959800
XS GIS Cut Line= 6
706142.608907315778829.090062148706039.659206131778853.635421714
705988.164987044778871.419978374705943.738252944778890.844488254
705894.337418191778920.413609648705798.195912848 778997.44500552
#Sta/Elev= 30
9699.0771494.4929717.048 1477.43 9737.461456.4219747.6661443.3689757.9731428.115
9778.703 1408.129799.4321391.8599809.8971380.2739820.4771360.9069831.0561345.357
9841.6361334.9079852.2161322.4519868.3831306.9319884.7291292.3479895.6431279.532
9906.557 1271.359907.9341269.9759940.8641234.8739952.8161216.7629955.6761214.172
9964.7691212.1099977.6181212.921   100011211.64710019.531212.37210029.981214.269
10034.841218.23410043.191226.907 10055.71237.07310084.68 1256.2610088.841259.542
#Mann= 3 , 0 , 0
9699.077    0.12       09699.077    0.12       010088.84    0.12       0
#XS Ineff= 2 , 0
       0                               0
Bank Sta=9699.077,10088.84
Exp/Cntr=0.3,0.1

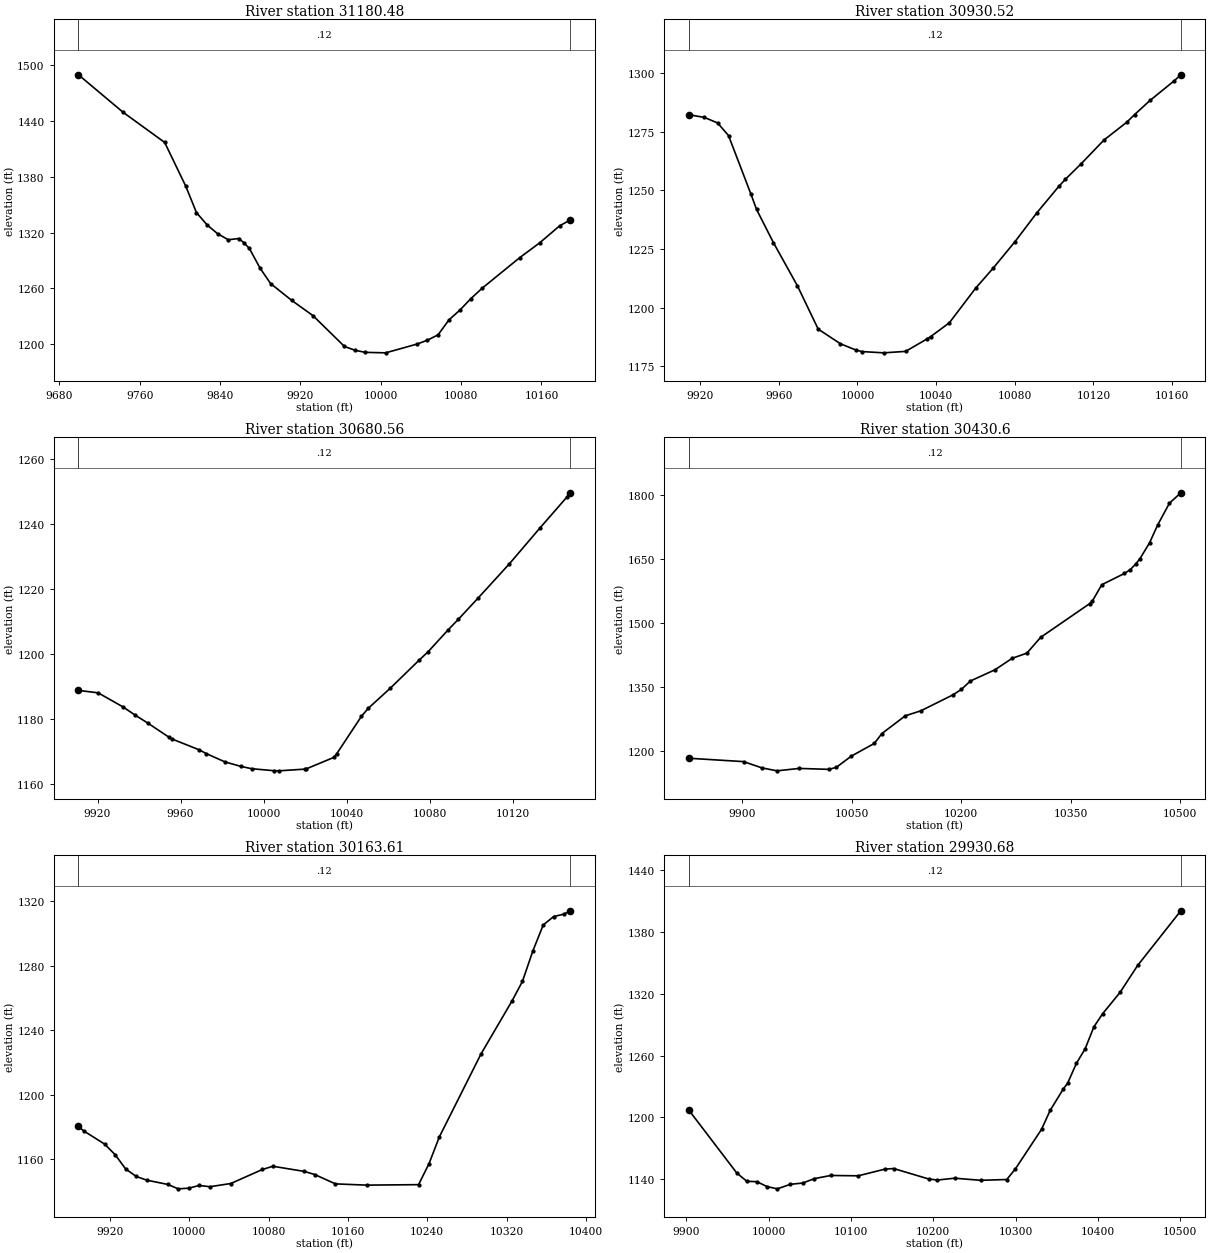
Type RM Length L Ch R = 1 ,31180.48,249.959800,249.959800,249.959800
XS GIS Cut Line= 6
706088.157609688  778628.8743367706013.218568352 778647.28266706
705850.180318862778701.789518984705746.947853553778728.505337002
705690.919187645 778754.20685514705628.485657745778790.158364707
#Sta/Elev= 30
9699.0621489.6149743.5031449.3399784.8951416.9169805.9831369.6839816.5271341.535
9827.071 1328.369837.6151318.8239848.1591312.3389858.7031313.6689863.6471309.214
9869.2471302.9469879.7911281.9499890.3351265.2529911.4241247.1119932.5121230.808
9963.8691197.6829974.232 1193.639984.5461191.33610004.891190.81710035.951200.193
10046.461204.40110057.031210.14610067.881226.23810078.741236.71410089.651249.008
10100.841260.18410138.221293.01210158.041308.882 10178.31327.49910188.631333.508
#Mann= 3 , 0 , 0
9699.062    0.12       09699.062    0.12       010188.63    0.12       0
#XS Ineff= 2 , 0
       0                               0
Bank Sta=9699.062,10188.63
Exp/Cntr=0.3,0.1

Type RM Length L Ch R = 1 ,30930.52,249.959800,249.959800,249.959800
XS GIS Cut Line= 6
705653.505083956778488.651358757705642.152432414778504.405940851
705619.077601898778546.574750834705564.791173614778658.379191703
705547.376921847778688.493947466705534.176307635778707.962142143
#Sta/Elev= 30
9914.3271282.2289922.1521281.0779928.8751278.7199934.423 1273.349945.8221248.393
9948.6461241.9329957.2211227.7859969.4771209.295 9980.021190.8839991.3091184.656
    99991182.041 10002.21181.33210013.321180.78610024.451181.40110035.581186.818
10037.231187.71710046.711193.59210060.031208.28310068.96 1216.8410080.091228.157
10091.221240.46610102.341251.67410105.631254.65310113.751261.353 10125.31271.433
10136.861278.99510140.891282.28310148.75 1288.3210160.831296.53410164.41 1299.25
#Mann= 3 , 0 , 0
9914.327    0.12       09914.327    0.12       010164.41    0.12       0
#XS Ineff= 2 , 0
       0                               0
Bank Sta=9914.327,10164.41
Exp/Cntr=0.3,0.1

Type RM Length L Ch R = 1 ,30680.56,249.959800,249.959800,249.959800
XS GIS Cut Line= 6
705440.313547939778397.306642613705415.863342299778433.407943302
705393.781442591778462.538474745705356.388306358778505.942402171
705324.095831903778539.534811584705283.850015749778573.422436179
#Sta/Elev= 30
9910.8261188.7429920.3021187.9899932.196 1183.699938.135 1181.129944.2731178.653
9954.428 1174.329955.8571173.7839968.9741170.4459972.4111169.2669981.5231166.688
9988.9651165.3679994.1511164.64310004.751164.03610007.221163.98410019.961164.518
10020.491164.59610033.761168.12610035.181169.29710047.03 1180.7710050.281183.216
10060.841189.37410074.711197.99810079.141200.66210088.581207.25210093.571210.564
10103.131217.13210118.251227.71910133.111238.86110146.091248.37910147.521249.566
#Mann= 3 , 0 , 0
9910.826    0.12       09910.826    0.12       010147.52    0.12       0
#XS Ineff= 2 , 0
       0                               0
Bank Sta=9910.826,10147.52
Exp/Cntr=0.3,0.1

Type RM Length L Ch R = 1 , 30430.6,266.994300,266.994300,266.994300
XS GIS Cut Line= 6
705391.727881759 778372.86451979705324.982605845778299.921009302
705158.902722806778261.485113129705039.838111639778207.541071743
704902.865113437778113.517299563704823.543378502778043.564220771
#Sta/Elev= 30
9827.5261182.744 9902.211174.8979927.2151160.2839947.9571153.2969978.3431158.955
10019.07 1156.7810029.311161.555 10049.81187.79410081.151217.387 10091.61240.558
10123.571282.06210145.031293.90810189.161331.39410200.451343.97110212.741363.585
10246.351389.80910269.951416.73910290.121428.83310308.951465.76110376.011544.635
10379.951551.34310392.661589.01910423.621615.31110431.791624.60210439.011637.198
10444.941649.917 10458.11687.15210469.38 1729.5510485.281779.75310500.911804.284
#Mann= 3 , 0 , 0
9827.526    0.12       09827.526    0.12       010500.91    0.12       0
#XS Ineff= 2 , 0
       0                               0
Bank Sta=9827.526,10500.91
Exp/Cntr=0.3,0.1

Type RM Length L Ch R = 1 ,30163.61,232.925300,232.925300,232.925300
XS GIS Cut Line= 3
705412.591566712778369.883993372705484.124200732778167.208196968
705400.669461012777898.960819334
#Sta/Elev= 30
9888.3511180.259 9893.531177.4859914.7391169.2399925.3441162.6629935.949  1153.8
9946.5531149.1789957.1581146.8479978.3671144.1999988.9711141.4529999.5761141.859
10010.181143.55810020.791142.76310041.991144.76110073.81 1153.4810084.411155.476
10116.071152.27710126.54 1150.3510147.481144.529 10178.91143.75910231.271144.052
10241.741156.98210252.211173.699 10294.11225.08110325.52 1258.1810335.97 1270.24
10346.471289.11610356.941305.32610367.411310.53810377.881312.08110384.211314.145
#Mann= 3 , 0 , 0
9888.351    0.12       09888.351    0.12       010384.21    0.12       0
#XS Ineff= 2 , 0
       0                               0
Bank Sta=9888.351,10384.21
Exp/Cntr=0.3,0.1

Type RM Length L Ch R = 1 ,29930.68,249.959800,249.959800,249.959800
XS GIS Cut Line= 6
705742.908425138778306.888905188705646.237738827778238.485205105
705619.193056235778203.576386446705596.410405664778156.172413337
705578.660020706778108.585934276705469.435693823777795.657248754
#Sta/Elev= 30
 9903.28 1206.679961.3261145.7469973.5571137.6559985.7881137.3099998.0191132.546
10010.611130.34210026.491134.75310041.491135.97910055.691140.30310075.561143.347
10108.851143.01110141.241149.49410151.911150.09310194.341139.967 10204.91138.883
10226.021140.69210257.711138.64110289.391139.40610299.951149.83310331.641188.253
 10342.21206.76810358.27  1227.710363.351233.11710373.991252.34910384.621266.569
10395.251287.89110405.891300.68610427.151321.51310448.421347.62710500.891400.803
#Mann= 3 , 0 , 0
 9903.28    0.12       0 9903.28    0.12       010500.89    0.12       0
#XS Ineff= 2 , 0
       0                               0
Bank Sta=9903.28,10500.89
Exp/Cntr=0.3,0.1

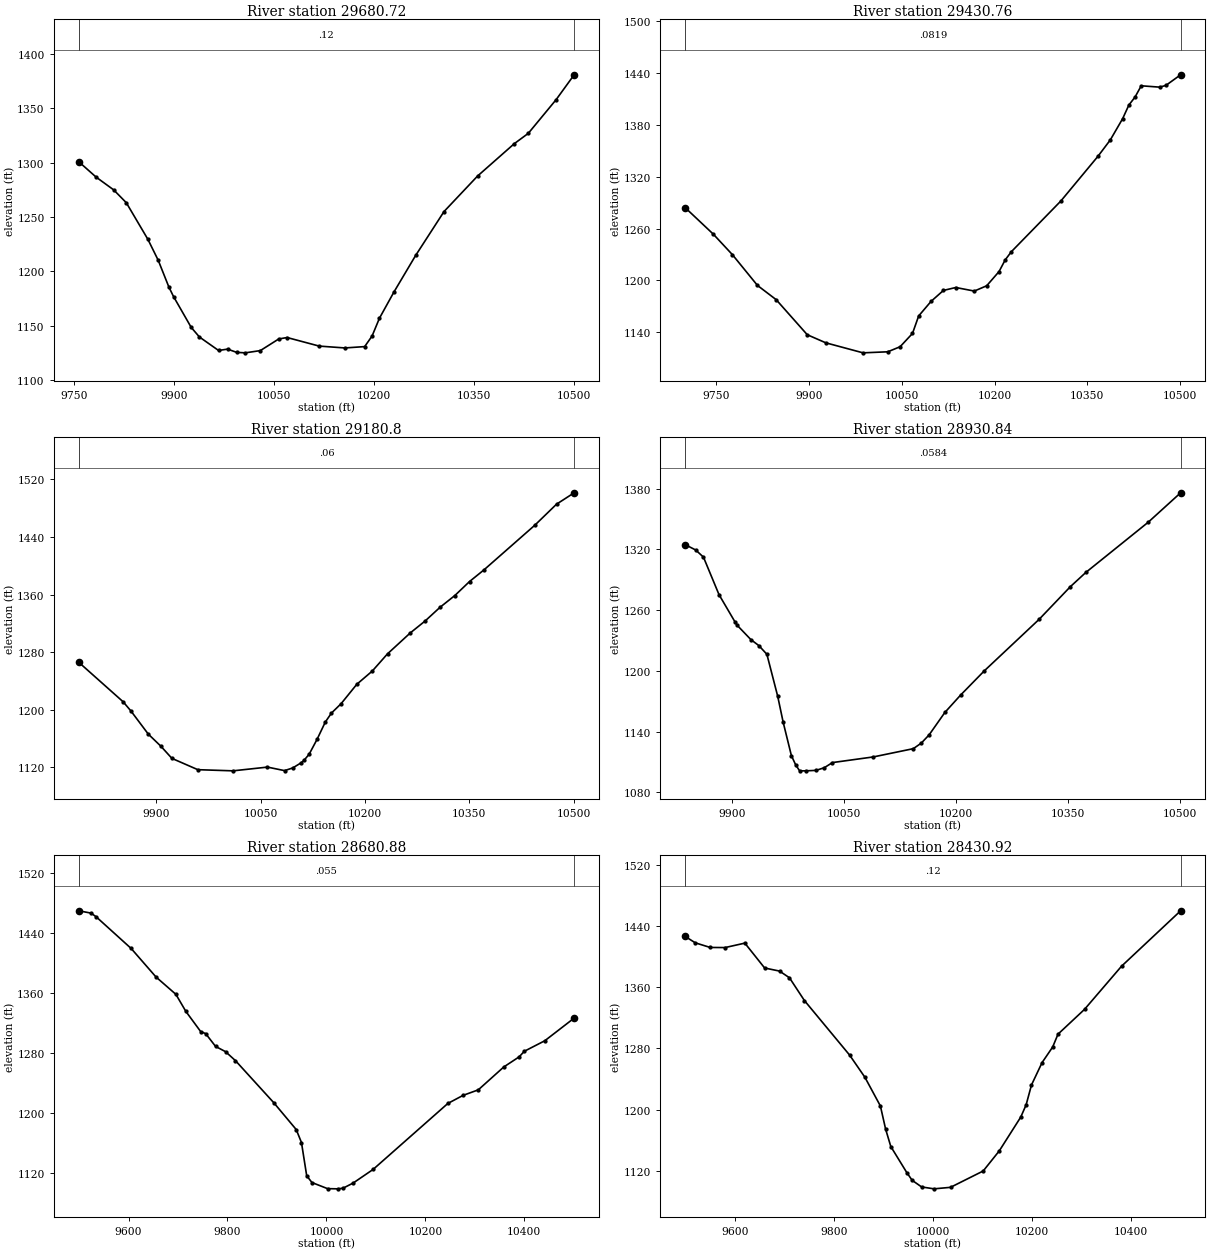
Type RM Length L Ch R = 1 ,29680.72,249.959800,249.959800,249.959800
XS GIS Cut Line= 6
706004.419364644778221.606585507  705853.9353608 778094.52204617
705822.092819397778059.561230778705752.710341221777963.022286999
705693.952915862 777843.34545766705616.250179545777609.197147924
#Sta/Elev= 30
9757.4031300.9099783.7451286.6159809.9671274.9549828.9221263.1629861.2721229.571
9876.8291210.2649892.7981185.7159899.7511176.9929926.3111148.6319938.6421139.809
9967.3661127.4289980.9341128.6689994.5011125.69410007.461125.25510030.041127.308
10057.651138.001 10070.21139.31910118.351131.452 10156.91129.74810186.571130.979
10197.711140.71910208.77 1157.0710230.561181.18410263.041214.67910305.641255.031
10356.071287.70810411.161317.42310432.09 1326.8610473.941357.88410500.931380.662
#Mann= 3 , 0 , 0
9757.403    0.12       09757.403    0.12       010500.93    0.12       0
#XS Ineff= 2 , 0
       0                               0
Bank Sta=9757.403,10500.93
Exp/Cntr=0.3,0.1

Type RM Length L Ch R = 1 ,29430.76,249.959800,249.959800,249.959800
XS GIS Cut Line= 6
706072.456659249778228.802837819706063.758867672778203.245022602
706046.192906051 778118.68200385706036.102143485778028.597803009
706030.787530722777950.418204461706027.654506237777431.250688011
#Sta/Elev= 30
9699.398 1284.44 9745.151253.5749775.9591229.8819816.512 1194.23  9846.71177.786
9897.012 1137.159927.1071127.7599987.233 1116.1810027.231117.38810047.231123.276
10067.231138.64810077.231158.93210097.241175.75910117.241188.47410137.241191.867
10167.241187.73610187.241193.85310207.241210.33310217.241223.90210227.241233.389
10307.241292.06610367.241343.84510387.241362.83610407.241387.53610417.24 1403.21
10427.241412.48610437.241425.51910467.24 1423.9510477.241426.02210500.991438.279
#Mann= 3 , 0 , 0
9699.398  0.0819       09699.398  0.0819       010500.99  0.0819       0
#XS Ineff= 2 , 0
       0                               0
Bank Sta=9699.398,10500.99
Exp/Cntr=0.3,0.1

Type RM Length L Ch R = 1 , 29180.8,249.959800,249.959800,249.959800
XS GIS Cut Line= 6
706138.382519476778235.775765342706172.068739168778147.670321877
706289.418668333777986.245066368706347.745446295777884.278220414
706398.084518352777760.104351135706444.657183912777600.506204945
#Sta/Elev= 30
9788.5281266.1559852.5611211.0759863.6561198.4149888.691 1166.19 9906.751149.405
9922.6311132.4889959.8971116.79410010.391115.18310060.031120.37110084.52 1115.49
10096.321119.19110108.111126.16210112.431129.65910119.911138.22910131.291158.919
 10143.21183.02910152.021195.44510165.83 1208.4310188.461235.43810210.73 1253.85
10232.581277.72110265.34 1306.7910286.781323.458 10308.11342.40310329.431358.771
10350.49 1378.1610371.47 1394.5410444.481456.52710475.56 1485.6210500.941501.483
#Mann= 3 , 0 , 0
9788.528    0.06       09788.528    0.06       010500.94    0.06       0
#XS Ineff= 2 , 0
       0                               0
Bank Sta=9788.528,10500.94
Exp/Cntr=0.3,0.1

Type RM Length L Ch R = 1 ,28930.84,249.959900,249.959900,249.959900
XS GIS Cut Line= 6
706394.950014926 778338.78757666706410.102917158778284.366872134
706432.093374026778227.983157763706484.312420641778113.817930243
706509.480954223778048.504676177706613.873662725777713.408571744
#Sta/Elev= 30
9837.3741324.7529851.5471319.4299861.9711312.3539882.8191275.2579903.957 1248.66
9907.3811244.8149925.425 1230.919936.1581224.9359946.8921216.3889961.3941174.861
9968.7081149.229 9979.711116.2629985.3771107.2499990.7121101.207    99991101.201
10012.721101.66110023.711104.268 10034.71109.36910089.421114.946   101431123.111
10153.651128.58710164.171136.75310185.221158.87510206.261176.01910237.831199.847
 10311.41250.85410353.161283.08210374.04 1297.2610457.551346.85310500.971375.955
#Mann= 3 , 0 , 0
9837.374  0.0584       09837.374  0.0584       010500.97  0.0584       0
#XS Ineff= 2 , 0
       0                               0
Bank Sta=9837.374,10500.97
Exp/Cntr=0.3,0.1

Type RM Length L Ch R = 1 ,28680.88,249.959800,249.959800,249.959800
XS GIS Cut Line= 6
706765.369109537778679.562559781706722.346417545778322.380629495
706672.153270422778147.696267456706663.944919795778084.561140491
706679.553023848777941.168566837706742.448863707777697.697102165
#Sta/Elev= 30
9499.0911470.1649524.133 1467.069534.3291462.2439605.2671419.8859655.5431381.807
9695.7031358.7059715.7671336.0379745.8631308.9739755.8951306.3029775.9591289.197
9796.0321282.2329816.1921270.1989893.5471214.1489938.9871178.2969949.5741161.017
9960.161 1116.689970.7481107.62410002.341099.46710023.141099.20610033.551100.046
10054.061106.93910094.431125.107 10245.51213.11810276.271223.89710307.071231.272
10358.591261.77910389.691275.30310400.051282.69910441.511296.765 10500.91327.009
#Mann= 3 , 0 , 0
9499.091   0.055       09499.091   0.055       0 10500.9   0.055       0
#XS Ineff= 2 , 0
       0                               0
Bank Sta=9499.091,10500.9
Exp/Cntr=0.3,0.1

Type RM Length L Ch R = 1 ,28430.92,249.959800,249.959800,249.959800
XS GIS Cut Line= 6
706848.044128256778705.558204454706844.441150283778535.745325925
706856.395546395778431.893736148706877.318063976778336.068990527
707004.697084216778037.453020024707111.598574547777752.678786997
#Sta/Elev= 30
9499.0671426.2849519.6971417.8249549.8021411.7899579.8431411.6489619.8591417.454
9659.883 1384.979689.9791380.9429710.0671372.2039740.274 1342.499831.6721271.231
9862.6181242.2329893.9441204.738 9904.441174.6359915.0011151.7679947.2331117.828
9958.2031107.6289977.2791099.00310002.431096.53310035.681098.49210101.791119.849
10134.341146.15510177.751190.286 10188.61206.29110199.421232.19710220.861261.468
 10242.3 1281.8210253.021298.55110306.631330.93710381.441387.27810500.981459.697
#Mann= 3 , 0 , 0
9499.067    0.12       09499.067    0.12       010500.98    0.12       0
#XS Ineff= 2 , 0
       0                               0
Bank Sta=9499.067,10500.98
Exp/Cntr=0.3,0.1

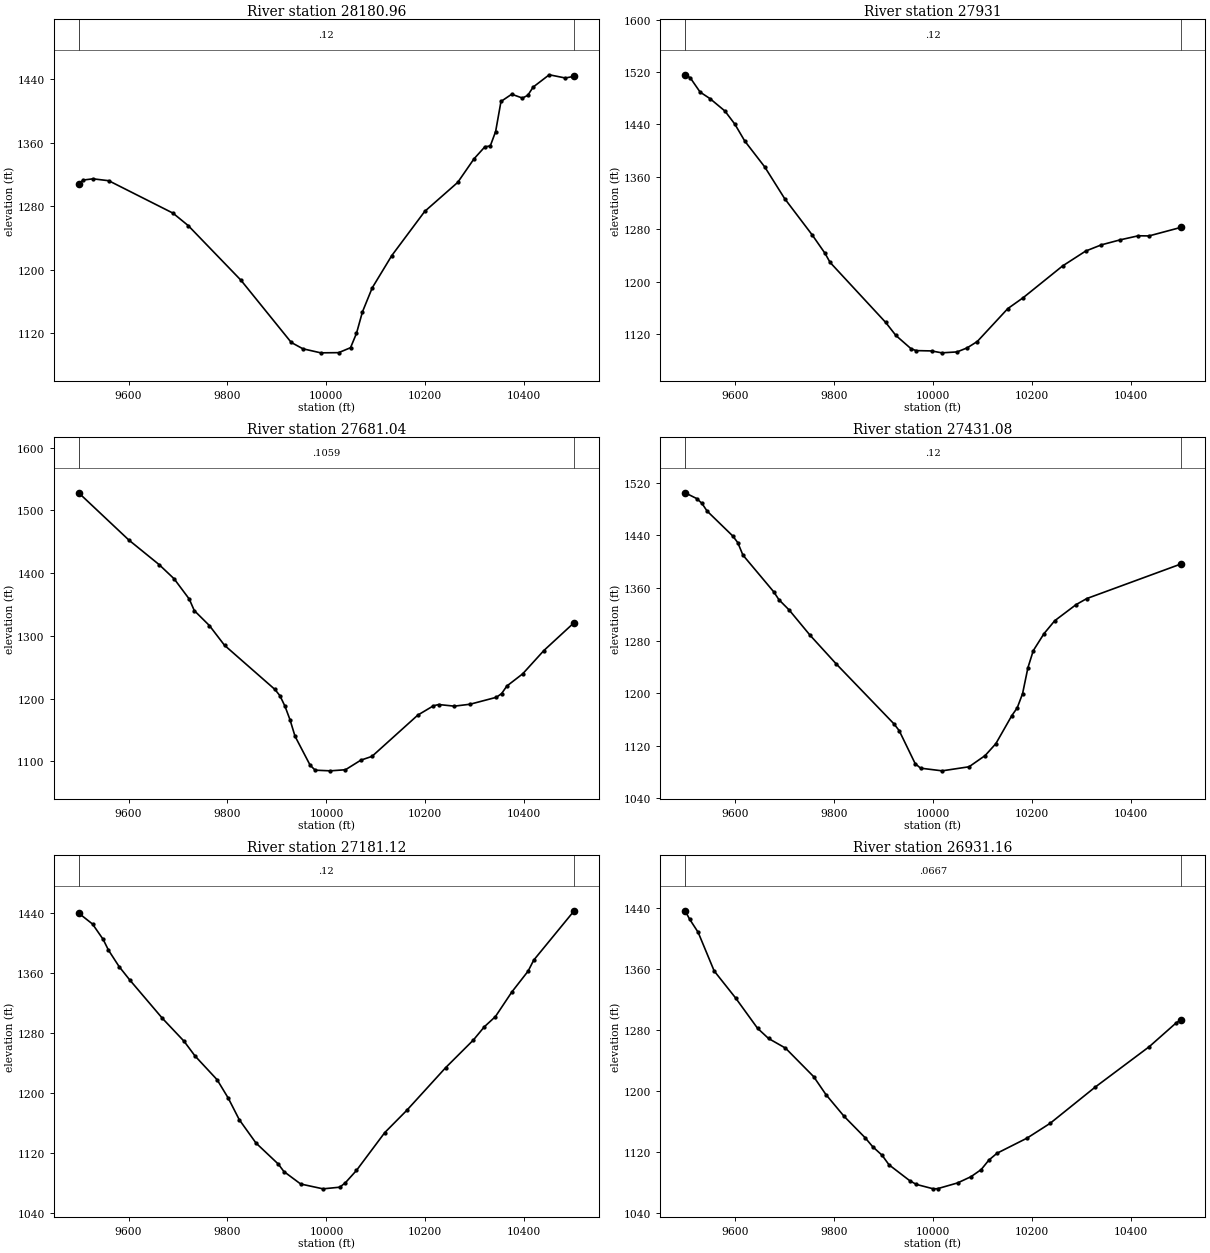
Type RM Length L Ch R = 1 ,28180.96,249.959800,249.959800,249.959800
XS GIS Cut Line= 6
706994.740833385778804.048179548707003.182262594778667.408704537
707045.126580669778515.350604242707096.693702119778409.364215991
 707237.03519073778183.154600458707367.629161749777888.464597495
#Sta/Elev= 30
 9499.091308.3319508.1381313.0939528.1381314.6599559.9751312.2639689.7481271.475
9720.6721255.7459827.4381186.8319929.0181108.5519952.5221100.5949988.586 1095.49
10024.781095.72410048.841101.97810060.871120.06710072.881147.051 10092.71177.384
10132.32 1218.0810198.781273.60510265.511310.15510298.481339.85410320.46 1355.01
10331.331356.03310342.171374.237   103531412.09110374.681421.21910396.351416.377
10407.19 1419.8310418.03  1430.210450.541445.69910483.051441.65510500.971443.759
#Mann= 3 , 0 , 0
 9499.09    0.12       0 9499.09    0.12       010500.97    0.12       0
#XS Ineff= 2 , 0
       0                               0
Bank Sta=9499.09,10500.97
Exp/Cntr=0.3,0.1

Type RM Length L Ch R = 1 ,   27931,249.959800,249.959800,249.959800
XS GIS Cut Line= 6
707274.560475475 778955.30007486707282.184136367778848.132839813
707299.932582683778724.998814566707386.759213205 778339.56682994
707425.142470945778209.028690052707508.260027472777985.173040012
#Sta/Elev= 30
9499.0521515.6679509.3781511.1569529.4291489.2359549.479 1479.259579.5551460.364
9599.6061440.3419619.7311414.5029660.0611375.0219700.2661326.7449756.3491270.906
9781.9361243.1679792.1411229.3469904.6651137.6369925.2581117.7569956.147 1097.37
9966.4441094.6719997.3331094.16810017.971091.25710048.841092.65610069.321098.834
 10089.81108.536 10151.51158.78210182.551175.38310262.181223.81410308.931246.594
10340.781256.09910379.321263.82310415.57 1269.9410436.971269.69410500.981282.621
#Mann= 3 , 0 , 0
9499.052    0.12       09499.052    0.12       010500.98    0.12       0
#XS Ineff= 2 , 0
       0                               0
Bank Sta=9499.052,10500.98
Exp/Cntr=0.3,0.1

Type RM Length L Ch R = 1 ,27681.04,249.959800,249.959800,249.959800
XS GIS Cut Line= 6
707501.451090208778965.309789096 707530.06144481778797.453997415
707601.812858185778428.346250168 707625.84523461778346.439338327
707659.708338766 778242.92355455707750.362617972777997.785522058
#Sta/Elev= 30
9499.018 1528.149600.7741452.652 9661.641413.7319692.1571390.9749722.7031358.707
9732.8851340.3489763.4311316.4919793.9771285.0779895.7961214.7379905.9781204.747
 9916.16 1188.039926.3421166.5229936.5241140.126 9967.071093.9499977.2521085.982
10007.791084.923 10038.51086.65310069.661101.95310092.171107.96110184.811173.773
10216.381188.577 10226.91190.63110258.651188.02510290.52  1191.110343.631202.149
10354.261208.09510364.881220.10810396.961239.60410439.761276.73110500.981321.215
#Mann= 3 , 0 , 0
9499.018  0.1059       09499.018  0.1059       010500.98  0.1059       0
#XS Ineff= 2 , 0
       0                               0
Bank Sta=9499.018,10500.98
Exp/Cntr=0.3,0.1

Type RM Length L Ch R = 1 ,27431.08,249.959800,249.959800,249.959800
XS GIS Cut Line= 6
707669.242410039779038.068916657707694.387779841778940.436018607
707722.101099514778845.116580164707750.863753035 778754.50801246
707783.703478469778660.350956562708016.393588334778099.644907295
#Sta/Elev= 30
9499.0211504.9769522.843 1496.069533.1691488.7189543.4961477.1799595.1271439.475
9605.5011429.2389615.9151410.234  9678.41354.2039688.8141342.2769709.721 1326.47
9751.688  1288.39804.2411244.9599921.1051153.706 9931.841143.3159964.1971093.108
9975.101 1086.1210018.741082.06210073.191088.24910105.651105.27510127.291123.344
10159.761166.20410170.581177.867 10181.41199.52310192.221238.96610203.04 1264.89
10224.681290.69510246.321310.314 10289.61334.87910311.251344.10910500.991396.496
#Mann= 3 , 0 , 0
9499.021    0.12       09499.021    0.12       010500.99    0.12       0
#XS Ineff= 2 , 0
       0                               0
Bank Sta=9499.021,10500.99
Exp/Cntr=0.3,0.1

Type RM Length L Ch R = 1 ,27181.12,249.959800,249.959800,249.959800
XS GIS Cut Line= 6
707846.166668465779091.255125503707882.555304037 778997.24043473
 707934.86960781778882.045433829708180.145170327778409.403173778
708230.007622173778307.666246328 708284.08823751 778190.75243436
#Sta/Elev= 30
9499.0381440.0789527.1911425.4069548.6371404.945 9559.361390.6539580.805 1368.75
 9602.311350.9229668.2071299.7999712.1391269.1249734.2591249.5259779.0691217.713
9801.474  1193.39823.8791164.3759857.6911133.251 9902.831105.1529914.1151095.211
 9947.971078.615 9993.111072.16210026.991074.35310038.271080.20110060.831096.739
10117.99 1147.1810162.33 1176.7510241.281233.94110297.181270.70510319.461288.444
10341.731301.94510375.111334.94410407.881362.65910419.181377.26510500.991443.137
#Mann= 3 , 0 , 0
9499.038    0.12       09499.038    0.12       010500.99    0.12       0
#XS Ineff= 2 , 0
       0                               0
Bank Sta=9499.038,10500.99
Exp/Cntr=0.3,0.1

Type RM Length L Ch R = 1 ,26931.16,249.959800,249.959800,249.959800
XS GIS Cut Line= 6
707981.553416106 779219.38401389708049.985293411779063.766505004
708113.758057239778956.277954279708320.617309594778723.343254815
708378.420823133778642.275749146708506.951624171778376.781553302
#Sta/Elev= 30
9499.0721436.2519508.1541425.2969525.4281408.0149557.8551357.2579601.1231321.848
 9645.561282.0079667.7791268.6199701.9771256.0059759.0511218.5069783.8741194.929
 9820.52 1166.449862.7261138.5479878.3891126.5429897.4711115.2469911.3261102.796
9952.8931082.1099966.2761077.122   100011071.235 10009.61071.45910049.991078.999
10077.13 1087.2110097.65 1096.4910113.291109.01510129.691117.96410190.481137.841
10237.131157.24510327.63 1204.4910437.541257.871   10492 1289.1410500.961293.033
#Mann= 3 , 0 , 0
9499.072  0.0667       09499.072  0.0667       010500.96  0.0667       0
#XS Ineff= 2 , 0
       0                               0
Bank Sta=9499.072,10500.96
Exp/Cntr=0.3,0.1

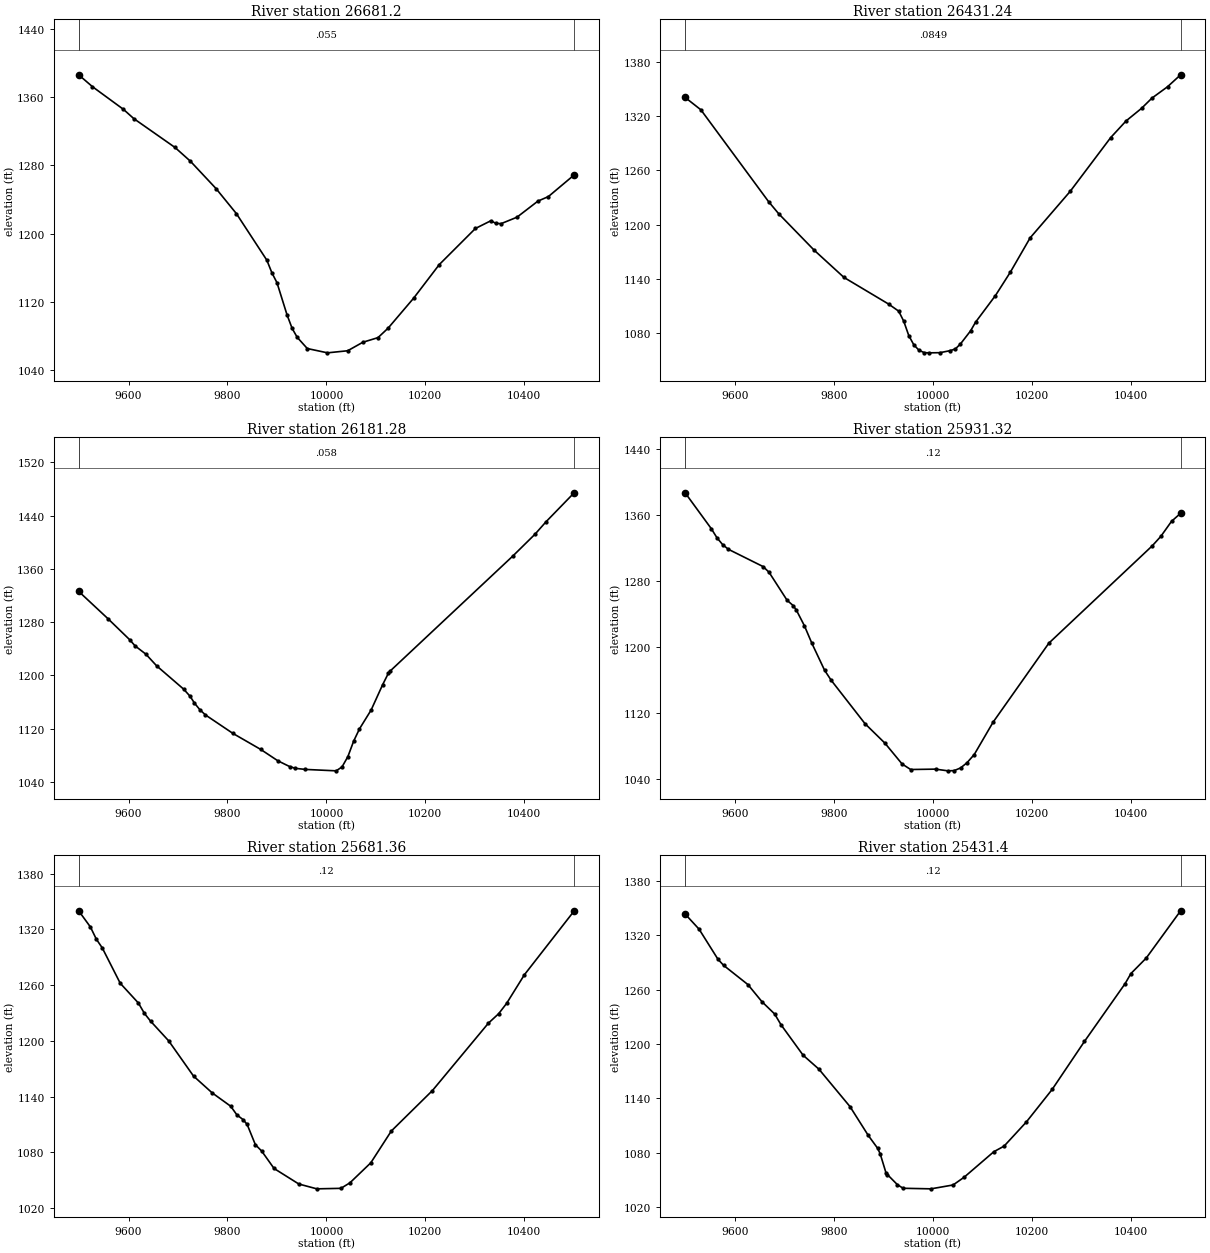
Type RM Length L Ch R = 1 , 26681.2,249.959800,249.959800,249.959800
XS GIS Cut Line= 6
708327.723921621779411.844900411708411.211754981779120.399147697
708474.594369538 778823.20399137708498.410049892778726.678153158
708538.659923989778592.654594521708589.565108715778445.727175274
#Sta/Elev= 30
9499.0151386.2669527.039 1372.289589.6731345.7259610.5511334.9139693.9611301.074
9725.0091284.9959776.7561252.9959818.0171223.597 9879.581169.043 9889.841154.184
9900.0881142.6299920.5081104.7879930.7181089.1219940.928  1078.79961.3471065.538
10002.191060.49110043.031062.93310073.651072.88310104.28  1078.310124.861089.472
10176.361124.53610228.171163.87410301.26 1206.1910332.581215.25710343.021212.047
10353.571211.92610385.321219.39410427.65 1238.2510448.821243.56610500.971268.924
#Mann= 3 , 0 , 0
9499.015   0.055       09499.015   0.055       010500.97   0.055       0
#XS Ineff= 2 , 0
       0                               0
Bank Sta=9499.015,10500.97
Exp/Cntr=0.3,0.1

Type RM Length L Ch R = 1 ,26431.24,249.959800,249.959800,249.959800
XS GIS Cut Line= 6
708643.353350685779385.162459903708720.381598668779100.981904865
708719.456203267778991.949836161708670.210020802778733.072806556
708691.193024449778582.944809211708742.047089084778409.737806859
#Sta/Elev= 30
9499.158 1341.049531.0881327.2829667.7541225.5919688.3521212.051 9759.83 1171.76
9820.2941141.4299910.5791111.8699930.9651104.0029941.158 1092.85 9951.351076.903
9961.6411066.5469972.1621060.5959982.6821057.9849993.2021057.79810014.311057.977
10035.251060.25310045.551062.17310055.851067.69810076.231082.14610086.321091.783
10126.571121.37210156.581147.20610196.631185.292 10277.51236.78510359.591296.565
10390.651315.00110421.791328.905 10442.81340.24310474.331352.83610500.88 1366.14
#Mann= 3 , 0 , 0
9499.158  0.0849       09499.158  0.0849       010500.88  0.0849       0
#XS Ineff= 2 , 0
       0                               0
Bank Sta=9499.158,10500.88
Exp/Cntr=0.3,0.1

Type RM Length L Ch R = 1 ,26181.28,249.959800,249.959800,249.959800
XS GIS Cut Line= 6
708714.969846581779369.638609335708805.950522361  779160.7923298
708857.515571217779054.350913058709041.947531432778748.661934432
709115.709182328778613.126896933709181.239258723778484.340158104
#Sta/Elev= 30
9499.0331326.2839558.6321284.9639602.2621253.553 9613.171244.3049634.9851231.854
9656.801 1214.279711.3391179.2819724.4571168.4899733.273 1158.239744.3841148.152
9755.4961140.4829811.0541112.7049867.3591088.584 9901.851071.5729925.4331062.992
9937.2461060.2319957.3541058.61210019.851056.47410031.611062.40110043.371077.726
10055.14 1101.16 10066.91119.57210090.411147.82510113.611185.75910125.211202.994
10129.31 1206.7510376.971379.358 10421.71412.07710444.141430.89410500.981474.415
#Mann= 3 , 0 , 0
9499.033   0.058       09499.033   0.058       010500.98   0.058       0
#XS Ineff= 2 , 0
       0                               0
Bank Sta=9499.033,10500.98
Exp/Cntr=0.3,0.1

Type RM Length L Ch R = 1 ,25931.32,249.959800,249.959800,249.959800
XS GIS Cut Line= 6
 708777.19207122779501.161377979708863.595977599 779354.70441614
708938.591186136779254.731357645709015.359478105779177.071293507
709243.045161841 778984.13226506709427.772067967778749.856329706
#Sta/Elev= 30
9499.0611386.9069552.0721343.4419563.5561332.394 9575.041324.1499586.5241318.548
9656.994 1297.559668.801 1290.739705.3731256.7659717.5671250.4259724.0241244.957
9740.269 1226.059755.4921204.643 9781.061172.2059794.1881160.2559862.893 1107.48
9902.9541084.0539937.8021058.7599955.152 1052.0810005.381052.54310030.421050.477
 10043.11050.772   100561053.989 10068.9 1060.19 10083.71070.23410121.751109.331
10234.571204.98710443.271322.55110460.871334.13510482.56 1352.3610500.961362.147
#Mann= 3 , 0 , 0
9499.061    0.12       09499.061    0.12       010500.96    0.12       0
#XS Ineff= 2 , 0
       0                               0
Bank Sta=9499.061,10500.96
Exp/Cntr=0.3,0.1

Type RM Length L Ch R = 1 ,25681.36,249.959800,249.959800,249.959800
XS GIS Cut Line= 6
708975.931558536779694.855408483709076.640142386779548.821169663
709244.065072965779326.877619884709299.070265194779242.829428361
709462.570149428779025.695455528709561.322973224778882.164289847
#Sta/Elev= 30
9499.0371340.0259522.8641322.5919534.8651309.4279546.8661300.048 9583.141262.025
9619.8861240.7419632.1341229.5369644.3831221.3139681.2351199.963 9731.341162.129
9768.9181144.1129806.4971129.6759819.0231120.3699831.5491115.2749839.7761110.074
9856.381  1088.39869.1281081.452 9894.181062.6849944.2851045.9639980.5961040.784
10029.321041.32310047.511047.23210089.751068.79410131.271103.00910214.391146.567
10327.571219.08410348.281229.25210364.29 1240.3110400.31 1271.1610500.961339.884
#Mann= 3 , 0 , 0
9499.037    0.12       09499.037    0.12       010500.96    0.12       0
#XS Ineff= 2 , 0
       0                               0
Bank Sta=9499.037,10500.96
Exp/Cntr=0.3,0.1

Type RM Length L Ch R = 1 , 25431.4,249.959800,249.959800,249.959800
XS GIS Cut Line= 6
709187.845057829779827.971264486709370.473854893779596.144399251
709422.468397708779523.683797565709456.155417142779466.265939309
709556.998564458779272.009624183709731.574532476778989.510539353
#Sta/Elev= 30
 9499.061343.3329527.4121326.5059565.5931293.3289576.9931286.631 9626.061265.449
9654.4381246.5769680.1181233.0149692.9581221.1469737.6561187.5469769.5411172.203
9832.5431130.8049869.4671098.9959888.3981084.8469893.4631078.8199905.0571058.135
9908.159 1055.859928.2451044.7729939.8391040.7659996.2581040.14510040.931044.411
10063.261052.95210123.291081.09910144.021087.26310188.871113.78510241.171149.774
10306.431202.68810388.711266.49610400.471277.63410431.391294.69310500.971346.857
#Mann= 3 , 0 , 0
 9499.06    0.12       0 9499.06    0.12       010500.97    0.12       0
#XS Ineff= 2 , 0
       0                               0
Bank Sta=9499.06,10500.97
Exp/Cntr=0.3,0.1