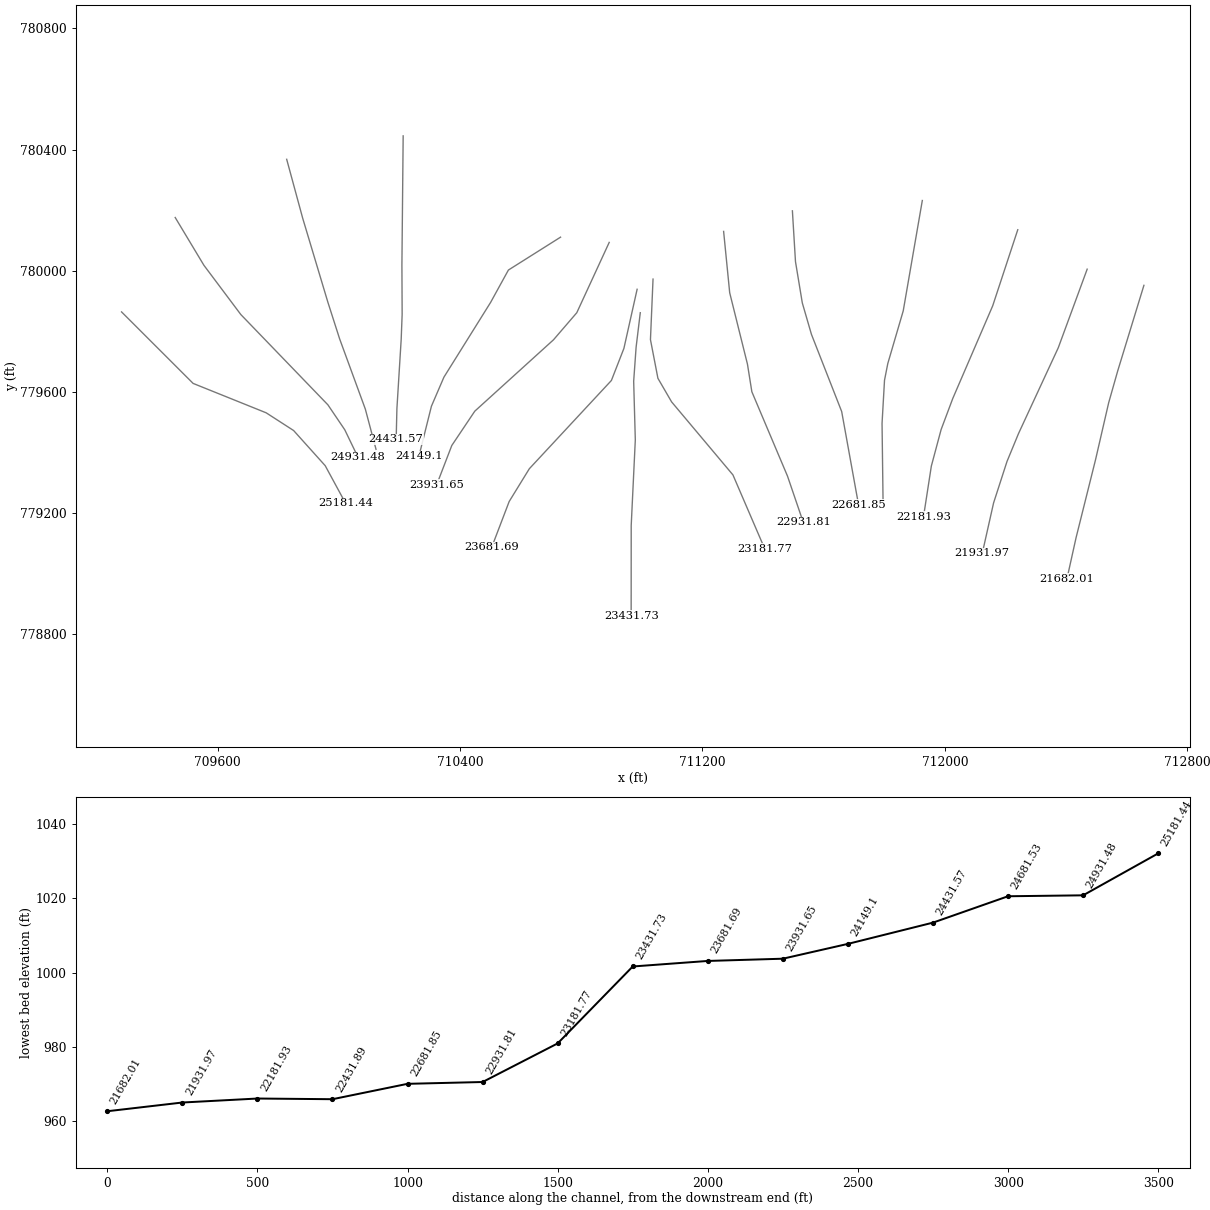
HEC-RAS study 14536_ras.prj: 14536

--- 14536_ras.g01 (geometry) --- (continued)

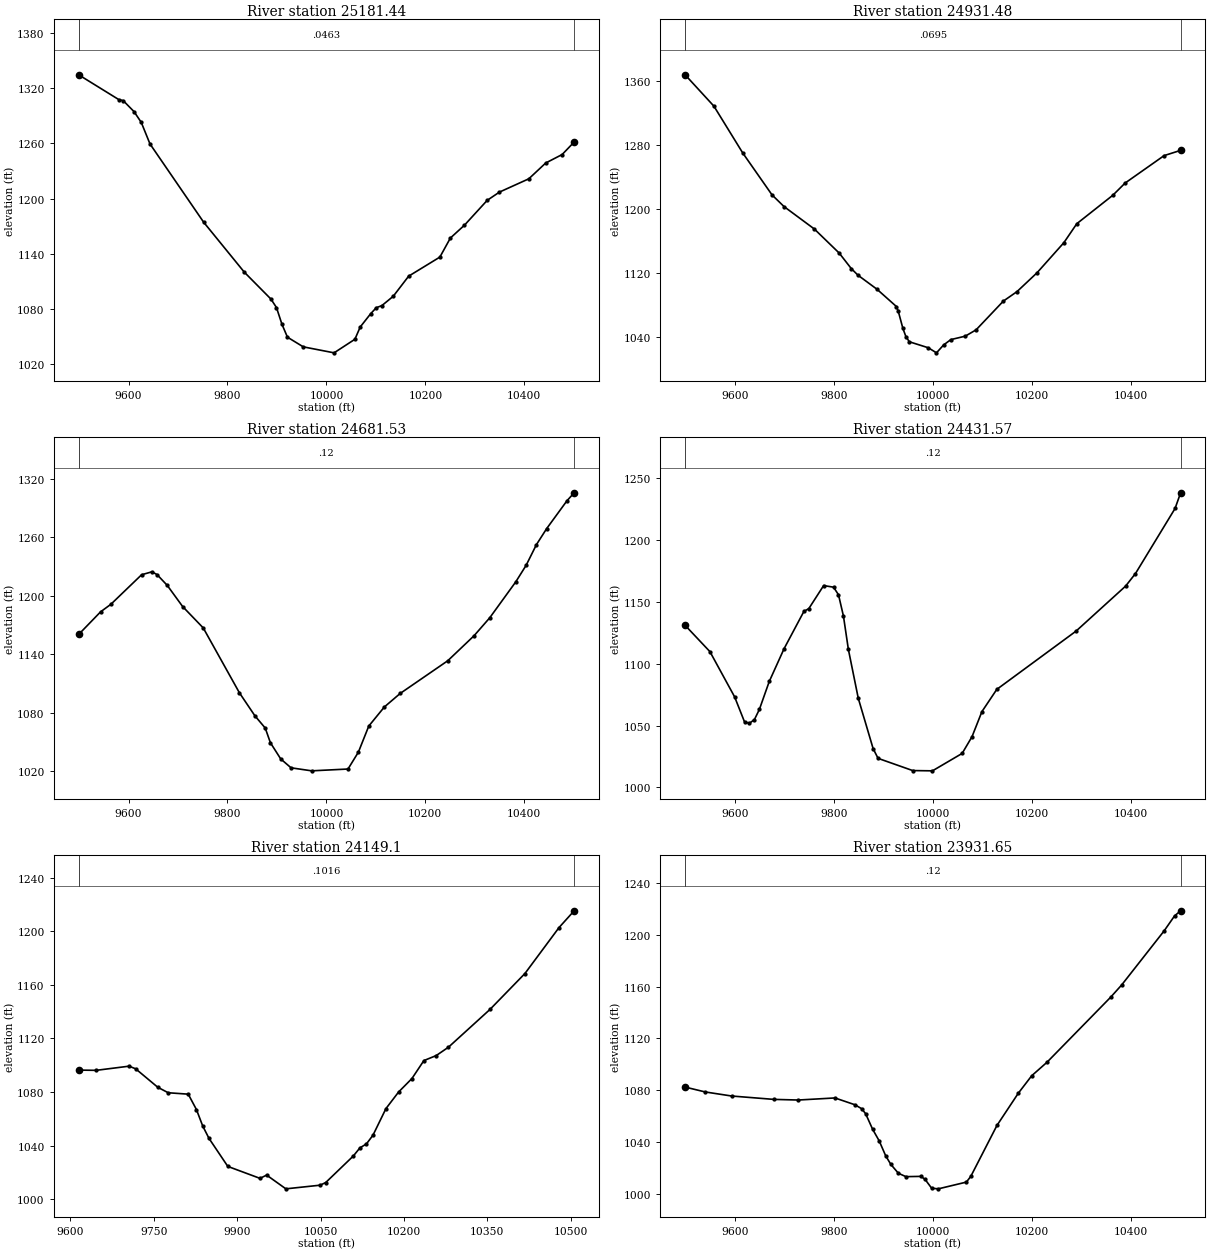
Type RM Length L Ch R = 1 ,25181.44,249.959800,249.959800,249.959800
XS GIS Cut Line= 6
709283.014055651779864.233054424709519.139017243779628.286247437
709760.256401465779531.244657899709850.852401609 779472.74683476
709955.024693774779356.805469062710022.145651187779233.066300398
#Sta/Elev= 30
 9499.141334.7549580.4531307.7049589.1781306.6439611.1381294.645  9625.71282.983
9643.4011259.4619751.871 1174.279834.0361119.9039887.9251090.5869899.0351081.404
9910.1451063.1869921.2541049.1089953.2691038.59610015.52 1032.0810057.581046.849
10068.331060.20110089.831074.89810100.841081.21110112.141083.51510135.051093.621
10166.281115.54810229.371136.31410250.621157.06110279.141171.07110324.99 1198.06
10349.771207.05810409.111221.507 10443.31238.71310476.541247.95410500.841261.573
#Mann= 3 , 0 , 0
 9499.14  0.0463       0 9499.14  0.0463       010500.84  0.0463       0
#XS Ineff= 2 , 0
       0                               0
Bank Sta=9499.14,10500.84
Exp/Cntr=0.3,0.1

Type RM Length L Ch R = 1 ,24931.48,249.959800,249.959800,249.959800
XS GIS Cut Line= 6
709460.046236405780175.735854528709554.758200223 780018.11763778
709676.637020876779855.495991352709964.066433079779557.435800564
710019.610773813779475.252382738710063.361698933779384.510025062
#Sta/Elev= 30
9499.0571367.8859557.3711328.6829615.6991270.1999674.8531217.9329699.0691203.374
9760.3341175.3759810.597 1145.349835.0891125.9319848.7561117.6139886.934 1100.24
9926.2681078.6189930.1371072.572 9939.381051.2839945.5981040.8919952.4911034.599
9990.863 1027.1110007.321020.79810021.861030.72510036.391037.32710065.471041.604
10087.431049.52610142.541085.402 10170.11097.21710210.571120.71610264.83 1158.27
10290.991181.98810363.85 1217.5110388.711232.74610467.55    126710500.941273.539
#Mann= 3 , 0 , 0
9499.057  0.0695       09499.057  0.0695       010500.94  0.0695       0
#XS Ineff= 2 , 0
       0                               0
Bank Sta=9499.057,10500.94
Exp/Cntr=0.3,0.1

Type RM Length L Ch R = 1 ,24681.53,249.959800,249.959800,249.959800
XS GIS Cut Line= 6
709827.921155639780367.863732645709880.743325811 780173.48282458
709963.664433215779896.785204468710002.539931773779775.547110135
710087.500771247779543.377590725710122.701745282779410.912254727
#Sta/Elev= 30
9499.0131160.2229543.4311183.4369564.1561191.1399626.3321221.4249647.0571224.403
 9657.421221.6549678.1451210.5639709.2981188.8699751.0561166.8899824.1321100.474
 9855.451076.9059876.3291064.3689886.7681049.3369907.6471032.7389928.5261023.642
9970.2831020.54810043.661022.41310064.67 1039.7110085.681066.423 10117.21085.981
10149.261099.85310245.451133.34810298.641158.99110330.391177.41510382.991214.225
10403.811231.06210424.631252.25510445.381268.71110486.491297.26910500.971305.389
#Mann= 3 , 0 , 0
9499.013    0.12       09499.013    0.12       010500.97    0.12       0
#XS Ineff= 2 , 0
       0                               0
Bank Sta=9499.013,10500.97
Exp/Cntr=0.3,0.1

Type RM Length L Ch R = 1 ,24431.57,282.468400,282.468400,282.468400
XS GIS Cut Line= 6
710212.321627881780445.146172727710208.167262189780019.397533889
710208.959378844779856.329316639710205.795648468779773.976013806
710191.640837532779544.531969159710189.215025742779443.742522813
#Sta/Elev= 30
9499.0141131.1339549.162 1109.879599.165 1073.259619.166 1053.049629.1661051.935
9639.1661054.8849649.1671063.0789669.168 1085.719699.1691112.2539739.1711142.346
9749.1721144.6579779.1731163.2819799.1741161.9659809.175 1155.859819.1751138.637
9829.1761111.6149849.1761072.1269879.1781031.4389889.1781023.5469959.181 1013.67
9999.1831013.44910059.19 1027.5410079.191041.08910099.191061.35910129.221079.316
10289.471126.43110389.661162.82710409.691173.02410489.711225.63610500.971238.311
#Mann= 3 , 0 , 0
9499.014    0.12       09499.014    0.12       010500.97    0.12       0
#XS Ineff= 2 , 0
       0                               0
Bank Sta=9499.014,10500.97
Exp/Cntr=0.3,0.1

Type RM Length L Ch R = 1 , 24149.1,217.451300,217.451300,217.451300
XS GIS Cut Line= 6
710731.677862316780110.902957067710559.602969497780002.400735199
710500.793605536779895.470226243710346.860037774779649.020645484
710305.570418894779553.008568019710264.374228269 779388.24733907
#Sta/Elev= 30
9615.125 1096.399646.6641096.2099705.7741099.3129717.5961097.3679757.4331083.567
9776.1821079.4779812.1721078.4229826.9031066.9569838.1871054.6869849.4711045.429
9883.3231024.4899941.1831015.5719953.1351018.0049987.7121007.74510049.251010.469
10059.351012.45210109.031032.286 10120.81038.31910132.571041.29710144.341047.799
10167.621067.64710190.411080.04910214.391090.10910235.83  1103.510257.931107.216
10279.991113.47910354.821141.73710417.481168.47310478.831202.80910506.031215.321
#Mann= 3 , 0 , 0
9615.125  0.1016       09615.125  0.1016       010506.03  0.1016       0
#XS Ineff= 2 , 0
       0                               0
Bank Sta=9615.125,10506.03
Exp/Cntr=0.3,0.1

Type RM Length L Ch R = 1 ,23931.65,249.959800,249.959800,249.959800
XS GIS Cut Line= 6
710892.256648647  780093.6161343710785.269674734779861.551360998
710708.483577022779772.287903704710448.649178554779536.643823217
 710372.76828083779423.390538711710322.729850968779293.280642125
#Sta/Elev= 30
 9499.121082.3449539.8831078.5689593.1851075.4429678.4981072.8339727.828 1072.34
9802.0641073.9449842.2321068.7129856.0311065.6559864.1151061.7589878.1931049.783
9891.4581040.8279904.7231029.1859915.1031022.5969930.3231015.7599945.5421013.157
9975.9821013.3629984.3141011.013 9997.581004.20610011.071003.74110067.781008.949
10076.71 1013.3810129.621052.74210172.751077.60410199.841091.10110230.631101.479
 10359.41151.74410381.681161.21210467.641203.04810488.621214.56710500.911218.516
#Mann= 3 , 0 , 0
 9499.12    0.12       0 9499.12    0.12       010500.91    0.12       0
#XS Ineff= 2 , 0
       0                               0
Bank Sta=9499.12,10500.91
Exp/Cntr=0.3,0.1

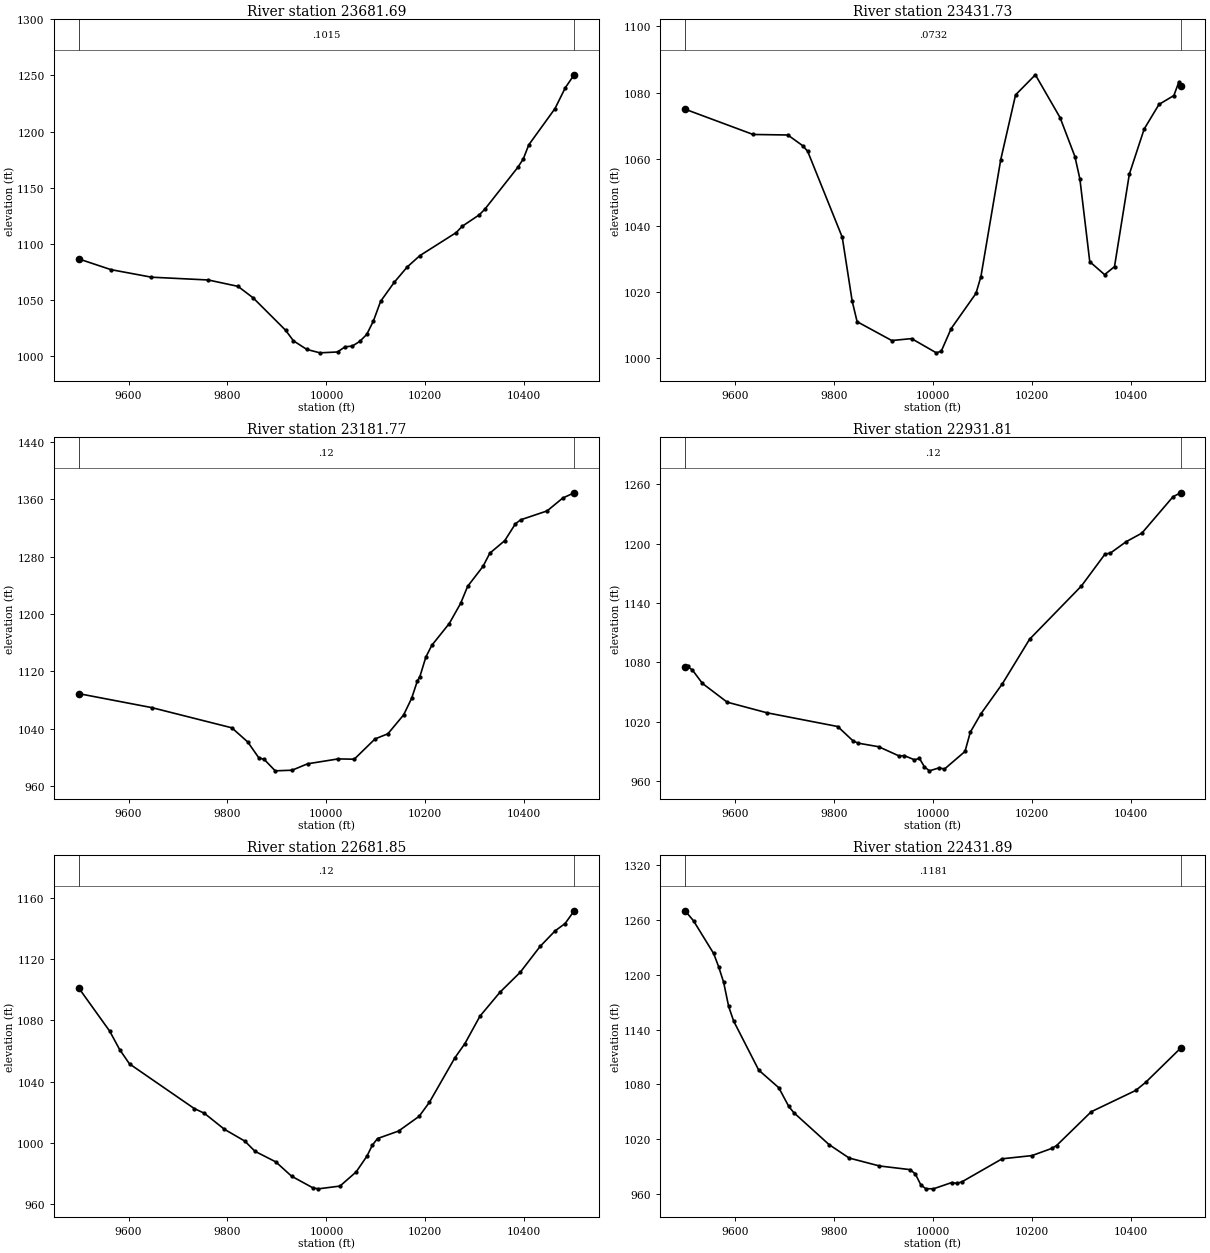
Type RM Length L Ch R = 1 ,23681.69,249.959800,249.959800,249.959800
XS GIS Cut Line= 6
  710984.3949411779938.961978104710940.745075274779743.754129716
 710899.52833034 779638.03638688710628.676206519779346.741354378
710562.155115455779238.565789197710504.658673606779087.902142035
#Sta/Elev= 30
9499.1081086.763 9564.361077.193 9646.391070.4639761.1691067.982 9821.291062.304
9852.0021052.0319917.6851023.1769933.2741013.8769960.4341006.1579986.9581003.137
10022.481003.90910037.731008.50110052.441009.16510067.431013.32310081.531019.504
10095.041031.49710109.621048.97610136.961065.78210163.251079.498 10188.91089.629
10262.541110.20210274.571115.77910309.18 1125.9910320.611131.13210387.151168.326
10398.111175.77710409.071188.21810462.141220.53510483.041239.13110500.911250.607
#Mann= 3 , 0 , 0
9499.108  0.1015       09499.108  0.1015       010500.91  0.1015       0
#XS Ineff= 2 , 0
       0                               0
Bank Sta=9499.108,10500.91
Exp/Cntr=0.3,0.1

Type RM Length L Ch R = 1 ,23431.73,249.959800,249.959800,249.959800
XS GIS Cut Line= 6
710994.809517473 779861.59996067710981.025636336779747.734922607
710972.988172869779635.385749733 710978.40274464779441.874730361
710964.860599134779159.191202303710964.687375847778861.292622828
#Sta/Elev= 30
9499.0721075.0599636.561 1067.44 9706.741067.287 9736.791064.064 9746.791062.407
9816.8141036.4739836.8341017.2729846.8451011.0349916.9161005.3559956.9691005.935
10007.041001.64610017.051002.15910037.091008.97210087.171019.56110097.181024.621
10137.221059.83110167.24 1079.3710207.261085.42710257.261072.50710287.261060.776
10297.261054.04310317.271029.10310347.271025.20310367.27 1027.6210397.271055.489
10427.271069.09510457.271076.50610487.281079.16910497.28 1083.2110500.981082.013
#Mann= 3 , 0 , 0
9499.072  0.0732       09499.072  0.0732       010500.98  0.0732       0
#XS Ineff= 2 , 0
       0                               0
Bank Sta=9499.072,10500.98
Exp/Cntr=0.3,0.1

Type RM Length L Ch R = 1 ,23181.77,249.959800,249.959800,249.959800
XS GIS Cut Line= 6
711036.888434579779972.551613378 711028.37231485779772.815564315
711053.004079449779645.103629805711098.188491806779567.282116589
711300.600784946779326.297525653711405.214397056779083.081640166
#Sta/Elev= 30
9499.1431088.8089647.0151069.259 9808.881041.0379841.0051021.2759863.174999.3574
9874.473996.80499896.547980.9466 9930.68981.83599961.906 990.76510023.92997.6294
10056.33997.193810098.36 1025.5310124.341032.70710156.12 1059.0610172.351082.258
10183.651105.95110189.021112.64910201.021139.76610213.021156.20210248.391186.727
10271.281214.74810285.631238.75710316.531266.44110330.341284.94510360.621302.533
10382.161326.06710392.931331.64710446.231344.03510477.831362.01410500.911369.361
#Mann= 3 , 0 , 0
9499.143    0.12       09499.143    0.12       010500.91    0.12       0
#XS Ineff= 2 , 0
       0                               0
Bank Sta=9499.143,10500.91
Exp/Cntr=0.3,0.1

Type RM Length L Ch R = 1 ,22931.81,249.959800,249.959800,249.959800
XS GIS Cut Line= 6
711269.818115818780129.907642871711289.884775655779927.400754232
711348.495260353779691.780540169711362.969559978779600.791584664
711480.699670317779322.214053767711532.502122003779170.344093874
#Sta/Elev= 30
9499.0851075.5399504.0031075.9259514.0221072.2289534.0611058.8359584.1581039.861
9664.7691029.1239807.6571015.2889838.7211000.7469849.075998.48819890.493994.8729
 9931.91985.53049942.265985.93799962.685981.69379972.868 983.1289982.966974.5702
9993.025970.553410013.14 973.63110023.29972.268510064.98 990.11810075.721009.588
10097.141028.12710140.691058.54110195.541103.37210300.221157.05110348.141189.364
10358.821190.27510390.881201.85510422.621210.47310485.571247.22310500.941251.199
#Mann= 3 , 0 , 0
9499.085    0.12       09499.085    0.12       010500.94    0.12       0
#XS Ineff= 2 , 0
       0                               0
Bank Sta=9499.085,10500.94
Exp/Cntr=0.3,0.1

Type RM Length L Ch R = 1 ,22681.85,249.959800,249.959800,249.959800
XS GIS Cut Line= 6
711496.802146306780197.796686957711506.974872991780030.128393461
711529.489537297779893.898188756711559.618860398779790.190615493
711659.436709154779535.391604098 711715.22718951779226.863347262
#Sta/Elev= 30
9499.0571101.3239561.9081073.0099581.9251061.0419601.9431051.6459732.8491022.495
9753.1181019.4399793.8951008.9369835.0651001.2449855.726994.55779897.675987.6709
9929.602978.32459972.817  970.699983.767970.066110027.47971.877410060.19981.1166
   10082991.432710092.78998.532910103.411002.91410145.851007.799 10187.61017.442
 10208.21026.55310259.591055.53710279.981064.88910310.571082.86310351.231098.556
10391.781111.42910432.191128.39910462.471138.54210482.651143.32410500.961151.635
#Mann= 3 , 0 , 0
9499.057    0.12       09499.057    0.12       010500.96    0.12       0
#XS Ineff= 2 , 0
       0                               0
Bank Sta=9499.057,10500.96
Exp/Cntr=0.3,0.1

Type RM Length L Ch R = 1 ,22431.89,249.959800,249.959800,249.959800
XS GIS Cut Line= 6
711925.546488015 780231.89631051711862.540521194779867.671707722
711811.587295537779693.808213275711800.779826697779638.817032454
 711792.64329185779496.396849314711795.893071239 779244.28799142
#Sta/Elev= 30
 9499.041269.7689516.1631258.7459556.7011223.1279566.8351208.726 9576.971191.601
9587.1041165.2379597.2391149.1929647.9111095.6579688.4491076.4139708.718  1055.9
9718.8521049.1679790.0171014.3159830.715 999.5859892.044990.91269953.917986.9086
 9964.47982.26469975.513970.37289985.575966.1088   10001965.924810038.24972.8194
10048.76971.842310058.99973.656110140.02998.761210200.151002.22110240.17 1010.06
10250.171013.26910320.171050.16910410.191073.46710430.191082.27710500.921119.668
#Mann= 3 , 0 , 0
 9499.04  0.1181       0 9499.04  0.1181       010500.92  0.1181       0
#XS Ineff= 2 , 0
       0                               0
Bank Sta=9499.04,10500.92
Exp/Cntr=0.3,0.1

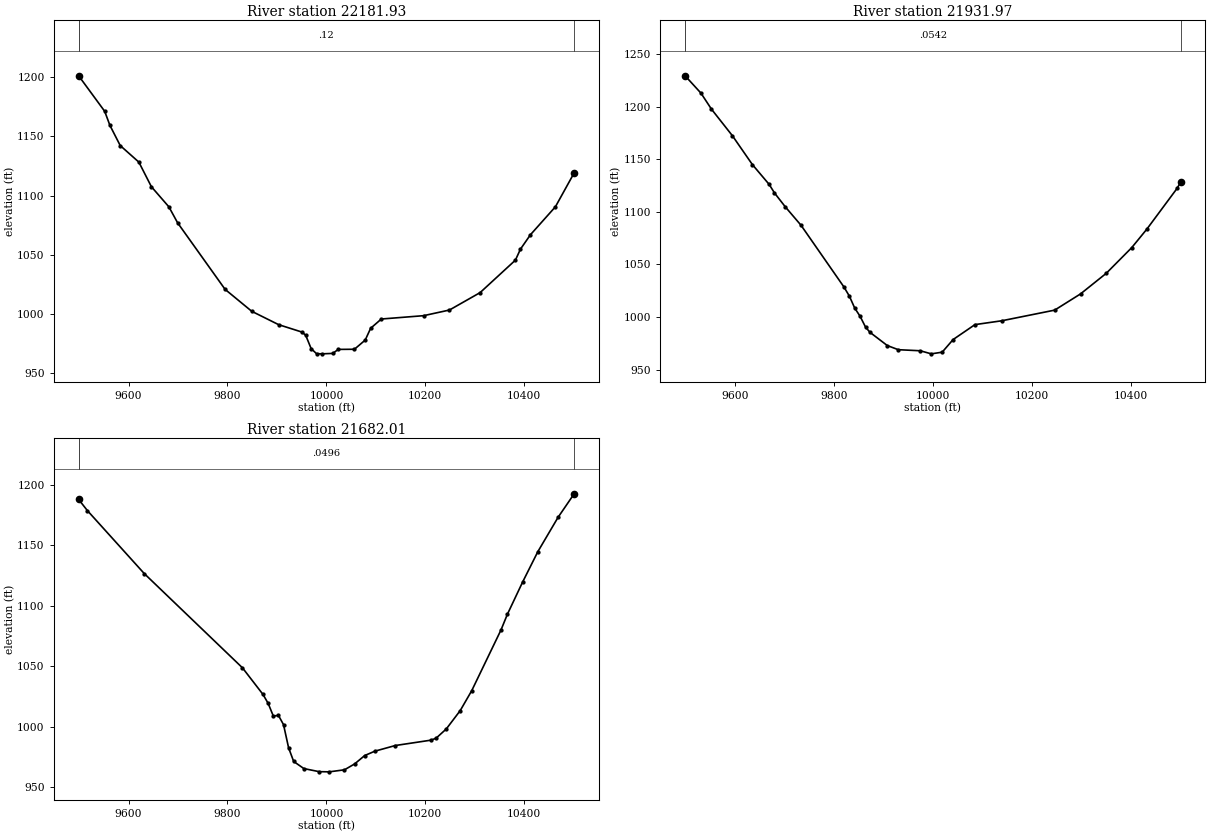
Type RM Length L Ch R = 1 ,22181.93,249.959800,249.959800,249.959800
XS GIS Cut Line= 6
712240.526435404780135.432622287712157.758470293779884.243304394
712025.987347195779578.475805818711987.619880724779476.184846533
711955.303523833779355.433258904711929.339215384779187.401557256
#Sta/Elev= 30
 9499.031201.2799551.7571171.2149562.2121159.3919583.1221142.2559620.7941128.263
9646.1471107.453 9681.511090.4319699.1541076.9199795.1211020.6539849.0781002.076
9903.436990.78349950.837984.47799958.185981.76779969.135970.53769980.085966.2203
9991.034966.107410012.92966.475910023.85969.857710056.64 969.986 10078.5977.7504
10089.43987.714110111.06995.558910196.49998.380210248.751003.16310310.761017.888
10382.181045.36810392.361054.664 10412.61066.86710463.031090.48410500.961119.167
#Mann= 3 , 0 , 0
 9499.03    0.12       0 9499.03    0.12       010500.96    0.12       0
#XS Ineff= 2 , 0
       0                               0
Bank Sta=9499.03,10500.96
Exp/Cntr=0.3,0.1

Type RM Length L Ch R = 1 ,21931.97,249.959800,249.959800,249.959800
XS GIS Cut Line= 6
712469.580252021780005.308722991712374.174618515779745.925284075
712242.856723407779462.490555067712204.981403816779370.665080486
712160.746140303779234.016531408712123.467374421779068.107610408
#Sta/Elev= 30
9499.028 1229.349531.106 1212.849552.2741197.653 9594.611172.3969635.1291144.904
9669.0291126.0659679.7711117.9649701.2551104.9739733.4821087.2039820.1541028.604
9831.0761019.9789841.9971008.5129852.9191000.6719863.841990.47049872.888985.4586
9907.916972.89679930.111968.9735  9974.5967.96029996.695965.0351 10018.8966.5978
 10040.9978.6085 10085.1992.816710139.24996.459510246.231006.578 10298.51021.991
10350.481041.54410402.041065.97710432.671083.58310493.92 1122.4110500.961128.261
#Mann= 3 , 0 , 0
9499.028  0.0542       09499.028  0.0542       010500.96  0.0542       0
#XS Ineff= 2 , 0
       0                               0
Bank Sta=9499.028,10500.96
Exp/Cntr=0.3,0.1

Type RM Length L Ch R = 1 ,21682.01,249.959800,249.959800,249.959800
XS GIS Cut Line= 6
712656.801958008779951.950185665712570.401037197779669.722423898
712540.550911991 779564.60442652712497.149246445779376.437080303
712432.888448084 779119.08291544712402.769241872778983.205048863
#Sta/Elev= 30
9499.0161187.8149516.7431178.5669631.7821126.4989830.2681048.648 9871.851026.629
9882.2451019.2449892.6411008.8469903.0361009.3119913.3141001.6719923.588982.5046
9933.861971.25519954.408965.39079985.228962.840910005.76962.687510036.52964.3604
10057.02969.215210077.53976.178510098.04 979.76910139.27984.433710211.42988.8656
10221.72990.473110242.34998.090410270.541013.27610293.871029.776 10353.11080.002
10365.991092.91510396.721119.50310427.451144.57910468.421173.00910500.991192.469
#Mann= 3 , 0 , 0
9499.016  0.0496       09499.016  0.0496       010500.99  0.0496       0
#XS Ineff= 2 , 0
       0                               0
Bank Sta=9499.016,10500.99
Exp/Cntr=0.3,0.1