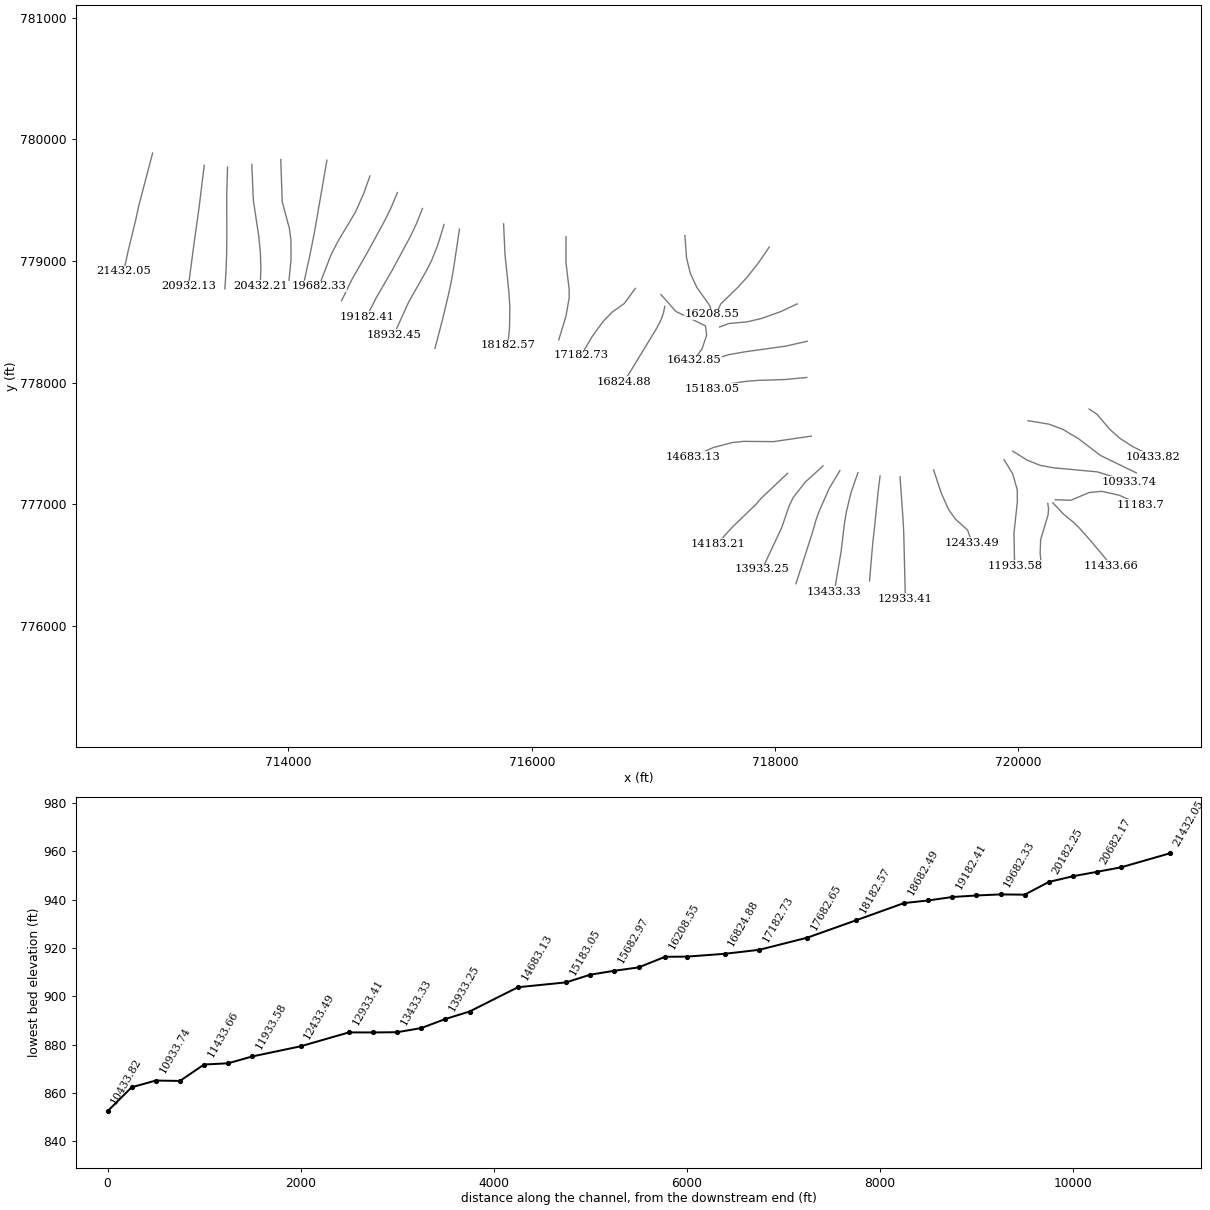
HEC-RAS study 14536_ras.prj: 14536

--- 14536_ras.g01 (geometry) --- (continued)

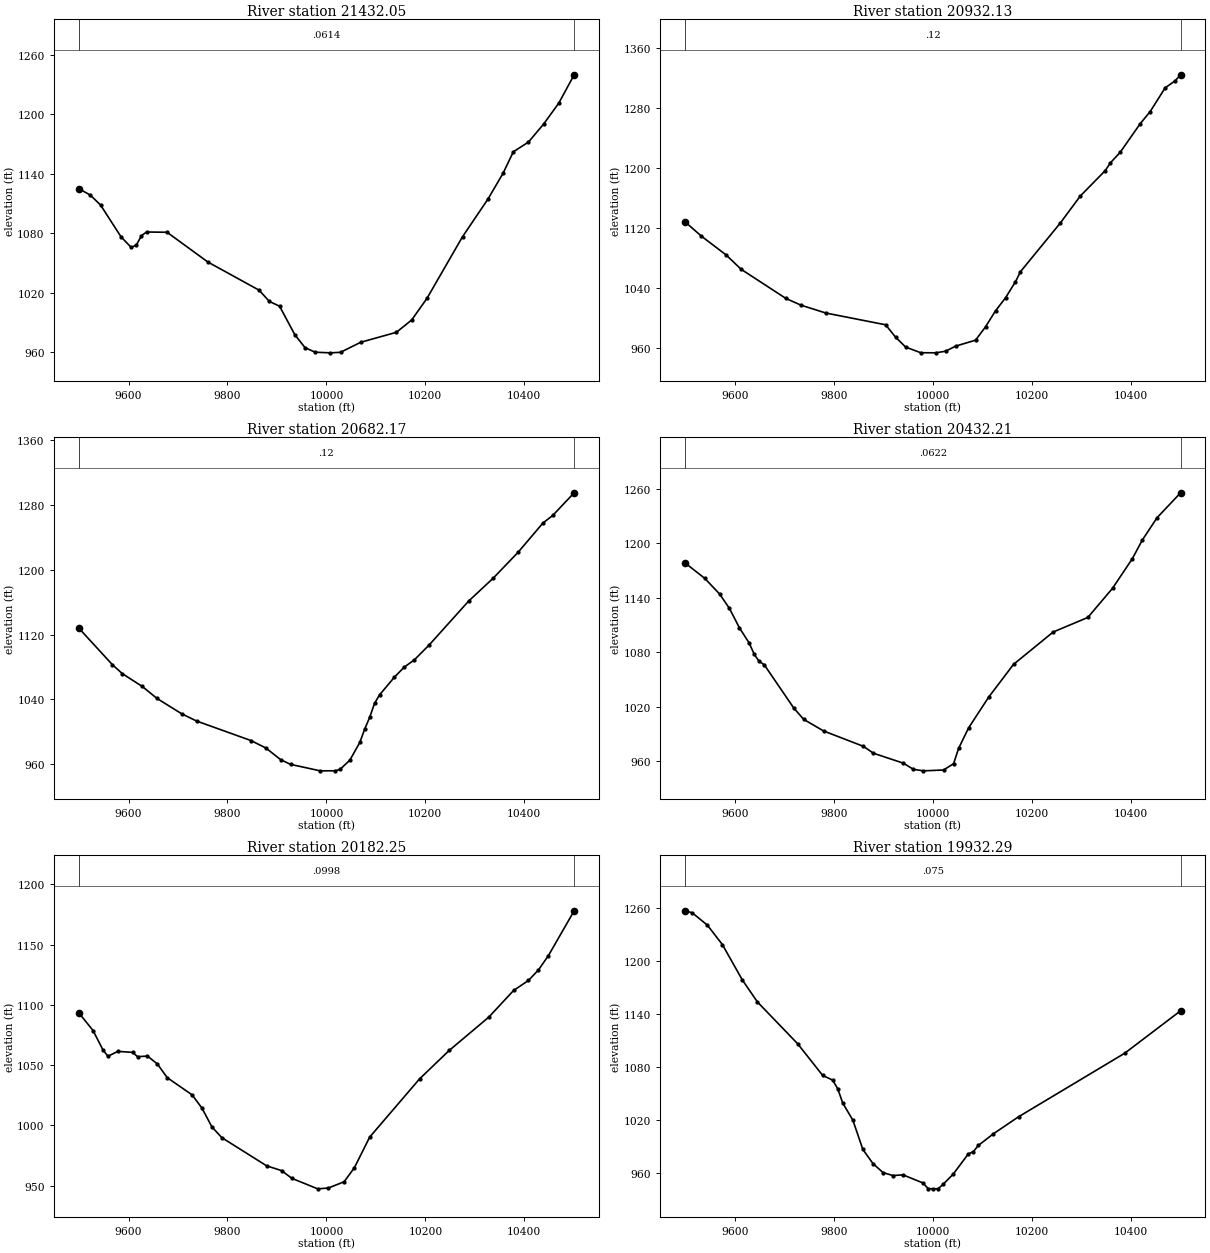
Type RM Length L Ch R = 1 ,21432.05,499.919600,499.919600,499.919600
XS GIS Cut Line= 6
712883.431684014779887.913787427  712772.6610697779467.541950844
712758.471278707779403.840810361712744.173197623779338.113793406
712682.054437702779082.613055805712645.941438362778914.673870099
#Sta/Elev= 30
9499.0161124.9449522.7121118.2669543.395 1108.29 9584.761076.1899605.4431065.469
9615.7841067.9519626.1261077.4369636.4671081.0739677.8321080.7959760.5631050.701
9863.9771022.337 9884.661011.0079905.3421006.1879936.342977.25119956.832964.3451
9977.322959.751410008.04959.126610028.51959.657610069.47969.799910141.51 979.849
10172.38992.252610203.261014.035 10275.31076.35210326.751114.36110357.451140.563
10377.911161.985 10408.61171.84210439.28 1190.0210469.971211.19610500.991239.735
#Mann= 3 , 0 , 0
9499.016  0.0614       09499.016  0.0614       010500.99  0.0614       0
#XS Ineff= 2 , 0
       0                               0
Bank Sta=9499.016,10500.99
Exp/Cntr=0.3,0.1

Type RM Length L Ch R = 1 ,20932.13,249.959800,249.959800,249.959800
XS GIS Cut Line= 6
713307.665666834779787.414014488713265.582818474779443.883253044
713244.333875742779291.459372751713244.071459308779289.476663086
713222.731754092779138.037111001713177.674651555778793.911099189
#Sta/Elev= 30
9499.0031128.296 9531.661109.3099582.0331084.0449612.258 1064.96 9702.931025.958
9733.1551017.0689783.5291006.5499904.555990.81819924.748974.12699944.942961.1295
9975.232953.565910005.52953.386110025.72955.539110045.92962.322310086.31970.2944
10106.51988.143910126.711009.523 10146.9 1026.8110167.081048.34710177.171061.746
10257.851126.81410298.191162.76310348.62 1196.7110358.711206.79910378.881221.213
10419.221259.26810439.391275.45710469.641307.09810489.821316.508   105011324.589
#Mann= 3 , 0 , 0
9499.003    0.12       09499.003    0.12       0   10501    0.12       0
#XS Ineff= 2 , 0
       0                               0
Bank Sta=9499.003,10501
Exp/Cntr=0.3,0.1

Type RM Length L Ch R = 1 ,20682.17,249.959800,249.959800,249.959800
XS GIS Cut Line= 6
713499.289573855779773.413738158713492.469429748779546.172264136
713493.310674049779192.959876895713491.613725238779051.726909689
713486.870154837778918.438937177713477.395018328778771.950421781
#Sta/Elev= 30
9499.0091128.187 9567.481082.6429587.4961071.6269627.5131055.901 9657.521041.002
9707.5311021.9899737.5361013.0869847.536988.94629877.536979.77349907.536965.3248
9927.536959.50849987.536951.509310017.54951.577310027.54953.220510047.54964.7913
10067.54986.592710077.541003.29410087.541017.70310097.541035.20110107.541045.462
10137.541067.35210157.541079.82810177.541088.55610207.551106.98310287.591161.381
10337.621189.932 10387.71221.79610437.811257.87510457.851267.39310500.991295.304
#Mann= 3 , 0 , 0
9499.009    0.12       09499.009    0.12       010500.99    0.12       0
#XS Ineff= 2 , 0
       0                               0
Bank Sta=9499.009,10500.99
Exp/Cntr=0.3,0.1

Type RM Length L Ch R = 1 ,20432.21,249.959800,249.959800,249.959800
XS GIS Cut Line= 6
713698.606490916 779794.72754595713711.125152798779499.973835637
713755.066829354779209.682530538713768.941852808779071.972160293
713773.087123311778934.508398048713768.190397083778797.478246087
#Sta/Elev= 30
 9499.041178.2289538.771 1161.299568.7741144.1099588.7761128.1449608.7781107.003
 9628.781089.9719638.7841077.8399648.799 1069.959658.8141066.4819718.902 1018.62
9738.9581006.2239779.102993.50779859.659976.59019879.814969.03639940.431958.0832
9960.739951.29869981.046949.675310021.64 950.59710041.91957.556110052.05974.3758
10072.33996.965910112.711030.58810163.041066.69610243.281102.30610313.341118.298
10363.341150.39610403.351182.93910423.361203.27810453.381228.02210500.971255.361
#Mann= 3 , 0 , 0
 9499.04  0.0622       0 9499.04  0.0622       010500.97  0.0622       0
#XS Ineff= 2 , 0
       0                               0
Bank Sta=9499.04,10500.97
Exp/Cntr=0.3,0.1

Type RM Length L Ch R = 1 ,20182.25,249.959800,249.959800,249.959800
XS GIS Cut Line= 6
 713936.63155167779834.150576434713948.643202073779486.808093045
714007.390776801779269.494843112714020.431589507779172.962132848
714020.811050284779012.453798104714004.591650036778843.167788841
#Sta/Elev= 30
9499.0551093.5969528.2111078.7049548.215 1062.639558.2171057.346 9578.221061.398
9608.2211060.5889618.2221057.0029638.2231057.5169658.2241050.9799678.2261039.567
9728.2841025.3759748.3071014.4049768.371998.80689788.461989.81899879.119966.4303
9909.567962.39989930.086956.03369982.346947.311410003.89947.980510035.93 953.228
10056.68964.958310087.48990.239110188.211038.52410248.251062.17710328.281089.819
 10378.41111.94410408.511120.26810428.641128.96610448.761140.83910500.92 1178.11
#Mann= 3 , 0 , 0
9499.055  0.0998       09499.055  0.0998       010500.92  0.0998       0
#XS Ineff= 2 , 0
       0                               0
Bank Sta=9499.055,10500.92
Exp/Cntr=0.3,0.1

Type RM Length L Ch R = 1 ,19932.29,249.959900,249.959900,249.959900
XS GIS Cut Line= 6
714316.120938419  779829.1971785714230.765721354779336.540360022
714230.355700368779334.582840471714210.483875821779220.782098994
714174.221058573779040.273829944714131.441372692 778844.53958768
#Sta/Elev= 30
9499.0041257.0059513.4121254.7099543.859 1240.849574.3061218.8029614.9021178.504
9645.349 1153.669726.5411106.4099777.2861070.4549797.5841065.1519807.7331055.211
9817.8821039.097 9838.181019.8729858.478 986.6219878.776 970.7439899.074960.4975
9919.371957.07259939.669957.88719980.265948.62129990.414 942.29210000.57942.0439
10010.73942.184610020.88947.284610041.18 958.71710071.64981.607510081.79984.1569
10091.94991.182410122.421004.41410173.421023.71910387.921095.66310500.991143.739
#Mann= 3 , 0 , 0
9499.004   0.075       09499.004   0.075       010500.99   0.075       0
#XS Ineff= 2 , 0
       0                               0
Bank Sta=9499.004,10500.99
Exp/Cntr=0.3,0.1

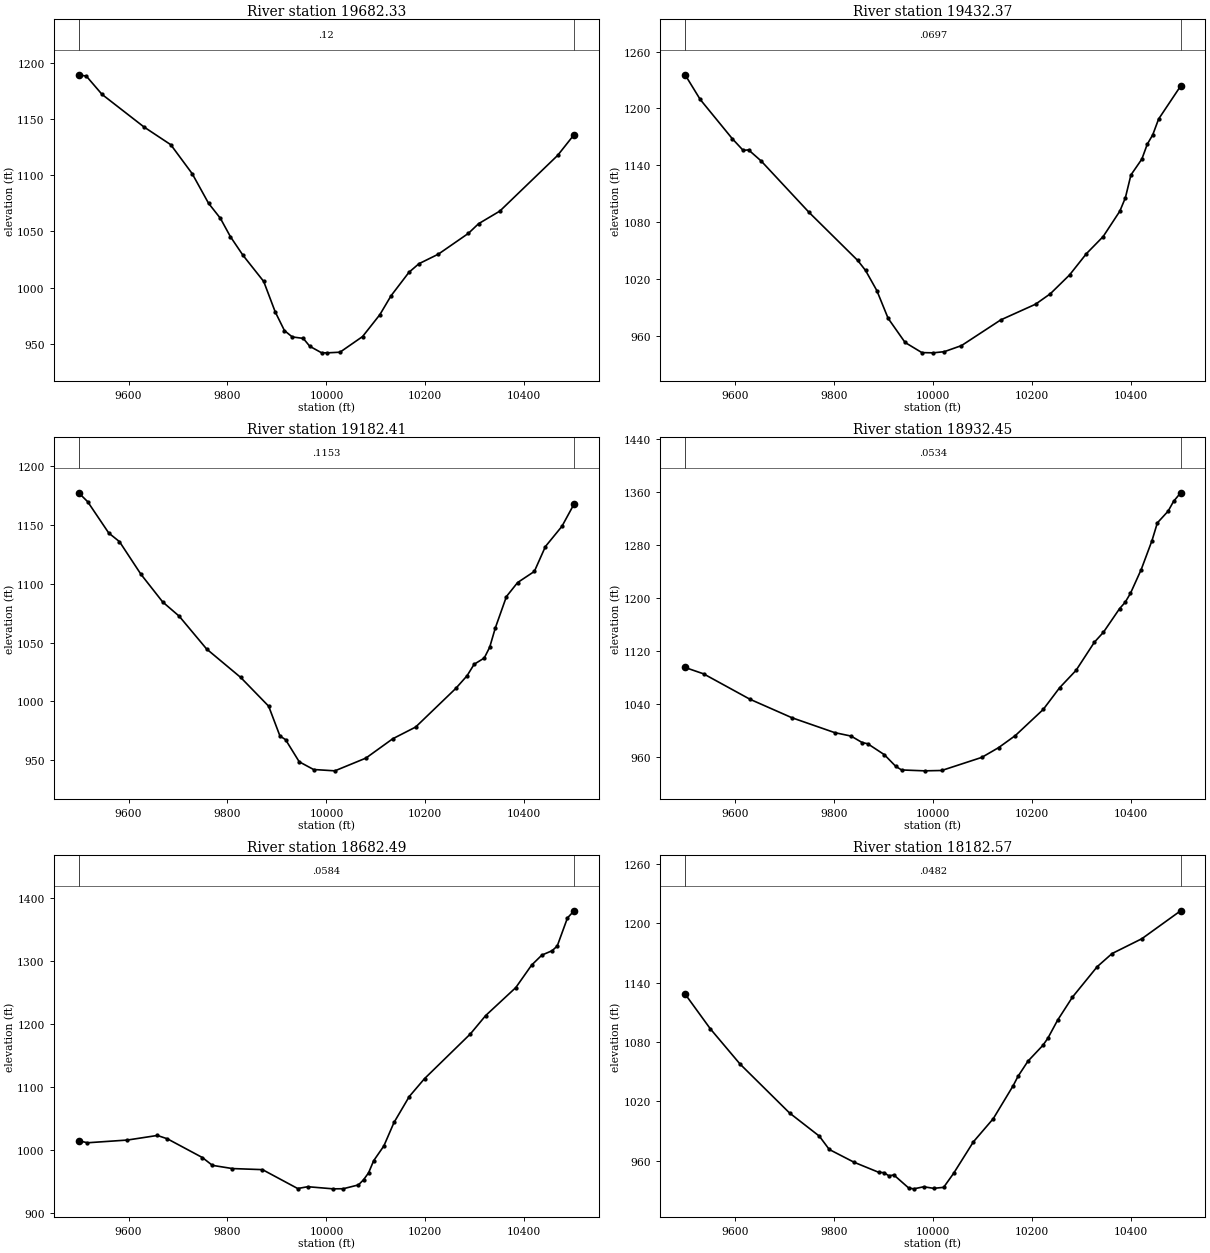
Type RM Length L Ch R = 1 ,19682.33,249.959800,249.959800,249.959800
XS GIS Cut Line= 6
714669.999206539779699.756900406714619.136175418779557.774731788
714551.449089482779404.249454978714403.728414958779156.729514992
 714349.16864296779049.658988848714250.237519489 778793.55103241
#Sta/Elev= 30
9499.0481189.1899514.643 1187.999546.3471171.7749631.4811142.7279685.3831127.046
9728.7081101.2949761.6891075.0529785.6941061.6529805.839 1045.429831.2441028.876
 9873.231005.5869896.465978.59589915.216961.88919930.992956.29239953.209954.9858
9966.486 947.9519990.149942.221610002.01942.152510027.49942.721110073.14956.6223
10108.07976.056310130.76992.891210166.951013.711 10187.11021.32510226.311029.805
10287.051048.279 10307.61056.84710350.621068.07410467.58 1117.5810500.971136.078
#Mann= 3 , 0 , 0
9499.048    0.12       09499.048    0.12       010500.97    0.12       0
#XS Ineff= 2 , 0
       0                               0
Bank Sta=9499.048,10500.97
Exp/Cntr=0.3,0.1

Type RM Length L Ch R = 1 ,19432.37,249.959800,249.959800,249.959800
XS GIS Cut Line= 6
714895.540388159779563.342286962714842.416050234779436.887577193
714791.830644273779333.614811447714648.947939166779071.167525712
714524.142486376778853.566124021714436.150171889778673.910938813
#Sta/Elev= 30
9499.0281235.457 9529.541209.4149594.6071167.8399616.4371155.5939627.3521156.114
9653.0661144.2719749.6611090.096 9848.111039.2839863.8441028.7829886.6881007.509
9909.533978.1693  9943.8 952.6759977.776941.960710000.38 941.70710023.03  942.93
10057.87 949.35710137.28976.506110207.64993.093610237.57 1004.1410276.351023.982
10310.531046.51810344.251064.50710377.981091.34210389.221105.47410400.46 1129.63
10422.531146.35710433.571162.159 10444.61172.06210456.411188.68710500.981223.573
#Mann= 3 , 0 , 0
9499.028  0.0697       09499.028  0.0697       010500.98  0.0697       0
#XS Ineff= 2 , 0
       0                               0
Bank Sta=9499.028,10500.98
Exp/Cntr=0.3,0.1

Type RM Length L Ch R = 1 ,19182.41,249.959800,249.959800,249.959800
XS GIS Cut Line= 6
715101.580848895779431.999036303715050.721162851779304.697170962
715001.210279675779200.884598787714854.874847044778928.555722221
 714721.24659374778697.972925761 714642.44327556778542.708244991
#Sta/Elev= 30
9499.0361177.2119517.2011169.6949559.9461143.0269581.6231135.7169624.9761108.021
9669.0441084.4649702.282 1072.459757.8651044.5269826.5931020.4429883.256995.9804
9906.054970.68649917.453967.55029945.062948.76459974.074942.2154 10017.1941.0792
10079.82 951.88910134.04968.289610180.44978.267610261.461011.00510284.391021.817
10298.731031.58310319.171036.883 10330.21046.08310341.481062.35310364.05 1089.11
10386.611100.97810420.461110.41610442.85 1131.57 10476.21148.70810500.981167.828
#Mann= 3 , 0 , 0
9499.036  0.1153       09499.036  0.1153       010500.98  0.1153       0
#XS Ineff= 2 , 0
       0                               0
Bank Sta=9499.036,10500.98
Exp/Cntr=0.3,0.1

Type RM Length L Ch R = 1 ,18932.45,249.959800,249.959800,249.959800
XS GIS Cut Line= 6
715278.783644053779300.824251375715229.535735299779138.044531708
715176.591140233779004.533475927715135.790586141778923.600548187
714988.331444367 778663.84355855714865.099422264778391.765540758
#Sta/Elev= 30
9499.0631095.5269536.326 1085.979630.2811047.5869715.0961019.7199801.435997.3062
9834.698992.04939857.096 982.2929868.295980.49289901.892964.01059925.082946.3537
9936.706940.98949983.206939.6433 10017.9940.176710098.91959.930910132.91974.6442
 10166.8992.870210223.081032.18110256.291065.006 10289.51091.18710326.611133.674
10344.841148.64410377.691184.48710388.581193.63310399.461207.29610421.231243.241
10443.011286.82810453.891313.63510475.671331.32610486.551345.93510500.961359.024
#Mann= 3 , 0 , 0
9499.063  0.0534       09499.063  0.0534       010500.96  0.0534       0
#XS Ineff= 2 , 0
       0                               0
Bank Sta=9499.063,10500.96
Exp/Cntr=0.3,0.1

Type RM Length L Ch R = 1 ,18682.49,499.919600,499.919600,499.919600
XS GIS Cut Line= 6
715405.581301481779262.486904488715356.611034321778935.422655736
715337.233096535778827.199892298715316.846859434778731.172523876
715267.956661085778526.331433832715204.216746892778281.949429635
#Sta/Elev= 30
9499.0111014.9879516.6931011.6589597.5851015.9839658.2541023.2789678.4771017.938
9749.257988.2113 9769.48975.83639809.926970.74149870.787 969.0239941.912939.0736
9962.341941.941910013.44938.565410033.92938.712510064.74944.786410075.02952.8458
 10085.3963.960610095.58983.208110116.151006.57210136.711043.87710167.551085.037
10198.391113.40110291.061184.325   103221213.46510382.991257.92710414.941293.592
10435.671309.45210456.39  1316.410466.751323.85410487.471368.515   105011379.771
#Mann= 3 , 0 , 0
9499.011  0.0584       09499.011  0.0584       0   10501  0.0584       0
#XS Ineff= 2 , 0
       0                               0
Bank Sta=9499.011,10501
Exp/Cntr=0.3,0.1

Type RM Length L Ch R = 1 ,18182.57,499.919600,499.919600,499.919600
XS GIS Cut Line= 6
715768.366215927779306.022440191715779.885752276 779054.14271522
715812.296120558778740.761263709715819.672644094778620.054978116
  715817.0936107778446.765991491715802.532862777778307.150804123
#Sta/Elev= 30
9499.0171128.4359550.0641093.2449610.0931057.6379710.2531008.1049770.413984.6996
9790.494971.22239840.696958.27839890.917948.01989900.983947.80599911.049944.5507
9921.114945.42719951.311932.14429961.377931.38569981.508933.457110001.64931.8904
10021.76932.888410041.88947.036510082.06979.017310122.131002.37910162.211035.607
10172.221045.27410192.251060.53810222.251076.44610232.251083.53610252.251102.048
10282.261125.348 10332.31156.13110362.33 1169.4110422.54  1184.410500.961212.672
#Mann= 3 , 0 , 0
9499.017  0.0482       09499.017  0.0482       010500.96  0.0482       0
#XS Ineff= 2 , 0
       0                               0
Bank Sta=9499.017,10500.96
Exp/Cntr=0.3,0.1

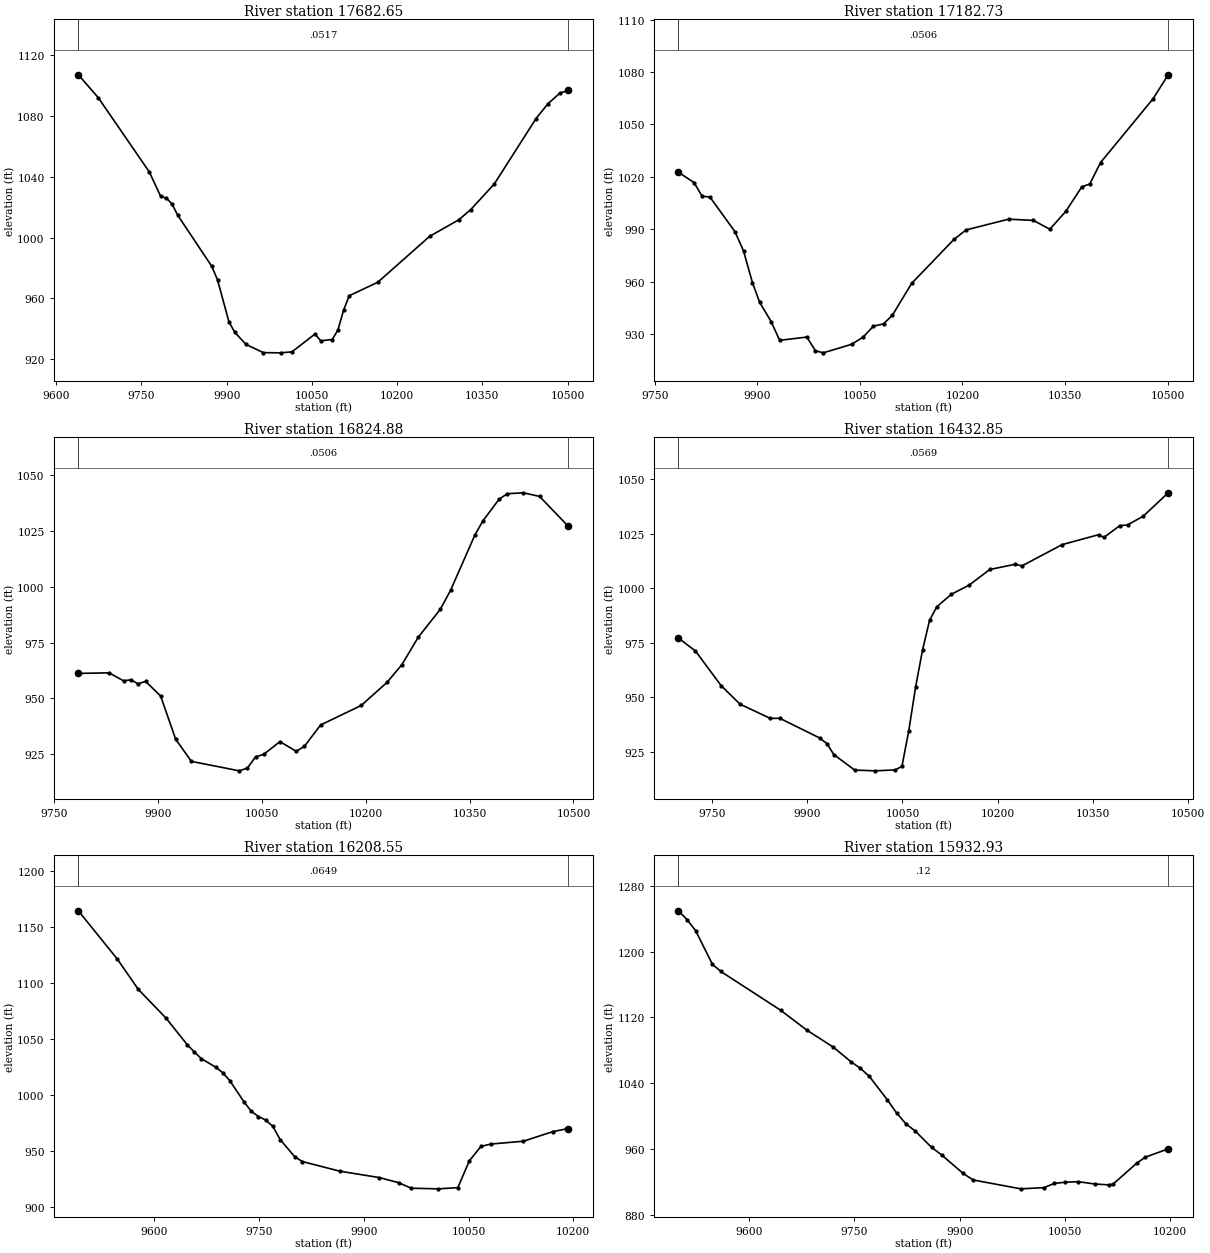
Type RM Length L Ch R = 1 ,17682.65,499.919600,499.919600,499.919600
XS GIS Cut Line= 6
716281.510513479779199.883669341716280.790183262778989.620849235
716307.321098618778767.915870201716307.706014154778699.872652635
716280.865740081778545.612581746716221.437403848778351.239421622
#Sta/Elev= 30
9639.0381106.8769673.9281091.9179763.9411043.0739783.9421027.0519793.9431025.911
9803.9431021.9719813.9441014.6299874.008980.97079884.034972.09889904.085944.6107
9914.111937.83829934.203929.76939964.503924.41039994.803924.265610015.01 924.925
10055.47936.628510065.59932.133410085.69933.0231 10095.7939.098710105.71952.1967
10115.71961.7661 10165.9 970.60810257.321000.79810308.621011.656 10329.41018.296
10370.961035.14910444.351078.06510465.381087.85410486.411094.83210500.881096.563
#Mann= 3 , 0 , 0
9639.038  0.0517       09639.038  0.0517       010500.88  0.0517       0
#XS Ineff= 2 , 0
       0                               0
Bank Sta=9639.038,10500.88
Exp/Cntr=0.3,0.1

Type RM Length L Ch R = 1 ,17182.73,357.852500,357.852500,357.852500
XS GIS Cut Line= 6
716851.170276806778775.338837936716760.158254058 778650.65256711
716662.732051379778582.404311866716587.469670468778505.239783336
716495.438447839778378.316302307716406.116970637778225.597159045
#Sta/Elev= 30
 9784.61 1022.569807.5111016.6679819.1041008.9069830.6971008.3729867.479988.4583
9879.808 977.5159892.895959.34499903.285948.20429920.196937.05989932.668926.3736
9972.324928.24499984.883920.43369996.385919.213910038.18924.136710054.85928.2791
 10069.8 934.48410084.53935.7971 10097.3 940.64110125.75  959.0110187.42984.0981
10205.31989.578810267.48 995.72310303.75995.022310327.79989.949410351.181000.231
10374.561014.24710386.251015.88610401.961028.16210478.661064.59910500.871078.377
#Mann= 3 , 0 , 0
 9784.61  0.0506       0 9784.61  0.0506       010500.87  0.0506       0
#XS Ineff= 2 , 0
       0                               0
Bank Sta=9784.61,10500.87
Exp/Cntr=0.3,0.1

Type RM Length L Ch R = 1 ,16824.88,392.026900,392.026900,392.026900
XS GIS Cut Line= 6
717093.363604462778628.665761255717083.639401097778578.283623606
717072.004461434778541.834608496717052.157371542 778495.57342585
717022.656673445  778440.5374853716759.574800938778009.711858381
#Sta/Elev= 30
9785.006961.24669829.481961.50119850.316957.92039860.813958.3892 9871.31956.5852
 9882.07 957.6839903.833951.09869925.623931.68389948.315921.8087 10017.4917.5634
10029.14918.815410040.88923.825610052.63924.947310076.11930.6646 10099.6926.3247
10111.34928.513210134.83938.114710193.55946.894810230.93957.278910252.26   965.2
10275.75977.429910307.63989.963410322.49998.491310357.541023.23910369.221029.654
10392.591039.34310404.35 1041.8110427.631042.236   104511040.60410492.221027.294
#Mann= 3 , 0 , 0
9785.006  0.0506       09785.006  0.0506       010492.22  0.0506       0
#XS Ineff= 2 , 0
       0                               0
Bank Sta=9785.006,10492.22
Exp/Cntr=0.3,0.1

Type RM Length L Ch R = 1 ,16432.85,224.301100,224.301100,224.301100
XS GIS Cut Line= 6
717061.640369982778724.982641041717184.833832443778585.954498529
717427.465433151778467.454192311717437.341866344778389.840158299
717399.647374332778278.264461949717330.289509028778183.274342045
#Sta/Elev= 30
9697.272977.20629724.119971.25949764.423955.43749794.281946.92969841.966940.4087
9856.848940.45949919.395931.4778 9930.99928.87879941.973923.8606 9974.71 916.753
10006.57916.396610038.53916.811710049.19 918.43810059.84934.534910070.65954.6456
10081.67971.7856 10092.7985.319610104.05991.519310127.08997.265510154.851001.401
10187.561008.60410227.891011.013 10238.21010.24810301.531019.99610358.741024.517
10367.281023.27510392.05 1028.6410404.431029.01510429.191032.99210468.481043.732
#Mann= 3 , 0 , 0
9697.272  0.0569       09697.272  0.0569       010468.48  0.0569       0
#XS Ineff= 2 , 0
       0                               0
Bank Sta=9697.272,10468.48
Exp/Cntr=0.3,0.1

Type RM Length L Ch R = 1 ,16208.55,275.618500,275.618500,275.618500
XS GIS Cut Line= 6
717258.485525386779210.632329708717272.318981541779025.935576697
717302.937484271778899.789905672717357.783603296778782.119512687
717464.035198593778632.417082809717484.344185012778563.705141169
#Sta/Elev= 30
9491.4141164.6979547.0841121.6789577.1041094.6219617.3291068.554 9647.511044.938
9657.5711038.5649667.6311032.542 9687.911025.0899698.1141020.0919708.3181012.933
9728.727993.86249738.931985.71829749.136980.94079759.533977.83869769.961972.0501
 9780.39960.30559801.247944.99289812.209 940.6889865.733932.10839922.091926.4184
9949.812921.88289967.987916.898410006.57916.336410034.73917.378610051.25941.4202
10067.77954.205810081.85956.332310128.56958.861610170.96 967.49210192.58970.1899
#Mann= 3 , 0 , 0
9491.414  0.0649       09491.414  0.0649       010192.58  0.0649       0
#XS Ineff= 2 , 0
       0                               0
Bank Sta=9491.414,10192.58
Exp/Cntr=0.3,0.1

Type RM Length L Ch R = 1 ,15932.93,249.959800,249.959800,249.959800
XS GIS Cut Line= 6
717951.979434154779115.444393484717863.402208184778985.478462503
 717775.16978442778873.324466904717694.095748134778784.474625337
717552.903109438778647.033738853717519.826861029778573.912577868
#Sta/Elev= 30
9499.0281249.4939511.5311238.4519523.502 1225.419547.4431184.5679559.4141175.839
9644.6541128.8039682.0971104.5699719.8411083.9559745.1811066.0939758.1081058.508
9771.0351048.6049796.8881020.0249810.1161004.0099823.405990.82049836.694982.0531
9859.909962.28689874.443953.02439904.853930.71829919.358922.67029987.253911.9236
10020.29913.394910035.01 918.56710049.73919.9044 10069.2 920.61410093.18917.7174
10113.31916.7339   10119917.838410152.19942.839310164.68950.320710197.37960.4333
#Mann= 3 , 0 , 0
9499.028    0.12       09499.028    0.12       010197.37    0.12       0
#XS Ineff= 2 , 0
       0                               0
Bank Sta=9499.028,10197.37
Exp/Cntr=0.3,0.1

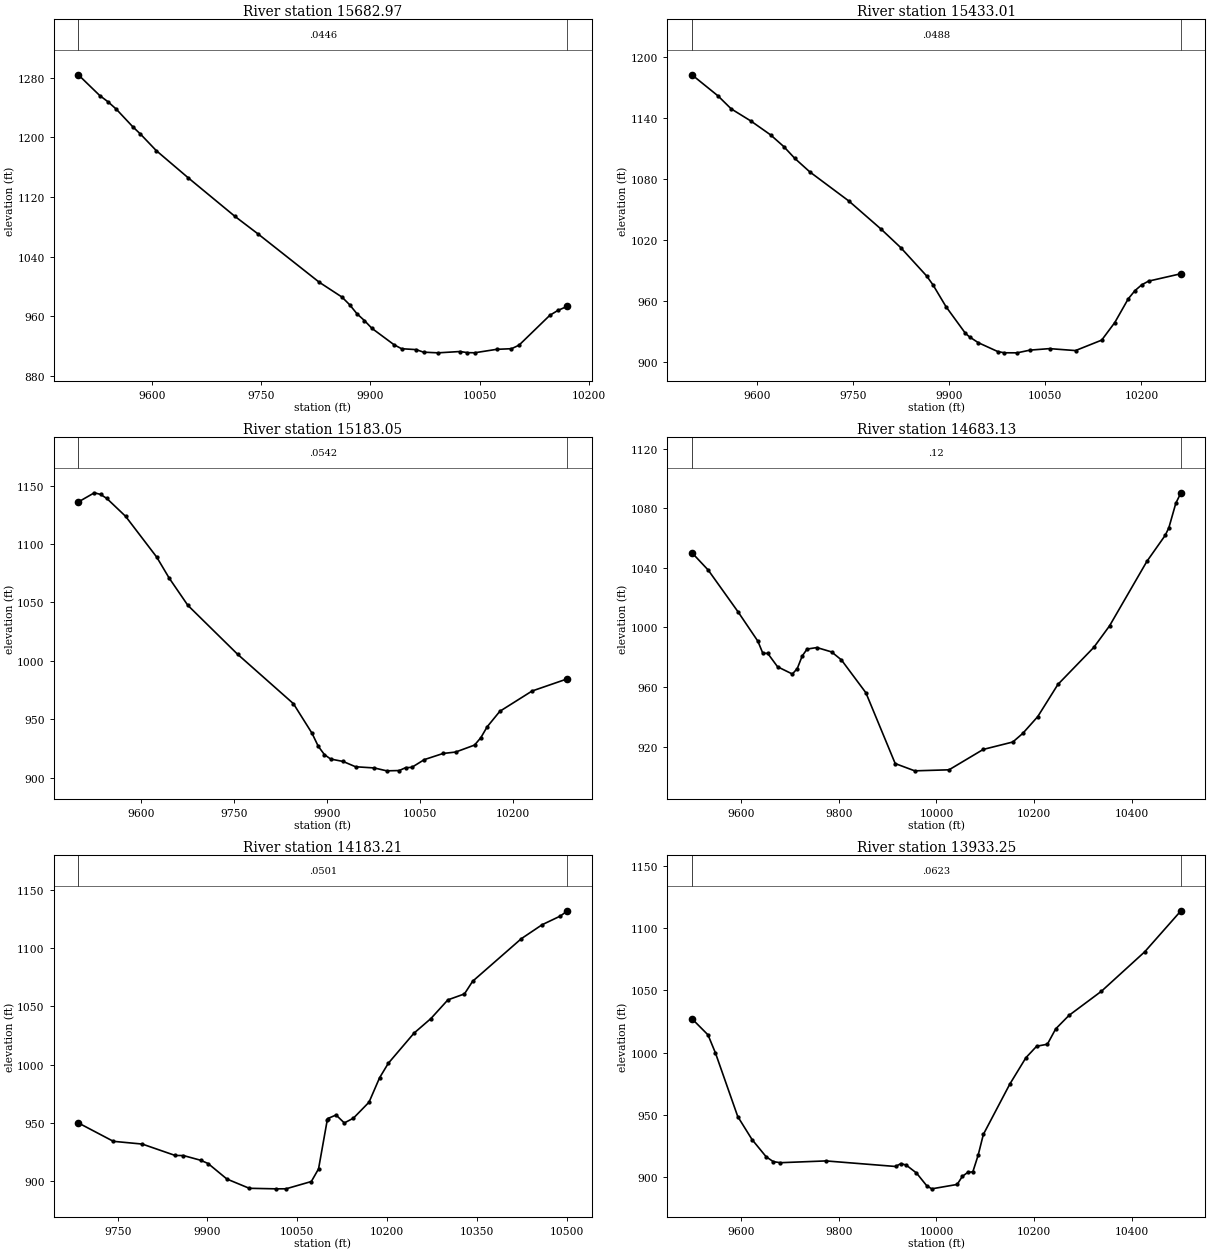
Type RM Length L Ch R = 1 ,15682.97,249.959800,249.959800,249.959800
XS GIS Cut Line= 6
718181.395299552778647.990429319 718044.55822783778583.884191877
717884.585054194778527.110656572717767.093384249778499.945860267
717620.642556587778486.889674771717543.755116464778458.241575086
#Sta/Elev= 30
9499.0691284.2779528.4981256.3629539.6471248.1259551.0591238.2129573.6731214.589
9584.2341204.7239606.0671182.3629649.7341145.9519714.0921093.9579745.9281070.256
9829.9431005.3399860.984985.50499871.331 975.3869881.672962.98779891.863953.8961
9902.053943.51769932.624921.32739942.787916.09329962.906914.86749972.965911.4269
9993.007910.543910023.04912.325110033.05 910.83410043.07 910.62110073.35915.2556
10093.67 916.10710104.01 920.82510146.24960.932610157.26967.489110170.39973.1305
#Mann= 3 , 0 , 0
9499.069  0.0446       09499.069  0.0446       010170.39  0.0446       0
#XS Ineff= 2 , 0
       0                               0
Bank Sta=9499.069,10170.39
Exp/Cntr=0.3,0.1

Type RM Length L Ch R = 1 ,15433.01,249.959900,249.959900,249.959900
XS GIS Cut Line= 6
718264.388867877778341.206381539718090.409613788778301.317005321
717751.408938836 778253.90850451717618.534780566778230.393264493
717569.882661681778215.383514903717519.650235099778190.877795399
#Sta/Elev= 30
9499.0251182.6879539.6991161.9389560.3511149.1139591.1231137.1289621.7781123.492
9642.2161112.0629659.6581100.2869683.0421087.0029743.8271058.3989794.4811030.499
9824.7381012.5149865.066984.66039875.148 975.7169895.312954.37359925.559928.1795
 9932.05924.59399945.723918.90499975.969910.21199986.051908.983210006.21908.9231
10026.39911.603110056.74913.074810097.29  911.1610138.09921.434810158.58938.7901
10179.51962.087110189.97970.142110200.44975.839510211.16979.520610261.75986.8164
#Mann= 3 , 0 , 0
9499.025  0.0488       09499.025  0.0488       010261.75  0.0488       0
#XS Ineff= 2 , 0
       0                               0
Bank Sta=9499.025,10261.75
Exp/Cntr=0.3,0.1

Type RM Length L Ch R = 1 ,15183.05,499.919600,499.919600,499.919600
XS GIS Cut Line= 6
718260.700290006778043.359275659718077.599012689778026.078097372
 717856.86638279778019.174376739717762.046459534 778011.46999372
717592.764512266777985.672785562717481.951256045777949.357836238
#Sta/Elev= 30
9499.0271136.0279524.9031143.9169534.9711142.4939545.0391139.0269575.2431123.749
9625.4071088.7899645.4661070.8329675.5551047.4999755.6491005.6379845.678963.2626
9875.686937.88419885.689926.77089895.692 919.5989905.698915.8414 9925.73913.7806
9945.761 909.2399975.895908.21879996.027905.744910016.21906.0028 10026.3908.4316
10036.39908.719910056.57915.355910086.85920.625810107.04921.835210137.52927.8086
10147.68934.178410157.84943.456210178.27956.738810230.24974.1267 10287.1984.5508
#Mann= 3 , 0 , 0
9499.027  0.0542       09499.027  0.0542       0 10287.1  0.0542       0
#XS Ineff= 2 , 0
       0                               0
Bank Sta=9499.027,10287.1
Exp/Cntr=0.3,0.1

Type RM Length L Ch R = 1 ,14683.13,499.919600,499.919600,499.919600
XS GIS Cut Line= 6
718297.714271173777561.277088697717987.558577382777515.851240124
 717740.50520712777517.977702318717648.869071215777508.499066311
717490.700352189777466.797219851717322.866186114777390.205618776
#Sta/Elev= 30
9499.0361050.2039532.5191038.5119593.6331010.4619634.217990.76689644.311982.6886
9654.393982.59779674.557973.59169704.803 968.7389714.885972.38369724.967 980.802
9735.017985.48479755.105986.50169785.237983.56479805.325978.20939855.443956.1612
9915.505908.61289955.526903.7195 10025.8904.409610095.89918.100710156.43 923.076
10176.83 928.85510207.49940.119110248.85961.754410322.35986.621110354.531001.027
 10431.11044.37710468.47 1061.7610476.04 1066.86 10490.41083.44610500.91 1090.43
#Mann= 3 , 0 , 0
9499.036    0.12       09499.036    0.12       010500.91    0.12       0
#XS Ineff= 2 , 0
       0                               0
Bank Sta=9499.036,10500.91
Exp/Cntr=0.3,0.1

Type RM Length L Ch R = 1 ,14183.21,249.959800,249.959800,249.959800
XS GIS Cut Line= 6
718102.798913211777255.111756384717885.145172062777050.014885578
717844.659223272777001.858039382717652.907445183776816.993134612
717588.643666916776747.829761551717527.487939526776676.711141024
#Sta/Elev= 30
9684.326950.14069742.838934.36599791.188932.0142 9846.13922.24849859.865922.1811
9888.708918.13759901.072915.3463 9932.47902.07089969.796 894.145 10014.9893.6771
 10031.2 893.71310073.43899.942510085.47 910.75510100.03 952.67110100.95953.8821
10114.72956.919410128.48950.0984 10143.7954.195910169.76967.867410187.37 988.766
10201.931001.17410244.871026.99810273.151039.52610301.431055.48910329.131060.603
10342.781071.42710424.091107.89510458.771119.83110489.441127.33510500.961131.785
#Mann= 3 , 0 , 0
9684.326  0.0501       09684.326  0.0501       010500.96  0.0501       0
#XS Ineff= 2 , 0
       0                               0
Bank Sta=9684.326,10500.96
Exp/Cntr=0.3,0.1

Type RM Length L Ch R = 1 ,13933.25,249.959800,249.959800,249.959800
XS GIS Cut Line= 6
718394.579343997777316.657515865718246.766003358777181.904779647
718148.649043863777056.029298817718113.914696467776983.421893073
718052.960731987776804.958180172717893.825771431776468.201436642
#Sta/Elev= 30
9499.0951027.2789532.0991014.2649547.338999.74019593.055948.62259622.341930.1592
 9651.28916.3132 9665.75912.4568 9680.22911.57649773.727913.0116 9916.23908.5457
9927.096910.85789937.962909.69159959.136  903.329980.131893.08139990.478890.5777
10042.48 894.10710053.14900.597510063.89903.717310074.65904.298110085.41917.5109
10096.16  934.32 10150.4974.766310183.35995.939310205.321005.15210227.291006.747
10244.311019.06510271.511029.90910338.081049.34110426.841081.05810500.951113.973
#Mann= 3 , 0 , 0
9499.095  0.0623       09499.095  0.0623       010500.95  0.0623       0
#XS Ineff= 2 , 0
       0                               0
Bank Sta=9499.095,10500.95
Exp/Cntr=0.3,0.1

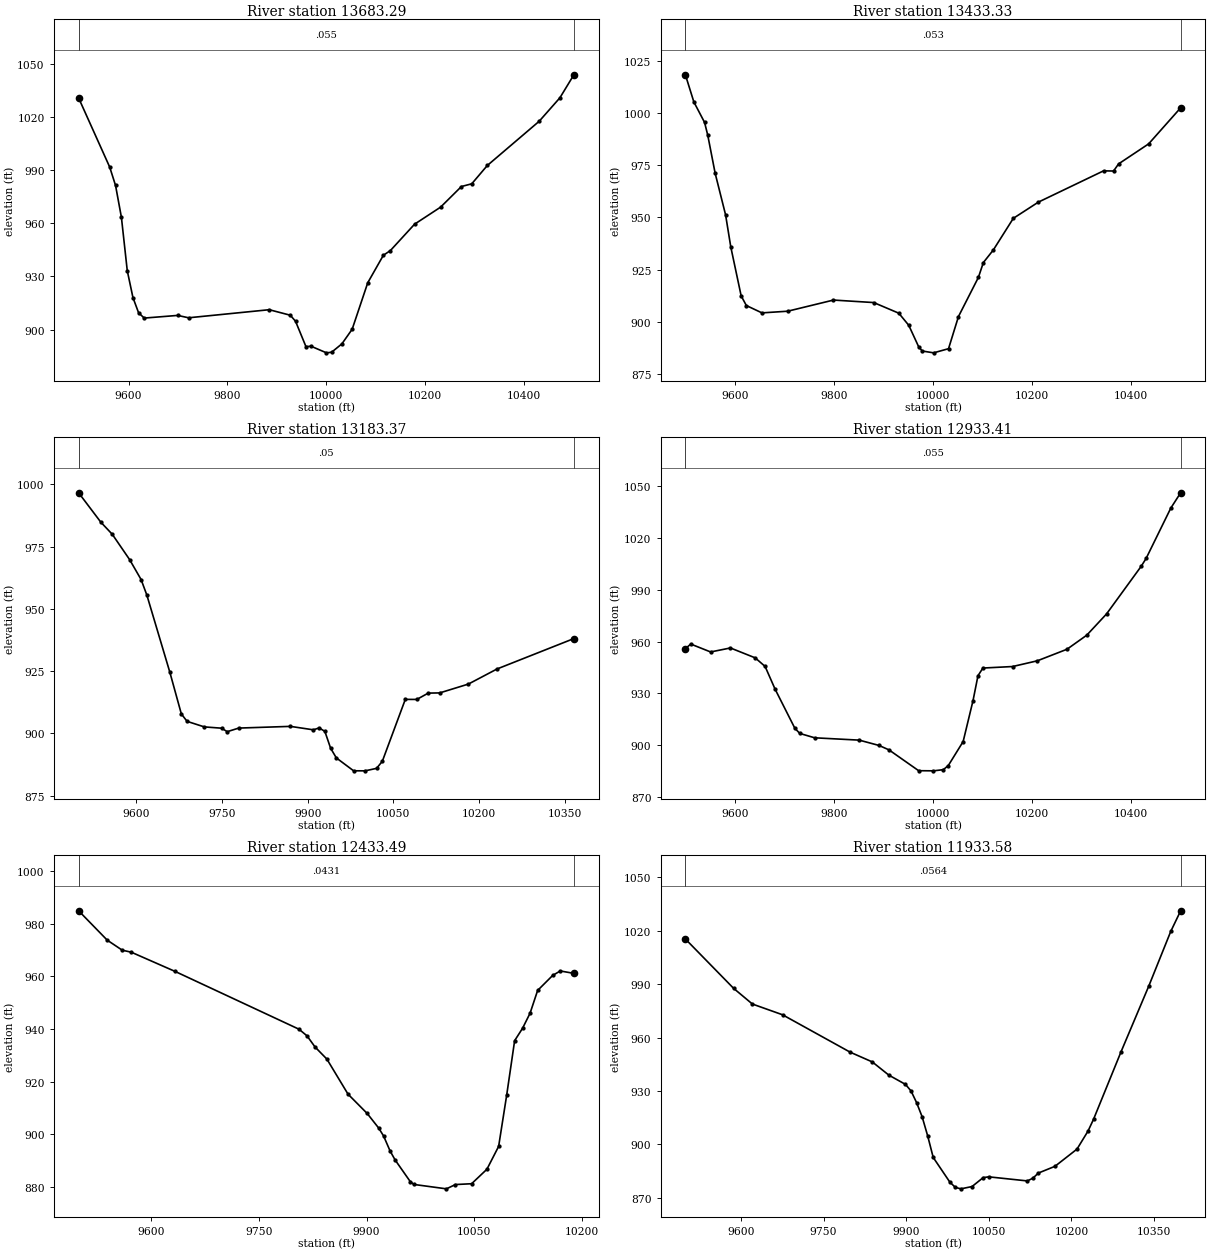
Type RM Length L Ch R = 1 ,13683.29,249.959800,249.959800,249.959800
XS GIS Cut Line= 6
718532.998977518 777278.09479031718445.535149089777132.321262648
718363.361266992776947.125618452718336.825039038776873.626691942
718308.542935448776773.392656241 718171.50915718776348.063427241
#Sta/Elev= 30
9499.0731030.8559561.953991.79259573.797981.3949 9585.64963.40999597.483933.2455
9608.989918.03259620.409909.44379631.829906.46369699.401907.96689721.547906.6293
9884.723911.1921 9927.25908.07939937.882904.67579958.941890.34729969.335890.5419
10000.51886.818910010.89887.161510031.67891.896910052.45900.150110084.01926.4345
10115.58941.964510129.63944.571810178.73959.524510231.35969.158110273.44 980.803
10294.41982.352310325.88992.694910430.781017.67710472.731030.95510500.991043.954
#Mann= 3 , 0 , 0
9499.073   0.055       09499.073   0.055       010500.99   0.055       0
#XS Ineff= 2 , 0
       0                               0
Bank Sta=9499.073,10500.99
Exp/Cntr=0.3,0.1

Type RM Length L Ch R = 1 ,13433.33,249.959800,249.959800,249.959800
XS GIS Cut Line= 6
718681.089988544777261.272941317718624.207332819777095.897731842
718586.727113473776942.203938435718569.817759546776841.137598661
 718542.93846469776614.113504848718486.784743038776281.169144559
#Sta/Elev= 30
9499.054 1018.359516.1851005.3349537.863995.52219544.314989.39099559.261971.1694
9580.399951.20969590.904935.84459611.913912.38369622.417907.7737 9653.93904.2561
9705.964905.05339798.637910.39899880.088909.19979930.783904.10769950.936898.3079
9971.059887.97299978.272885.978810001.23885.1076 10031.4 887.09610051.51902.5041
10091.81921.2553 10101.9928.383510122.08  934.4210162.44949.554310213.15957.3282
10344.98972.310710365.27972.232910375.41975.646210436.25985.241910500.99 1002.51
#Mann= 3 , 0 , 0
9499.054   0.053       09499.054   0.053       010500.99   0.053       0
#XS Ineff= 2 , 0
       0                               0
Bank Sta=9499.054,10500.99
Exp/Cntr=0.3,0.1

Type RM Length L Ch R = 1 ,13183.37,249.959800,249.959800,249.959800
XS GIS Cut Line= 6
718862.906886934777233.577692112718846.099940262777097.505899117
718817.889399492776815.000002936718808.915200183776734.526129148
718800.616677996776657.819141904718776.334636819776370.954024971
#Sta/Elev= 30
 9499.01996.56659537.881984.77379558.033979.88619588.261969.76659608.413961.7413
9618.489955.50299658.734924.55299678.833 907.8499688.883904.86479719.032902.6399
9749.182 902.1239759.231900.72749779.331902.16679869.778902.84819909.977901.4666
9920.027902.22939930.089900.8521 9940.15894.09319950.212890.19279980.397885.0269
10000.52885.010710020.64886.0075 10030.7888.847710070.93913.680610091.02913.6563
10111.09 916.19610131.16916.276410181.34919.818210231.52925.878310366.05938.0788
#Mann= 3 , 0 , 0
 9499.01    0.05       0 9499.01    0.05       010366.05    0.05       0
#XS Ineff= 2 , 0
       0                               0
Bank Sta=9499.01,10366.05
Exp/Cntr=0.3,0.1

Type RM Length L Ch R = 1 ,12933.41,499.919600,499.919600,499.919600
XS GIS Cut Line= 6
719027.317098768777225.891469262719050.386609161776895.993628519
719057.200384586776775.936995711719058.583084197776726.922702581
719058.596535456776724.922747816719070.893291697776225.080967452
#Sta/Elev= 30
9499.013955.91059509.931958.54739550.029 953.9689590.126956.28679640.248950.5502
9660.297945.57359680.346932.48019720.444909.72839730.468906.71699760.541904.1849
9850.744902.83149890.808899.7471 9910.84897.19539970.912885.108610000.92885.0251
10020.93885.707810030.93888.102710060.94902.004210080.95 925.76910090.95940.1903
10100.95944.638410160.97945.515910210.99948.8335   10271955.533510311.02963.6913
10351.03 976.00610421.051003.60410431.051008.17210481.071037.39810500.991046.283
#Mann= 3 , 0 , 0
9499.013   0.055       09499.013   0.055       010500.99   0.055       0
#XS Ineff= 2 , 0
       0                               0
Bank Sta=9499.013,10500.99
Exp/Cntr=0.3,0.1

Type RM Length L Ch R = 1 ,12433.49,499.919600,499.919600,499.919600
XS GIS Cut Line= 6
719303.061317598777282.987344277 719365.97774988777093.077934541
719425.197820173 776959.74875354719479.335228869776882.539898747
719582.147202248 776788.54613668719618.943786527776686.637824166
#Sta/Elev= 30
9499.132984.92179538.948973.7661 9559.91969.93919572.372969.1951 9633.63961.8568
 9805.98939.91599817.104937.39929828.228933.18469844.743928.57239874.203915.2399
9900.912907.90039916.847902.37689923.687899.35939932.782893.6353 9939.69890.2725
9960.838882.01799965.799880.947810011.15879.275110023.67880.903810046.24 881.218
10067.54886.725110083.84895.402210094.98 914.74610106.12935.570710117.11940.2591
10127.62946.014210138.14954.659110159.17960.382510169.69962.0528 10188.6961.1402
#Mann= 3 , 0 , 0
9499.132  0.0431       09499.132  0.0431       0 10188.6  0.0431       0
#XS Ineff= 2 , 0
       0                               0
Bank Sta=9499.132,10188.6
Exp/Cntr=0.3,0.1

Type RM Length L Ch R = 1 ,11933.58,249.959800,249.959800,249.959800
XS GIS Cut Line= 6
719881.625419951777368.067260116719952.998675592777251.251890979
719990.698948156777119.604864019719991.427750424777021.605988827
719963.464810803776760.424299278719968.998556188776497.060886575
#Sta/Elev= 30
9499.0921015.385 9586.63987.67859620.755978.86249675.444972.84339798.386 951.805
9838.427946.3554 9868.44938.94189898.638933.74429908.712930.07189918.785923.5193
9928.859915.57889938.933904.83399949.007892.70239979.228878.84039989.302875.8706
9999.374875.0815 10019.5876.373710039.64881.3723 10049.7881.823810119.96879.5232
10129.99 881.081   10140883.959210170.01887.725410210.03897.398910230.03907.5193
10240.03914.132810290.04952.097710340.09988.768510380.211019.623 10398.21031.239
#Mann= 3 , 0 , 0
9499.092  0.0564       09499.092  0.0564       0 10398.2  0.0564       0
#XS Ineff= 2 , 0
       0                               0
Bank Sta=9499.092,10398.2
Exp/Cntr=0.3,0.1

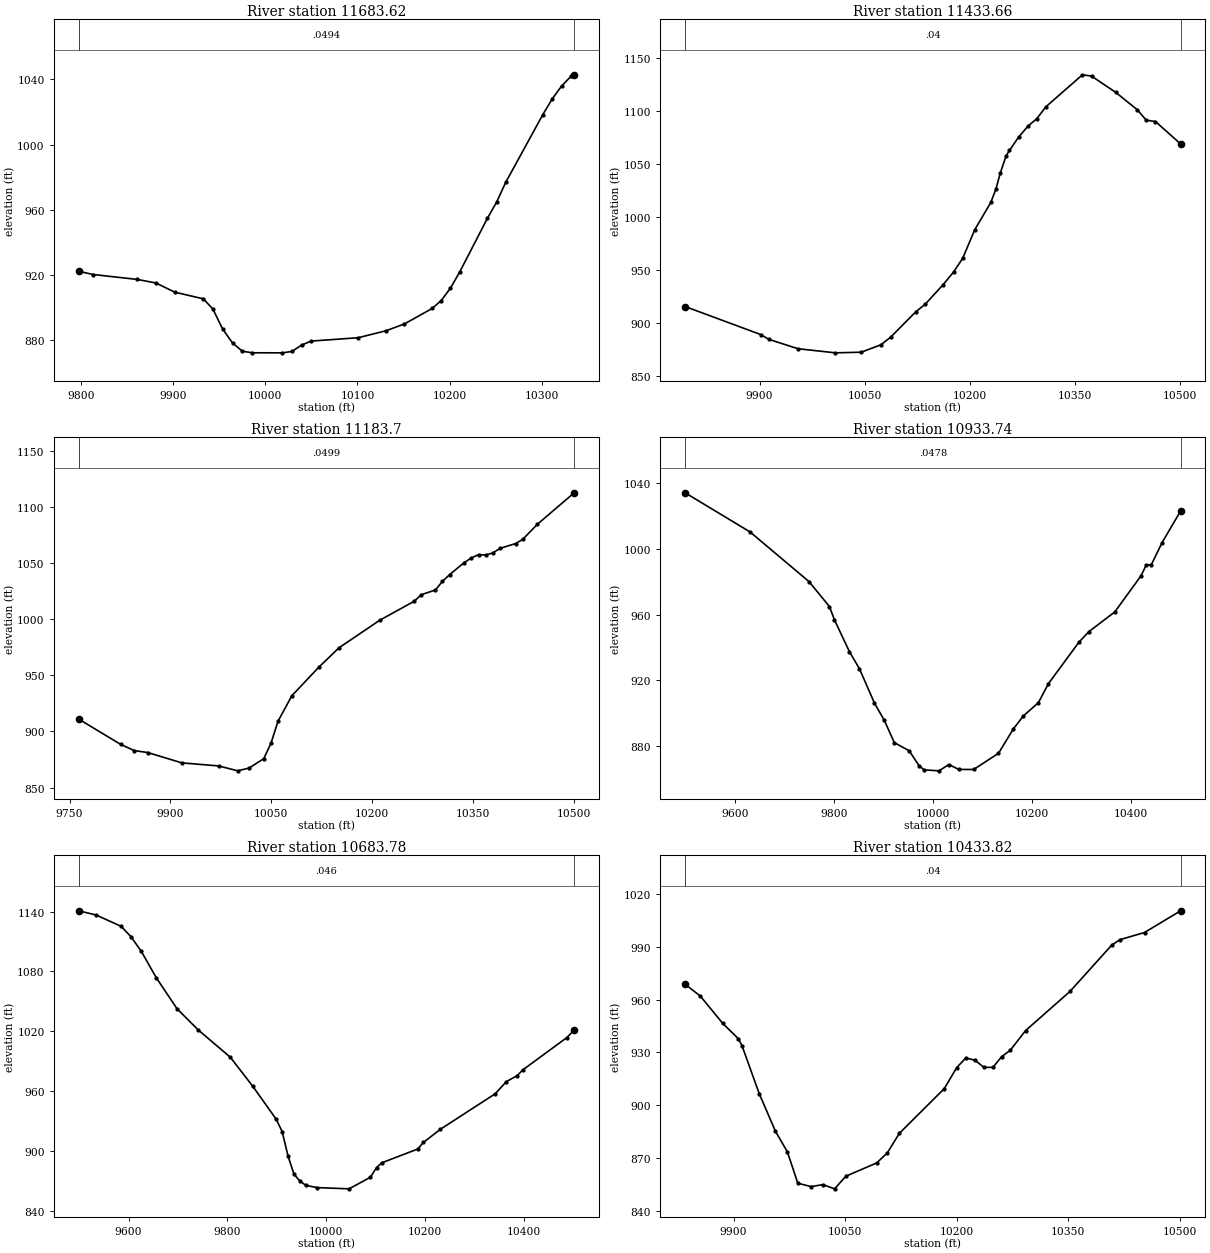
Type RM Length L Ch R = 1 ,11683.62,249.959800,249.959800,249.959800
XS GIS Cut Line= 6
720241.552478282777008.197601038720248.236551857776960.807220676
720243.475677282776912.332062318720183.005983283776711.152318821
720178.627219138776596.770840337720190.756772852776481.381012664
#Sta/Elev= 30
9797.221922.26999812.903920.28389861.021917.25579881.143915.08729901.563909.4524
9932.673905.35259943.043899.06349953.542886.87599964.301878.3027 9975.06873.2234
 9985.82872.276310018.17872.244810028.79873.076610039.25876.982510049.72879.4505
10100.71881.508910130.88885.774210150.95889.948810180.98899.443610190.98904.3392
10200.98911.974710210.98921.815610241.06954.7649 10251.1964.763610261.14977.0021
10301.291018.389 10311.41027.92610321.511035.78710331.621041.71710335.271042.763
#Mann= 3 , 0 , 0
9797.221  0.0494       09797.221  0.0494       010335.27  0.0494       0
#XS Ineff= 2 , 0
       0                               0
Bank Sta=9797.221,10335.27
Exp/Cntr=0.3,0.1

Type RM Length L Ch R = 1 ,11433.66,249.959800,249.959800,249.959800
XS GIS Cut Line= 6
720282.861388711777013.206685374720374.446967645776916.201034307
720453.005886303776852.866060719720500.370824661 776806.22219711
720604.719540741    776688.58475720764.217570751776497.443497508
#Sta/Elev= 30
9793.814915.40579901.511889.02249913.396884.43139954.941 875.59910008.32871.7286
 10045.1872.326210073.17 879.299 10087.2886.539110123.11910.502310136.48917.5794
10161.99936.029210177.06948.104410189.94960.8981 10207.2987.916510230.051013.536
10237.341026.15910243.411040.96410251.991057.71110256.661062.57610269.681075.164
10283.641085.90210295.731092.61710308.751103.86710360.85 1133.9910373.881132.726
10408.511117.293   104391101.02510452.02 1091.1310465.051089.89210500.941068.758
#Mann= 3 , 0 , 0
9793.814    0.04       09793.814    0.04       010500.94    0.04       0
#XS Ineff= 2 , 0
       0                               0
Bank Sta=9793.814,10500.94
Exp/Cntr=0.3,0.1

Type RM Length L Ch R = 1 , 11183.7,249.959800,249.959800,249.959800
XS GIS Cut Line= 6
720303.231469336777038.005044371720432.535918654777034.010609302
720581.232100235777097.369111138720684.532685499777107.482257408
720829.233914492777074.938910304721004.287090425776997.512051022
#Sta/Elev= 30
9763.444911.07539826.086888.47639846.105883.00199866.171881.23869917.073872.0341
9971.883869.306710000.22864.936510017.33 867.48410038.85875.765410049.59889.3383
10060.16909.126510080.76931.883610121.05957.389710151.08974.651610211.59999.1255
10262.951016.08510273.421021.901 10294.41026.04910304.891033.80910315.531039.752
 10336.5 1050.1510347.761054.59110358.511057.53810369.251057.119   103801059.223
10390.791063.19610413.971067.48510424.061071.06510446.231084.66410500.861112.681
#Mann= 3 , 0 , 0
9763.444  0.0499       09763.444  0.0499       010500.86  0.0499       0
#XS Ineff= 2 , 0
       0                               0
Bank Sta=9763.444,10500.86
Exp/Cntr=0.3,0.1

Type RM Length L Ch R = 1 ,10933.74,249.959900,249.959900,249.959900
XS GIS Cut Line= 6
719953.863228223777437.549284027720073.384396457777362.958328752
720178.977736668777321.040161452720283.824702807777301.309274061
720649.178149118777267.098096468720909.965671647777187.020882743
#Sta/Elev= 30
9499.0971033.9739630.364  1010.29749.635980.02169790.862964.89999801.068956.7739
9831.427937.41229851.666927.05979881.848906.2756 9901.92895.71689921.992882.2596
9952.101877.27889972.173868.20889982.209865.695910012.31865.093110032.37868.8881
10052.43 865.93610082.51865.923310132.66875.732310162.89890.606410183.07 898.479
10213.34 906.46310233.61918.014710295.03943.130610315.73949.7073 10367.8961.5965
10420.68983.480310431.26989.967110441.91990.393710463.381003.69810500.941022.937
#Mann= 3 , 0 , 0
9499.097  0.0478       09499.097  0.0478       010500.94  0.0478       0
#XS Ineff= 2 , 0
       0                               0
Bank Sta=9499.097,10500.94
Exp/Cntr=0.3,0.1

Type RM Length L Ch R = 1 ,10683.78,249.959800,249.959800,249.959800
XS GIS Cut Line= 6
720079.773692382777687.879349296720249.669489948777659.876629267
 720365.90670962 777616.68532099720498.359071288777536.948252158
720673.700425055777402.526513204 720969.78510464777258.824905251
#Sta/Elev= 30
9499.1251140.8069534.654 1136.549585.0841125.2389605.2931114.6249625.7531100.197
9656.4441073.4779697.9781042.755  9740.31021.7359805.964 994.0469851.518964.8232
9898.534931.99639910.623919.6506 9922.52895.07329934.417 877.1249946.315870.1372
9958.645865.74299981.931863.537410045.94862.316210089.07873.942910101.38883.6138
   10112888.379710184.63902.184810196.07908.748110230.42921.964610341.67957.6321
10363.67969.684910385.67975.632910396.68981.291710486.151013.81210500.961021.366
#Mann= 3 , 0 , 0
9499.125   0.046       09499.125   0.046       010500.96   0.046       0
#XS Ineff= 2 , 0
       0                               0
Bank Sta=9499.125,10500.96
Exp/Cntr=0.3,0.1

Type RM Length L Ch R = 1 ,10433.82,249.959800,249.959800,249.959800
XS GIS Cut Line= 6
720581.449872671777783.473339776720645.612467706777741.344973398
720751.349997385777616.789668169720832.780066386777543.868109648
720939.259203955777475.092633535721108.955589856777391.781147394
#Sta/Elev= 30
9834.818 968.7979855.243962.05559885.483946.46289906.378937.8111 9911.35933.7813
9934.383906.61839956.325885.07869972.273873.48599986.335855.603310004.18853.6509
10020.08854.794410035.75852.392510050.87859.5662 10092.4867.134610106.66872.8435
 10122.8883.958610183.22 909.40710199.87921.320310212.04926.795410224.22925.6329
10236.39921.512310248.56921.494110260.29927.535410271.94 931.241 10292.5942.4104
10352.22964.7036 10408.2990.987910419.24994.115510452.38998.197110500.921010.558
#Mann= 3 , 0 , 0
9834.818    0.04       09834.818    0.04       010500.92    0.04       0
#XS Ineff= 2 , 0
       0                               0
Bank Sta=9834.818,10500.92
Exp/Cntr=0.3,0.1