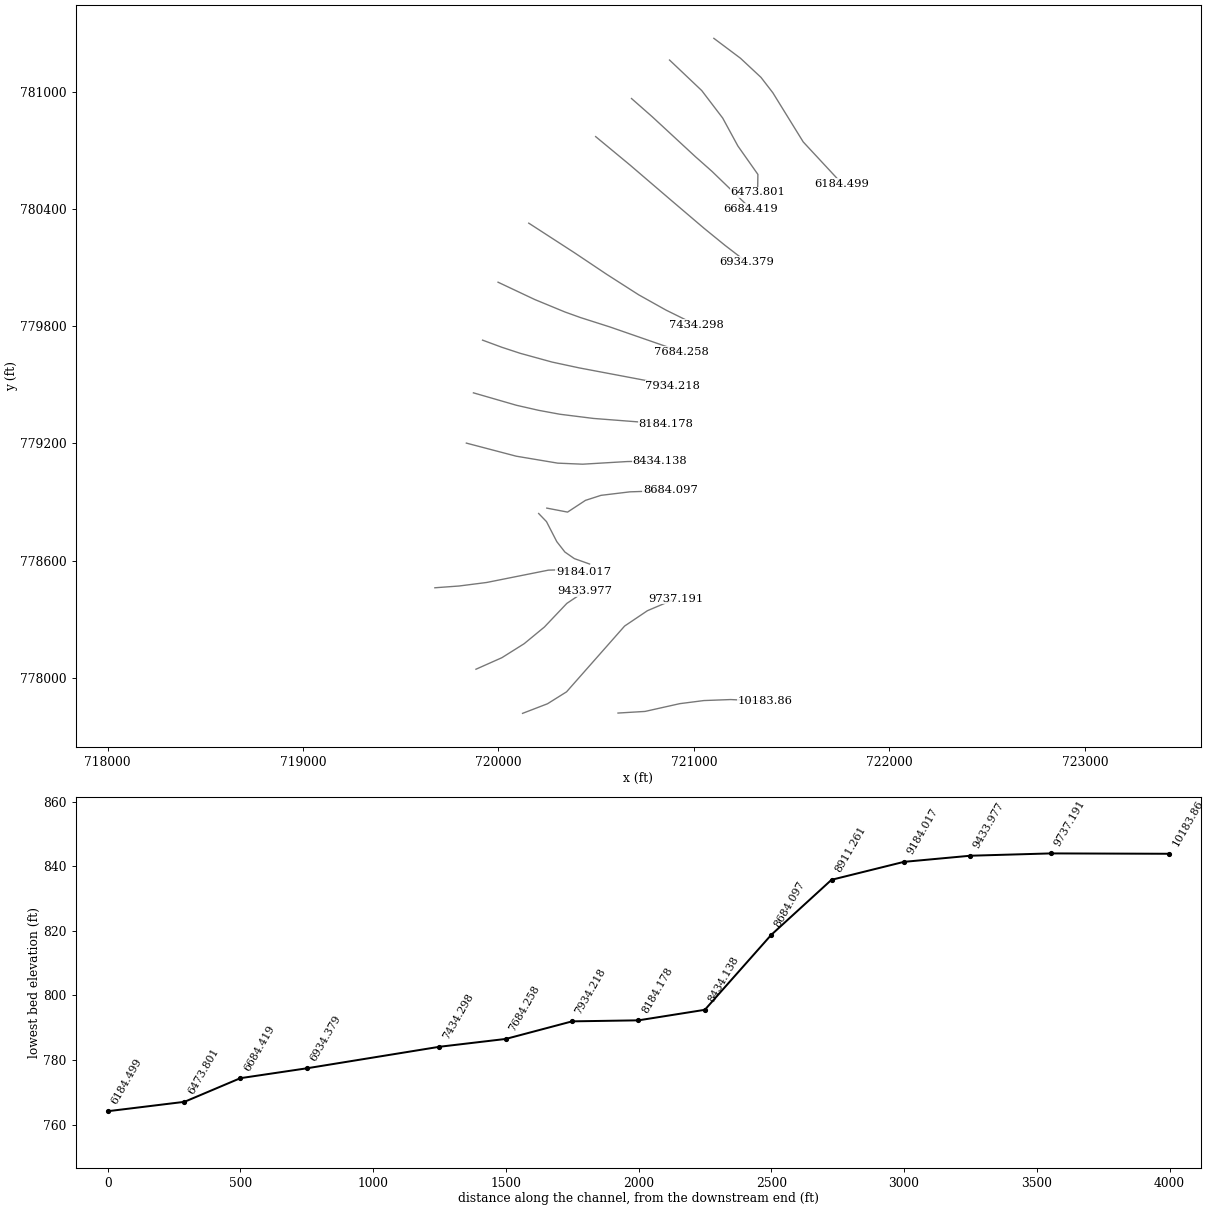
HEC-RAS study 14536_ras.prj: 14536

--- 14536_ras.g01 (geometry) --- (continued)

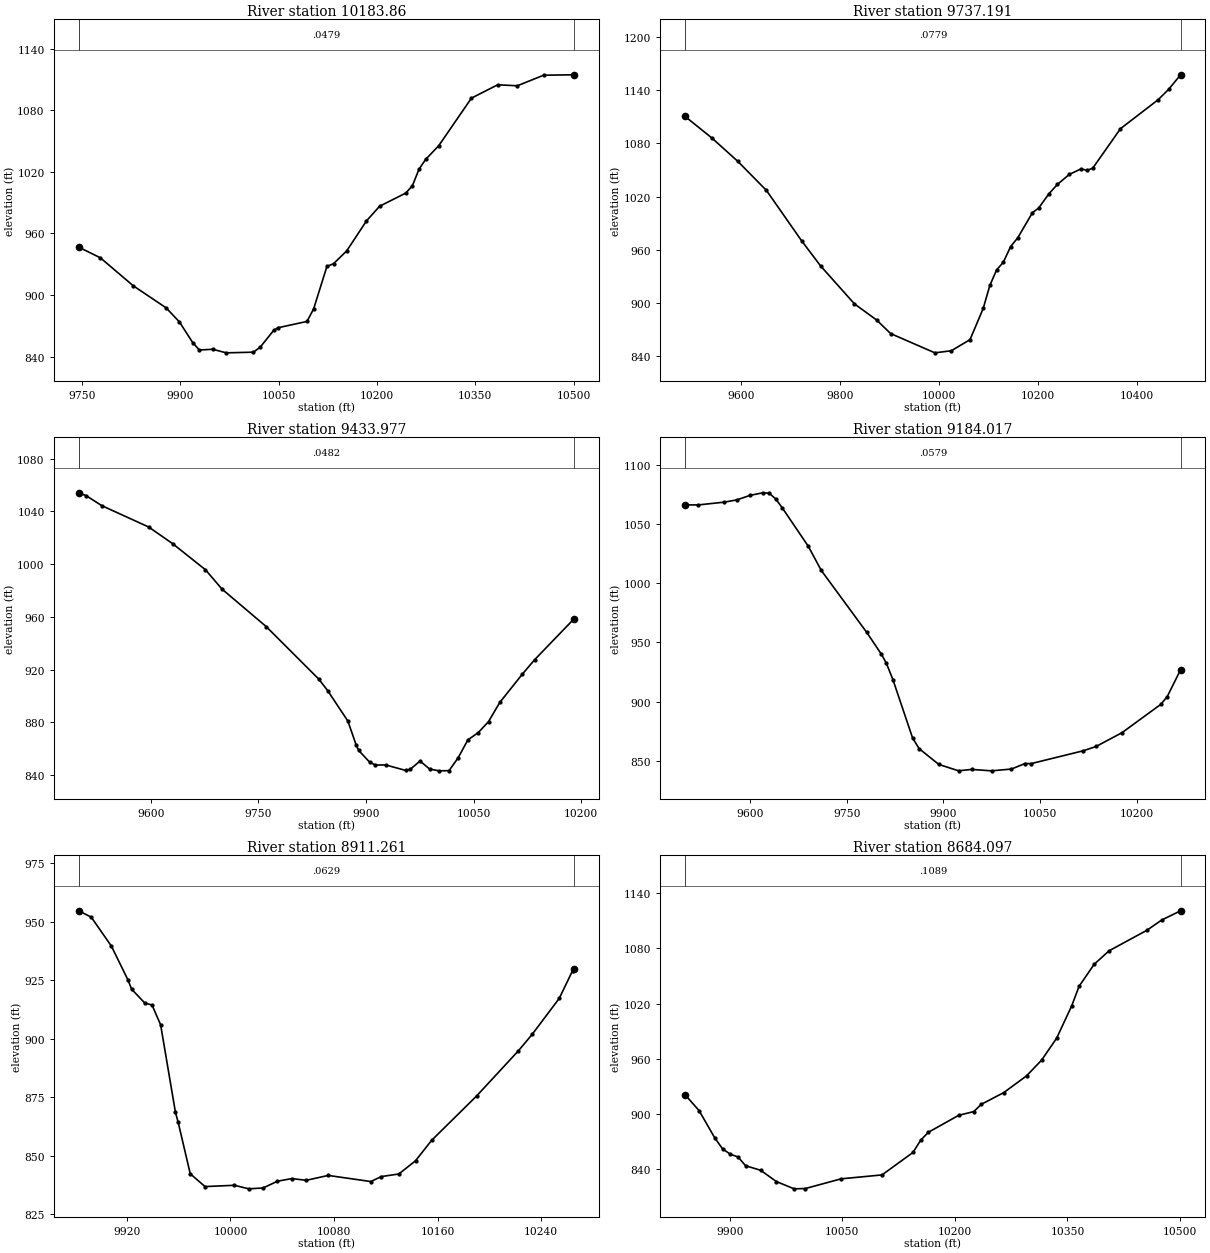
Type RM Length L Ch R = 1 ,10183.86,446.665600,446.665600,446.665600
XS GIS Cut Line= 6
720611.721093596777820.344312988 720749.99980881777828.666849184
720927.714437821777868.395245159 721051.02049102777884.268602022
 721187.76278048777889.385227573721361.530352876777881.590002583
#Sta/Elev= 30
 9744.85946.80399778.155936.27849828.231909.10449878.391887.63069898.629873.9796
9918.924853.82289929.072846.62289949.489847.3505 9970.04 843.87810011.64844.5179
10022.05849.5197 10042.5865.767610049.45 868.35710093.35874.439710103.47886.7618
 10123.7927.995110133.76930.610810153.87943.076310184.04972.269810204.09986.5335
10244.17999.381510254.181006.58510264.181022.54310274.181031.99910294.191045.345
 10344.21091.70910384.211104.68210414.221103.73910454.291114.00710500.931114.433
#Mann= 3 , 0 , 0
 9744.85  0.0479       0 9744.85  0.0479       010500.93  0.0479       0
#XS Ineff= 2 , 0
       0                               0
Bank Sta=9744.85,10500.93
Exp/Cntr=0.3,0.1

Type RM Length L Ch R = 1 ,9737.191,303.213800,303.213800,303.213800
XS GIS Cut Line= 6
720123.320863254777818.736290974720251.109064596777867.929206184
720348.463611253777928.869453713720645.358188671778265.337116826
720762.249444235778344.026762025720907.571444533778405.654221191
#Sta/Elev= 30
9486.9931110.3889541.3771085.9889593.469 1059.839651.5341026.9459722.618970.2108
9760.926941.92899829.426899.11949874.055881.04379902.584865.68169991.961843.9901
10025.16 846.336   10063 858.87110089.62893.968510103.09919.927310116.57937.2339
10130.25946.045110144.97963.6297 10159.7973.766510189.141001.92210201.761007.165
10222.061022.90710239.49 1033.7110263.92 1045.1310287.611051.32710299.45 1049.62
10311.01 1052.0310367.191096.61810443.431129.25210464.741141.04410488.781157.332
#Mann= 3 , 0 , 0
9486.993  0.0779       09486.993  0.0779       010488.78  0.0779       0
#XS Ineff= 2 , 0
       0                               0
Bank Sta=9486.993,10488.78
Exp/Cntr=0.3,0.1

Type RM Length L Ch R = 1 ,9433.977,249.959800,249.959800,249.959800
XS GIS Cut Line= 6
719884.968372896778044.593309939720017.818160688778103.659523621
720131.495311407778175.131620533720235.168270207778260.500630595
720349.800025265778381.303962347720441.168178828778442.672380789
#Sta/Elev= 30
9499.0891054.1869509.8821051.915  9531.41044.4219596.8761028.2069630.3081015.563
 9676.02 995.7829699.144981.10789760.764952.70119833.924912.94889846.562904.0959
9874.736880.9817 9886.43862.57669889.863 858.7089904.989849.88359913.085 847.671
9927.279847.76729955.697 843.5349961.873844.48069975.343850.72389988.602844.6885
10001.83843.273610015.85843.408110028.49853.129710042.13866.786710056.51872.2315
10070.89880.5889 10086.6 895.14510118.04916.572810135.06927.465110190.38958.6902
#Mann= 3 , 0 , 0
9499.089  0.0482       09499.089  0.0482       010190.38  0.0482       0
#XS Ineff= 2 , 0
       0                               0
Bank Sta=9499.089,10190.38
Exp/Cntr=0.3,0.1

Type RM Length L Ch R = 1 ,9184.017,272.755700,272.755700,272.755700
XS GIS Cut Line= 6
719674.695489299778461.273655546719798.213188335778470.307782256
719939.633609026778488.378949345720255.610147426778551.475390442
720308.589493043 778553.00327486720435.756423164778543.952747475
#Sta/Elev= 30
9499.0441066.3149519.4031066.295 9559.511068.6179579.5631070.5679599.6161074.341
 9619.671076.5669629.7341076.1749639.8151071.2799649.8961063.8219690.2221031.386
9710.3841010.9359781.063958.44979803.749940.02639811.522932.37049821.675918.4928
9852.134869.28669862.287 860.1919892.797846.82169923.485841.40499943.943842.5704
9974.798841.371610005.71842.887310026.29847.484310036.58847.531610117.24858.3454
10137.25862.035110177.35873.6586 10237.5897.580110247.52904.155210268.33926.9439
#Mann= 3 , 0 , 0
9499.044  0.0579       09499.044  0.0579       010268.33  0.0579       0
#XS Ineff= 2 , 0
       0                               0
Bank Sta=9499.044,10268.33
Exp/Cntr=0.3,0.1

Type RM Length L Ch R = 1 ,8911.261,227.163900,227.163900,227.163900
XS GIS Cut Line= 6
720205.763315384778841.244145973720245.783429663778799.742904455
720298.462153043778697.338474909720340.004517598778644.066380815
720388.336843177778610.449971707720466.204215743778582.875924249
#Sta/Elev= 30
9882.716954.59599892.457951.87259908.001939.51659920.918924.94579923.588921.1295
9933.834915.17789939.387914.34969946.051905.88479957.492868.50319959.595864.2481
9968.933  842.239980.374 836.77710003.08837.328510014.15835.811410025.22836.1904
10036.29839.064710047.36 840.19310058.58839.459710075.48  841.5410108.37838.9309
10116.51841.052210130.09842.160810142.94847.799710155.31856.487610190.06875.4483
10222.39894.775510233.01901.779110253.93917.161110264.24928.984410265.48929.8142
#Mann= 3 , 0 , 0
9882.716  0.0629       09882.716  0.0629       010265.48  0.0629       0
#XS Ineff= 2 , 0
       0                               0
Bank Sta=9882.716,10265.48
Exp/Cntr=0.3,0.1

Type RM Length L Ch R = 1 ,8684.097,249.959800,249.959800,249.959800
XS GIS Cut Line= 6
720247.359126468778868.855512965720353.653554352778848.457595826
720445.075540411778908.476157119720524.823032923778934.191668927
720672.487682982778952.073537258720880.200375515778959.128236816
#Sta/Elev= 30
9840.678921.00079859.311903.75929880.241874.07789890.549862.28179900.857856.3816
9911.165853.43339921.244843.88279941.348838.90449962.229826.69049985.938818.7448
   10001819.101710048.55829.618710103.02833.878710144.34858.328310154.48871.5422
10164.61880.149610205.15898.636210225.24902.704310235.28910.6032 10265.4 923.437
10295.52941.513310315.54958.527510335.56982.342210355.591017.301 10365.6 1038.92
10385.62 1062.7710405.621077.51910455.641099.61410475.641110.90910500.851120.941
#Mann= 3 , 0 , 0
9840.678  0.1089       09840.678  0.1089       010500.85  0.1089       0
#XS Ineff= 2 , 0
       0                               0
Bank Sta=9840.678,10500.85
Exp/Cntr=0.3,0.1

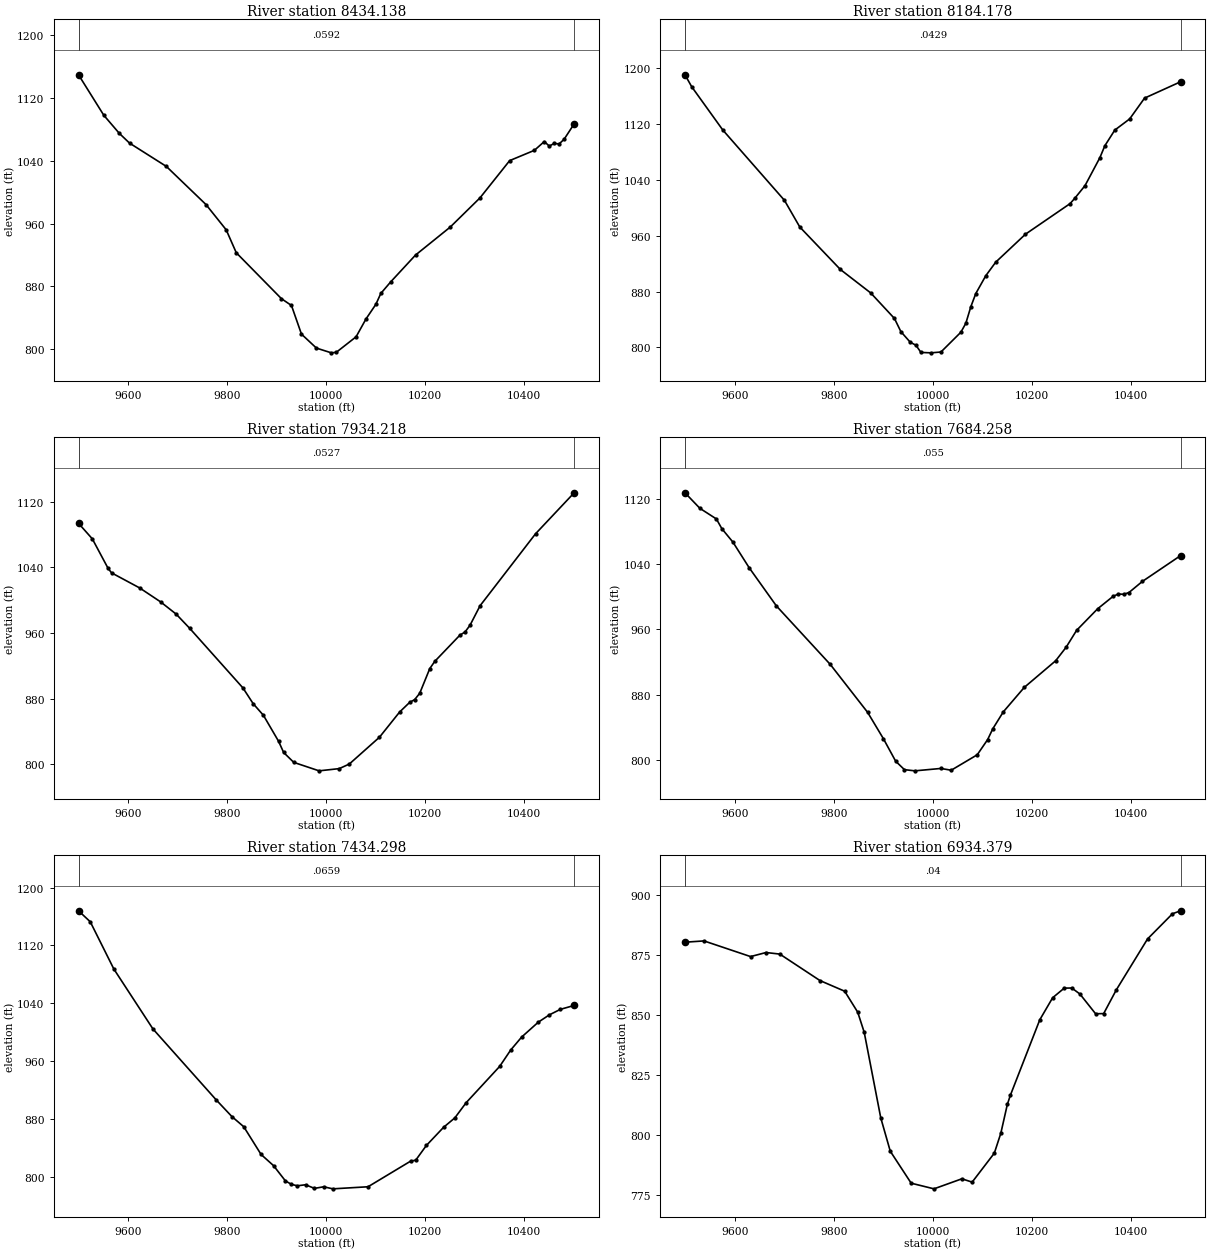
Type RM Length L Ch R = 1 ,8434.138,249.959800,249.959800,249.959800
XS GIS Cut Line= 6
719835.781006176779201.450478647720091.194649208779134.428646929
720303.221319226 779098.92539317720430.941643091779093.544342533
720658.812423273779107.089294589 720825.36921689779109.925255366
#Sta/Elev= 30
9499.0481149.3949550.195 1097.86 9581.371074.9479602.1531062.4539676.6141032.772
9756.773984.22269797.582952.08119817.952922.91469909.327864.42029929.519855.8141
9949.711819.36079979.989801.580210010.09795.5418 10020.1796.196810060.16815.9623
10080.16838.654910100.16857.309610110.17871.1661 10130.2885.901410180.29919.9737
10250.41955.570310310.52992.687510370.581040.14910420.591053.265 10440.61064.435
 10450.61058.676 10460.61062.006 10470.6 1061.39 10480.61067.30610500.971086.934
#Mann= 3 , 0 , 0
9499.048  0.0592       09499.048  0.0592       010500.97  0.0592       0
#XS Ineff= 2 , 0
       0                               0
Bank Sta=9499.048,10500.97
Exp/Cntr=0.3,0.1

Type RM Length L Ch R = 1 ,8184.178,249.959800,249.959800,249.959800
XS GIS Cut Line= 6
719872.008463226779458.578877654720092.287233935779394.970577907
720206.445941194779368.980437091720313.630864654779349.210556396
 720486.02211437779327.659380561720857.709923843 779298.86325624
#Sta/Elev= 30
 9499.03 1190.189512.635 1173.059575.4711111.1419700.0821010.5459731.131 972.343
9813.178911.55199874.464878.01349922.504841.42599935.476822.62389954.422 807.454
9965.922803.16719976.037792.86129996.268792.280910016.45793.451210056.75821.7681
10066.81834.638510076.87858.273910086.93877.154610107.04902.546910127.16922.0078
10187.34962.072610277.611005.85410287.641013.978 10307.7 1031.5510337.791071.611
10347.821088.65110367.881111.01210397.97 1127.0110428.061156.77510500.991180.197
#Mann= 3 , 0 , 0
 9499.03  0.0429       0 9499.03  0.0429       010500.99  0.0429       0
#XS Ineff= 2 , 0
       0                               0
Bank Sta=9499.03,10500.99
Exp/Cntr=0.3,0.1

Type RM Length L Ch R = 1 ,7934.218,249.959800,249.959800,249.959800
XS GIS Cut Line= 6
719918.800908697779728.176750594720017.828001169779691.576271581
720110.958100889779660.940433586720274.485896663779615.982439918
720412.986581167779586.267765129 720891.60910844779495.938581944
#Sta/Elev= 30
9499.0261093.5169526.9581074.5479558.9411038.482 9565.881033.1279622.6781014.754
9664.787997.87559696.368982.91879723.918965.48939831.501892.89899852.145873.7458
9872.784859.6588 9903.48  827.959913.712814.30639934.176802.27169985.337791.9651
10026.13 794.67210046.46800.253210107.46832.956710148.13863.594710168.47875.3692
10178.63878.7782 10188.8886.444710209.14916.5646 10219.3925.375710270.14957.3441
10280.31961.046310290.47969.327110310.81993.114510422.891080.715   105011130.691
#Mann= 3 , 0 , 0
9499.026  0.0527       09499.026  0.0527       0   10501  0.0527       0
#XS Ineff= 2 , 0
       0                               0
Bank Sta=9499.026,10501
Exp/Cntr=0.3,0.1

Type RM Length L Ch R = 1 ,7684.258,249.959800,249.959800,249.959800
XS GIS Cut Line= 6
719997.917445779780024.614151548720185.564386419779936.107504258
720340.207550058779872.274933552720419.889719357779843.671327949
720570.533458013779795.583708285720933.669175222779669.592104231
#Sta/Elev= 30
9499.0191127.5349529.1321108.477 9562.491095.4519573.6091083.4599595.8481067.101
9628.9741035.4269683.912988.69589792.853916.94419868.218 858.2739900.162825.8999
 9924.95798.30889942.661787.95719963.833786.517410016.24789.436810037.25 787.276
10089.79806.1972 10110.8824.783410121.34 838.14410142.51858.826610184.85888.8134
10248.36921.517110269.53938.1154 10290.7958.831710333.04985.157810364.791000.691
10375.381003.38610385.961003.00710396.55 1005.2110423.471018.74310500.99 1050.52
#Mann= 3 , 0 , 0
9499.019   0.055       09499.019   0.055       010500.99   0.055       0
#XS Ineff= 2 , 0
       0                               0
Bank Sta=9499.019,10500.99
Exp/Cntr=0.3,0.1

Type RM Length L Ch R = 1 ,7434.298,499.919600,499.919600,499.919600
XS GIS Cut Line= 6
720155.047240047780326.760241836720388.573072206780175.549996125
720553.882979562780064.917977575720717.385077671779960.217428335
720857.506555056779881.781387353 721010.11404101779806.671174307
#Sta/Elev= 30
9499.0041167.8829522.7741152.6739570.4271087.4899649.4321004.816 9777.21906.9652
9809.009883.88349833.075869.79099868.098831.51879893.239816.11939917.304795.0189
9929.337790.3043 9941.37788.29469957.997789.71299975.977784.7219 9994.63786.9081
10013.23784.089310084.28786.950510170.28  822.2810180.66823.650210202.22843.9529
10236.92 868.97310259.86882.093910282.58902.976910350.38953.075110372.67975.6918
10394.96 993.69210428.391014.09910450.69 1024.1810472.981031.79910500.971037.232
#Mann= 3 , 0 , 0
9499.004  0.0659       09499.004  0.0659       010500.97  0.0659       0
#XS Ineff= 2 , 0
       0                               0
Bank Sta=9499.004,10500.97
Exp/Cntr=0.3,0.1

Type RM Length L Ch R = 1 ,6934.379,249.959800,249.959800,249.959800
XS GIS Cut Line= 6
720497.320229315780769.530373283720673.074161571780624.074921507
720881.047951737780445.905708166721052.633004919780299.864038283
721159.322473741780213.030962858721268.055238697780129.511178053
#Sta/Elev= 30
9499.006880.2437 9537.48880.77379631.586874.25099662.955875.93929690.702875.2868
9771.835864.25889821.852859.80489848.188851.07259861.355842.67499894.802806.9996
9914.025793.10149956.286779.7684 10002.4777.416910058.72   781.610079.54780.2161
10124.38792.302210137.51800.597510150.64812.587210156.68816.3669 10216.3847.9083
10242.27857.087410265.71861.098510280.95 861.14710297.39858.637210329.08850.4089
10345.41850.480910371.04860.401210434.09881.598610484.53892.107910500.99893.3438
#Mann= 3 , 0 , 0
9499.006    0.04       09499.006    0.04       010500.99    0.04       0
#XS Ineff= 2 , 0
       0                               0
Bank Sta=9499.006,10500.99
Exp/Cntr=0.3,0.1

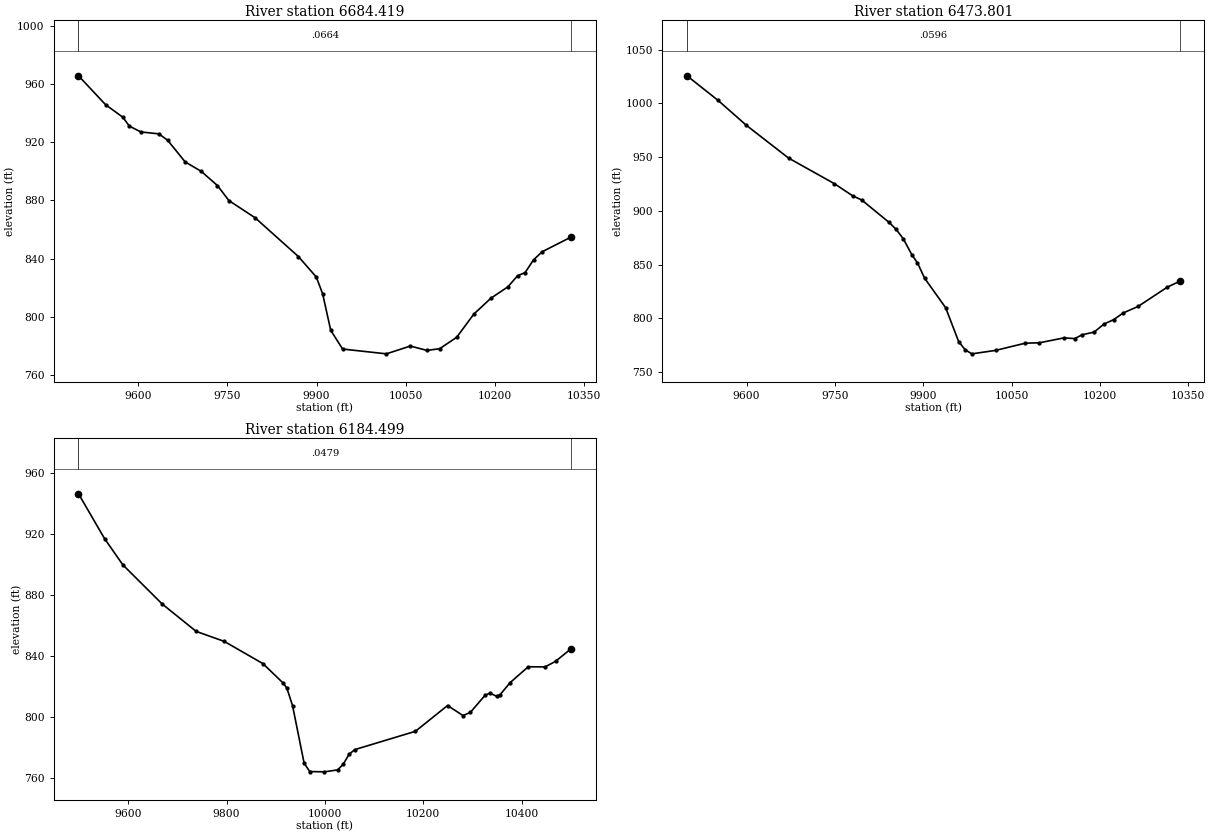
Type RM Length L Ch R = 1 ,6684.419,210.618300,210.618300,210.618300
XS GIS Cut Line= 6
720680.733847501780964.387430099720787.317056766780870.660909919
721006.596904564780667.798461309721052.532297253780627.162838151
721092.869533422780591.358426524721290.102189271780400.793304795
#Sta/Elev= 30
9499.013965.83869544.643945.92189573.801937.26959584.593931.18929604.087927.1612
9634.374925.83929649.281921.40739678.657906.52289705.903 900.0069733.149890.2133
9752.359879.90759796.536868.04739869.379841.38729899.614827.23849910.248815.7171
9923.871790.6021 9943.89777.659810017.67774.3618 10057.9779.731210085.71776.7386
10107.26 777.87110136.04785.752510164.83801.683810193.61 812.63510222.39820.5236
10238.66828.169910251.18830.259710265.57839.118510279.96844.650510329.19854.8552
#Mann= 3 , 0 , 0
9499.013  0.0664       09499.013  0.0664       010329.19  0.0664       0
#XS Ineff= 2 , 0
       0                               0
Bank Sta=9499.013,10329.19
Exp/Cntr=0.3,0.1

Type RM Length L Ch R = 1 ,6473.801,289.301400,289.301400,289.301400
XS GIS Cut Line= 6
720875.300269186781161.296926931721040.139886528781005.010725558
721147.333140224780864.319650352721225.089532435780721.347622469
721327.417828828780576.091813251721325.843448341780484.030921161
#Sta/Elev= 30
9498.7831025.6999551.4881002.8779599.577979.65529671.246949.18659749.115925.3406
9780.065914.07859795.655910.11199841.931889.36569854.107882.78969866.169874.0734
9881.127858.81249890.295851.71579902.358837.42489938.116809.97519960.279778.3767
9971.509770.66049982.738767.034410023.17770.256810073.47776.965310097.09777.2776
10139.25781.903410157.44781.199810169.65784.710710190.39787.3047 10207.4794.8493
10223.33798.7752 10239.8805.087810264.88811.085810314.88829.171610335.86834.5559
#Mann= 3 , 0 , 0
9498.783  0.0596       09498.783  0.0596       010335.86  0.0596       0
#XS Ineff= 2 , 0
       0                               0
Bank Sta=9498.783,10335.86
Exp/Cntr=0.3,0.1

Type RM Length L Ch R = 1 ,6184.499,249.959800,249.959800,249.959800
XS GIS Cut Line= 6
721102.054330589781272.310215631721238.238422423781170.448063936
721343.223072065781072.552634753721403.795310858780993.937853859
721559.379732182780742.181028477721758.245018511780528.112008644
#Sta/Elev= 30
9499.072946.63449552.096917.18089589.137900.01949669.166874.2967 9738.28856.3079
9795.364849.74869873.988835.15299914.447822.59899922.611819.1659 9934.33 807.402
9957.673769.8871 9969.06764.3152    9999764.121410025.92765.395910037.28769.1256
10048.87775.505510060.47778.688410183.95790.723410249.37807.665210280.74801.0432
 10295.8803.168610325.94 814.50710335.67815.766710349.03 813.71910355.89814.6837
10376.77822.758510413.34833.085310447.52832.996210468.84836.642910500.96845.0639
#Mann= 3 , 0 , 0
9499.072  0.0479       09499.072  0.0479       010500.96  0.0479       0
#XS Ineff= 2 , 0
       0                               0
Bank Sta=9499.072,10500.96
Exp/Cntr=0.3,0.1