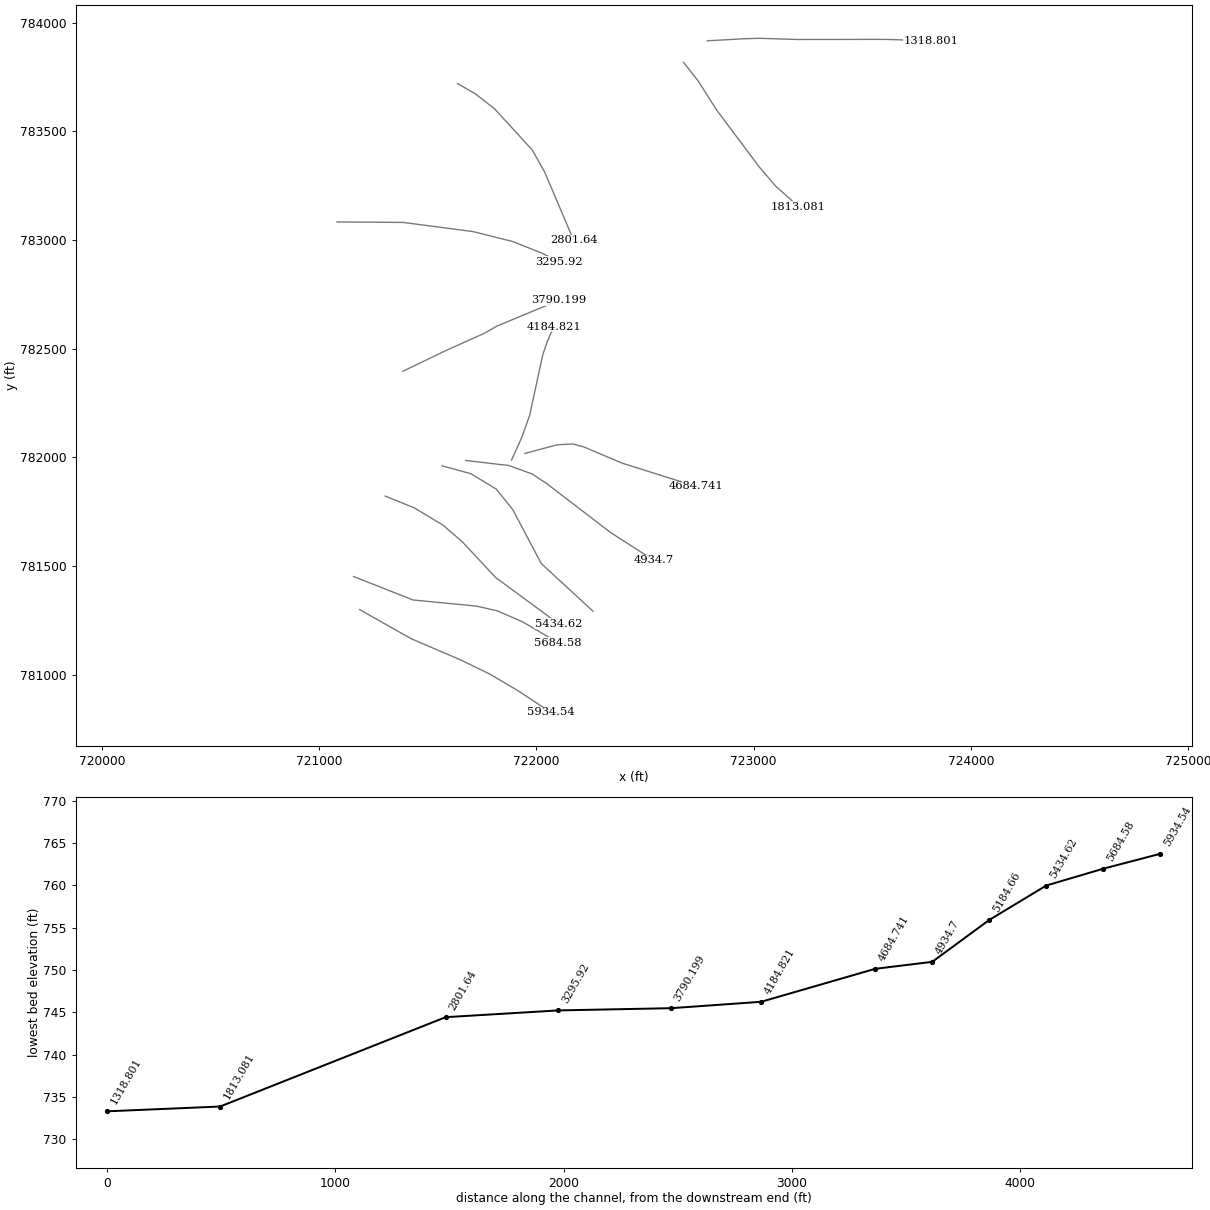
HEC-RAS study 14536_ras.prj: 14536

--- 14536_ras.g01 (geometry) --- (continued)

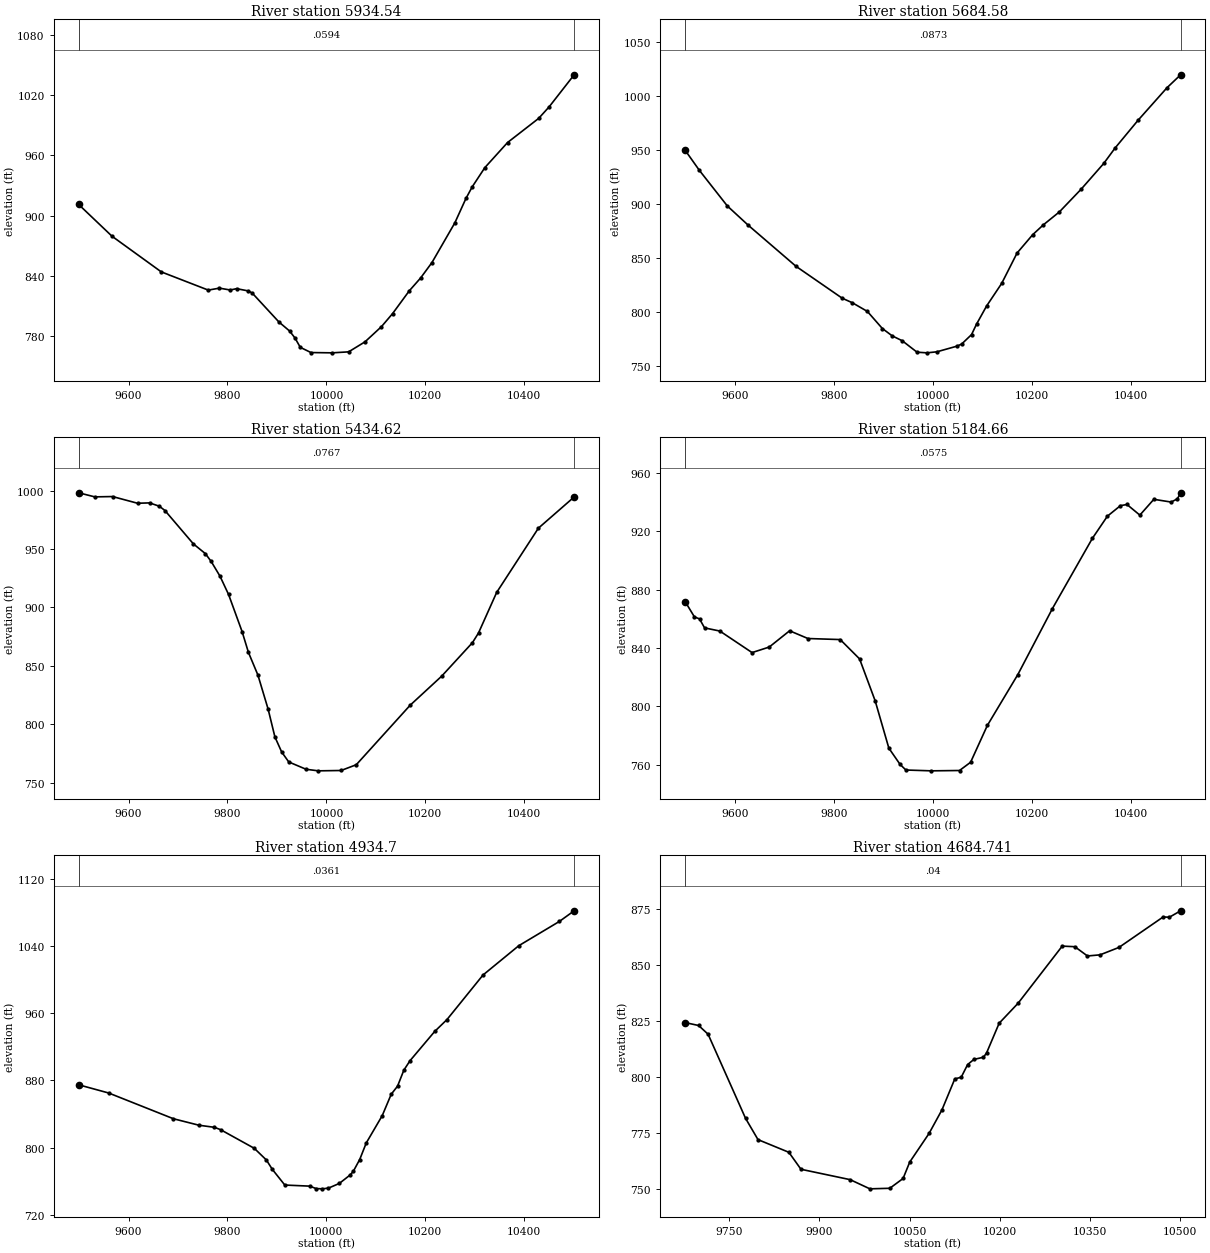
Type RM Length L Ch R = 1 , 5934.54,249.959800,249.959800,249.959800
XS GIS Cut Line= 6
721186.828704365781298.891490169721426.016178044781163.979613226
721650.615233994781067.910317923721785.773255122781002.181530713
721915.824628229780925.535327682722067.337238468780825.406677239
#Sta/Elev= 30
9499.045911.22829566.519879.63629666.218844.17939761.187826.08839783.625828.0361
9805.714826.18669818.418827.52589841.977825.27589849.891823.2314 9904.06794.3823
9925.644785.40119936.436  778.529947.227769.20919968.811764.022210011.98763.7381
10044.96764.720410078.05 774.67810111.38789.808710133.83 802.75510167.52825.3381
10190.47838.132810213.44 853.48910259.74 892.95410282.13  917.1710294.94928.8178
10320.34947.799710366.32972.780410429.16996.757910450.231008.15910500.971040.099
#Mann= 3 , 0 , 0
9499.045  0.0594       09499.045  0.0594       010500.97  0.0594       0
#XS Ineff= 2 , 0
       0                               0
Bank Sta=9499.045,10500.97
Exp/Cntr=0.3,0.1

Type RM Length L Ch R = 1 , 5684.58,249.959800,249.959800,249.959800
XS GIS Cut Line= 6
721158.802533637781451.196525894721432.911374968 781343.20510805
721724.633333448781315.040662569721820.506654611781292.986365968
721936.188554609781242.975428823722098.580174787781147.479969305
#Sta/Elev= 30
 9499.06949.66639527.978930.9537 9584.54 897.9629626.838880.10589723.393842.0805
9816.764812.54989837.203808.36299867.571800.33359897.838 784.514 9917.92777.6577
9937.965773.20239967.997 762.5729988.004761.977110008.01762.928610048.06768.0869
 10058.1770.079910078.18778.865210088.23788.515410108.57805.328210139.07826.2399
10170.22854.418910201.86871.425110223.26880.480310255.78892.502310300.08913.6907
10345.44937.378510368.32 951.63910414.57977.233510473.241007.45910500.911019.501
#Mann= 3 , 0 , 0
 9499.06  0.0873       0 9499.06  0.0873       010500.91  0.0873       0
#XS Ineff= 2 , 0
       0                               0
Bank Sta=9499.06,10500.91
Exp/Cntr=0.3,0.1

Type RM Length L Ch R = 1 , 5434.62,249.959800,249.959800,249.959800
XS GIS Cut Line= 6
721304.385609197781821.383301198721437.266921556781767.570709275
721570.234124817  781687.7901929 721657.98078155781612.219008064
721812.909684329781446.347572251722103.039322537781233.303540824
#Sta/Elev= 30
9499.078998.05989531.706994.55769567.644  994.839618.189989.09399642.508989.4009
9662.373986.53089673.575982.86379731.102954.2882 9755.24945.98069767.041939.2756
9784.897926.63039802.221910.9907 9829.56879.20829842.396861.38369861.552841.9802
9882.191812.81519895.882789.05459909.572776.12069923.906767.59099958.889761.3339
9983.642759.987610029.74760.282810060.44765.225910169.39816.185810233.01 841.028
10295.29869.736610307.53878.020610344.24912.7337 10428.6967.753910500.94994.4804
#Mann= 3 , 0 , 0
9499.078  0.0767       09499.078  0.0767       010500.94  0.0767       0
#XS Ineff= 2 , 0
       0                               0
Bank Sta=9499.078,10500.94
Exp/Cntr=0.3,0.1

Type RM Length L Ch R = 1 , 5184.66,249.959800,249.959800,249.959800
XS GIS Cut Line= 6
721566.557724102 781960.41243294721698.688270833781924.431717712
721815.575601319781853.394223828721890.754075006781760.107790174
722022.921509322781510.645871368722260.227115966781291.859359454
#Sta/Elev= 30
9499.131871.87119518.018861.31199528.259859.9863  9538.5853.8113 9569.36851.6522
9634.514836.90079669.226840.69129710.431851.83179747.478846.5343 9812.75845.8144
9851.866832.56479883.422803.80729911.045  771.459933.709760.33439945.465756.4847
9996.875755.920210053.89756.148810076.28 761.79310110.22787.048510171.85821.8865
10241.77867.084910322.34 915.05310352.85930.309810379.24937.521810392.43 938.314
10418.45931.033610446.71941.857410481.65939.984710494.29942.1666 10500.9946.3357
#Mann= 3 , 0 , 0
9499.131  0.0575       09499.131  0.0575       0 10500.9  0.0575       0
#XS Ineff= 2 , 0
       0                               0
Bank Sta=9499.131,10500.9
Exp/Cntr=0.3,0.1

Type RM Length L Ch R = 1 ,  4934.7,249.959800,249.959800,249.959800
XS GIS Cut Line= 6
721674.598236812781985.278936254721873.214533415781961.966863778
 721979.73645763781923.422284868722047.512190628 781878.99967998
 722340.13965538781654.655977898722540.505428018781525.734360556
#Sta/Elev= 30
9499.084874.74259559.767864.98219690.833834.32819742.464826.63559773.714824.1396
9786.025821.36889854.248799.17119878.637785.30959890.831774.0311 9915.95 755.486
9966.396754.19459979.008751.32479991.619750.975910004.13751.8329 10026.1757.3742
10048.39767.644310054.62772.044810067.37785.850410080.63805.599110112.87837.9915
10131.12863.528910143.88873.135710156.63892.167510169.17903.458410218.94938.1474
10243.82952.319310316.681005.31810388.941040.15110471.081069.03910500.971081.718
#Mann= 3 , 0 , 0
9499.084  0.0361       09499.084  0.0361       010500.97  0.0361       0
#XS Ineff= 2 , 0
       0                               0
Bank Sta=9499.084,10500.97
Exp/Cntr=0.3,0.1

Type RM Length L Ch R = 1 ,4684.741,499.919600,499.919600,499.919600
XS GIS Cut Line= 6
721947.842881551782017.729273939722095.693106914782057.365474935
722168.936867572782061.014711277722218.047609202 782047.73712016
722395.131529082781972.894084401722732.796518364781866.173879335
#Sta/Elev= 30
9676.741824.32519699.247 823.0229714.981819.1338 9777.24781.63089797.994772.1104
9849.312766.4572 9869.48758.87779951.234754.25329984.113 750.15310017.23750.4017
10039.31754.774710050.36762.086910082.58774.894410103.95785.373510125.32799.1962
10136.01799.944810146.69805.613310157.18807.900110173.03808.863910178.16810.7776
10199.13824.046410230.59832.945910304.01858.437410324.98858.174510345.96854.0359
10366.93854.542110398.39857.855310471.81871.4311 10482.3871.334510500.96874.2012
#Mann= 3 , 0 , 0
9676.741    0.04       09676.741    0.04       010500.96    0.04       0
#XS Ineff= 2 , 0
       0                               0
Bank Sta=9676.741,10500.96
Exp/Cntr=0.3,0.1

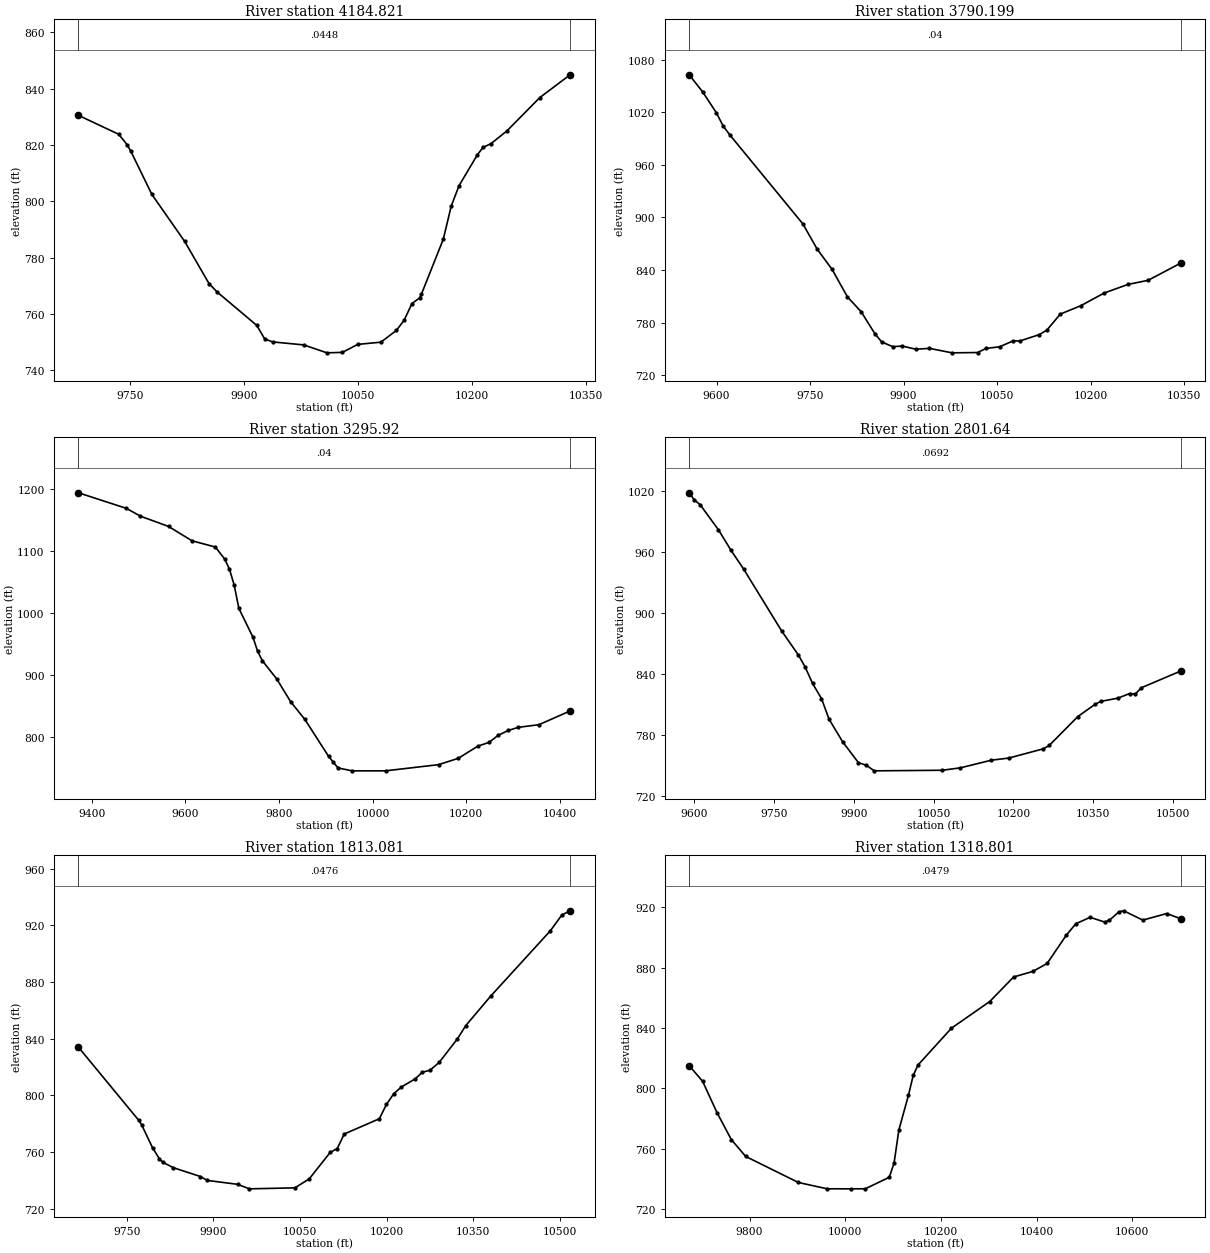
Type RM Length L Ch R = 1 ,4184.821,394.621600,394.621600,394.621600
XS GIS Cut Line= 6
721885.904699194781987.103643746721932.666095387  782090.7480015
721969.058377637782192.561122614722029.356643318782471.177602567
722049.032428326782529.579912805722080.034847182782601.241952458
#Sta/Elev= 30
9682.167830.53829735.141823.8148 9746.11820.15539751.082817.81219778.754802.4814
9821.862785.83269853.973770.84049864.501 767.8879916.873755.97399927.188751.2096
9937.503750.1414 9978.62749.071410009.15746.258410029.42746.417410049.69749.2627
 10080.1750.042210100.52754.213310110.74757.839910120.96763.741110131.19 765.785
10133.45767.074910162.23786.589810172.58 798.26810182.93805.583910206.99816.5067
10214.46819.152710225.01820.499910246.11 825.053 10289.2836.844510329.06844.9318
#Mann= 3 , 0 , 0
9682.167  0.0448       09682.167  0.0448       010329.06  0.0448       0
#XS Ineff= 2 , 0
       0                               0
Bank Sta=9682.167,10329.06
Exp/Cntr=0.3,0.1

Type RM Length L Ch R = 1 ,3790.199,494.279700,494.279700,494.279700
XS GIS Cut Line= 6
721385.856574078782395.683605109721581.416638326 782490.06996024
721756.944908708782568.915203047721819.969986052782604.290852267
722090.560463505782716.778584815722103.620743576782721.711989974
#Sta/Elev= 30
9555.9621062.7859577.3961043.4569599.4261019.643 9610.531004.2599621.634993.7712
9738.438892.60379761.444863.6867 9785.14840.87629809.924809.32159831.849792.4606
9853.774767.48059864.737 757.9599882.761752.52249897.625753.3034 9919.55749.6147
9941.475750.61219977.892745.503710018.62745.832310032.13750.526410054.09752.3975
10075.75759.156510086.58759.068110117.81766.3159 10129.9771.504310151.55789.7632
10184.04799.193610222.01813.795310259.85823.544310292.34828.281610344.81847.9625
#Mann= 3 , 0 , 0
9555.962    0.04       09555.962    0.04       010344.81    0.04       0
#XS Ineff= 2 , 0
       0                               0
Bank Sta=9555.962,10344.81
Exp/Cntr=0.3,0.1

Type RM Length L Ch R = 1 , 3295.92,494.279700,494.279700,494.279700
XS GIS Cut Line= 6
721082.599367171783082.907354366721386.770472238783080.768356866
721708.911907582783038.579768936721889.375105808782993.279476387
722022.908697337782940.459231406 722104.37689353782899.835707989
#Sta/Elev= 30
9371.5981193.9939474.0591168.8219504.0641156.224 9564.071139.688  9614.11116.521
9664.1661106.4299684.2141086.8399694.2551070.5839704.295 1045.059714.336 1007.35
9744.457960.87959754.498937.90799764.538 922.8599794.729894.03429824.989 856.686
 9855.25828.28019905.793768.84489915.932 759.331 9926.07749.95159956.485745.2413
10027.58745.241310140.94755.239110182.63 765.33210225.03 785.15710248.82791.1632
10267.94802.400310289.67810.390310311.39 815.44710355.45819.742610421.89841.8874
#Mann= 3 , 0 , 0
9371.598    0.04       09371.598    0.04       010421.89    0.04       0
#XS Ineff= 2 , 0
       0                               0
Bank Sta=9371.598,10421.89
Exp/Cntr=0.3,0.1

Type RM Length L Ch R = 1 , 2801.64,988.559400,988.559400,988.559400
XS GIS Cut Line= 6
721636.833622538783720.140707389721718.506512829783673.160184359
721807.731866585783603.516364753721980.648780902783414.754003184
722037.425475376783314.517538503 722172.02282357782998.031412889
#Sta/Elev= 30
 9591.121018.0079600.4331011.1999611.8371006.1789646.049 981.6199669.369961.6518
9693.379  942.95 9765.15 881.7539796.336858.33669808.794846.69899822.752830.4801
9839.525 815.5839853.859795.16559879.115773.16549908.814752.56339923.803749.9191
9938.699 744.44210066.47745.0152 10100.4747.403410158.44754.893710191.49757.0311
10256.44766.157110267.18769.383610320.92797.847510353.16809.841410363.91812.7338
10396.15815.964610418.02820.4479   10429820.008310439.98826.147110514.34842.6718
#Mann= 3 , 0 , 0
 9591.12  0.0692       0 9591.12  0.0692       010514.34  0.0692       0
#XS Ineff= 2 , 0
       0                               0
Bank Sta=9591.12,10514.34
Exp/Cntr=0.3,0.1

Type RM Length L Ch R = 1 ,1813.081,494.279700,494.279700,494.279700
XS GIS Cut Line= 6
722677.636287376783817.147396408722744.055935712 783732.53293313
722830.054330223783597.575370547723025.806585831783336.037927337
723100.878957491783248.189220284723206.486984745783153.789806018
#Sta/Elev= 30
9666.029833.90839770.645 782.2039775.468 779.1859794.502762.8591 9806.36755.0854
9812.685752.59029830.075748.88279877.506742.58369889.364739.83499941.827737.0793
9962.276733.889610041.12734.578710065.98740.903410102.41759.643410114.55762.3321
10126.69772.602710187.48783.3635 10199.9793.504310212.32800.956710225.63805.7898
10249.58811.523910262.05816.220110275.34817.636410291.24823.170510322.44839.5661
10337.45849.200410380.89870.139610483.71916.013510503.87927.250910518.12930.2197
#Mann= 3 , 0 , 0
9666.029  0.0476       09666.029  0.0476       010518.12  0.0476       0
#XS Ineff= 2 , 0
       0                               0
Bank Sta=9666.029,10518.12
Exp/Cntr=0.3,0.1

Type RM Length L Ch R = 1 ,1318.801,0.000000,0.000000,0.000000
XS GIS Cut Line= 6
722786.932093172783916.695343382722958.185684574783926.044750043
723025.176311296783928.089151686723201.082884586783922.604310148
723599.807002729783923.082586223723814.515255615783917.070309113
#Sta/Elev= 30
9673.619815.04729701.728804.62659731.773783.86839761.818 765.9429791.863754.7867
9901.968737.54279961.995733.364710012.02733.324310042.04733.364710092.06741.0112
10102.06750.415210112.06772.312410132.06795.311710142.06 808.48510152.06815.4072
10222.06839.846610302.06857.499610352.06 873.80710392.06877.458110422.06 882.744
10462.06901.444110482.06909.074910512.07913.356210542.08910.242110552.09911.3286
10572.09916.9578 10582.1917.686510622.11911.512310672.13915.850310701.66912.3975
#Mann= 3 , 0 , 0
9673.619  0.0479       09673.619  0.0479       010701.66  0.0479       0
#XS Ineff= 2 , 0
       0                               0
Bank Sta=9673.619,10701.66
Exp/Cntr=0.3,0.1